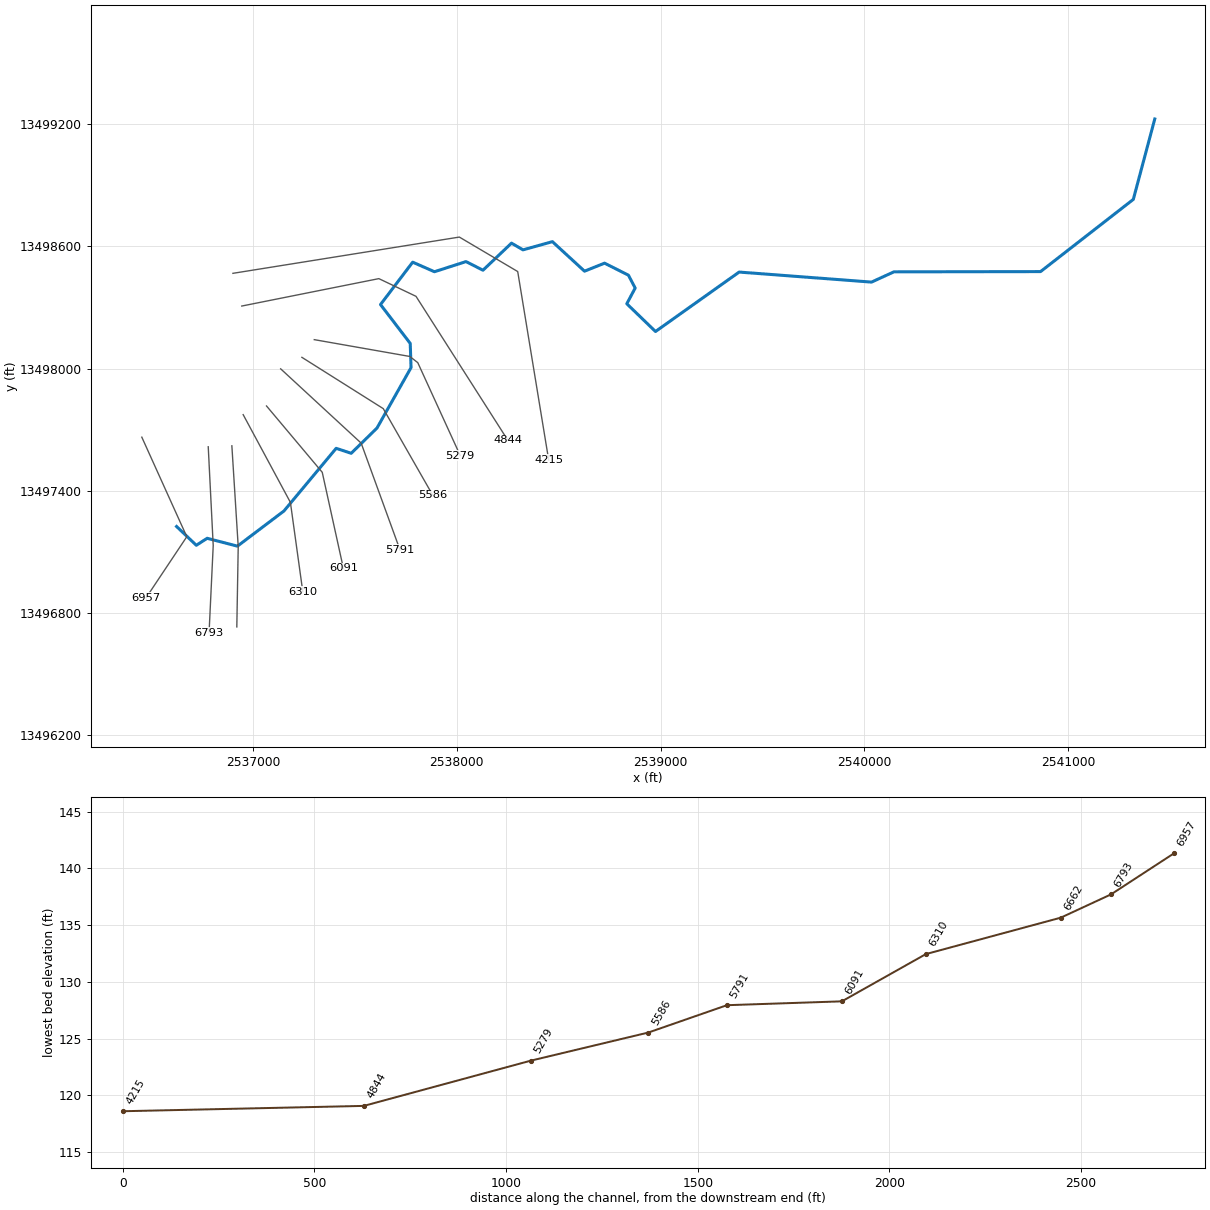
--- TRIB 5 TO COLETO CREEK.prj (project) ---

Proj Title=TRIB 5 TO COLETO CREEK Base Level Engineering
Current Plan=p01
Default Exp/Contr=0.3,0.1
English Units
Geom File=g01
Flow File=f01
Plan File=p01
Y Axis Title=Elevation
X Axis Title(PF)=Main Channel Distance
X Axis Title(XS)=Station
BEGIN DESCRIPTION:
TRIB 5 TO COLETO CREEK
END DESCRIPTION:
DSS Export Rating Curves= 0
DSS Export Rating Curve Sorted= 0
DSS Export Volume Flow Curves= 0
DXF OffsetX= 0
DXF OffsetY= 0
DXF ScaleX= 1
DXF ScaleY= 10

--- TRIB 5 TO COLETO CREEK.p01 (plan) ---

Plan Title=Multiple Run
Short Identifier=Multiple
Geom File=g01
Flow File=f01
Subcritical Flow
K Sum by GR= 0
Std Step Tol= 0.01
Critical Tol= 0.01
Num of Std Step Trials= 20
Max Error Tol= 0.3
Flow Tol Ratio= 0.001
Split Flow NTrial= 30
Split Flow Tol= 0.02
Split Flow Ratio= 0.02
Log Output Level= 0
Friction Slope Method= 1
Unsteady Friction Slope Method= 2
Unsteady Bridges Friction Slope Method= 1
Parabolic Critical Depth
Global Vel Dist=  1 , 1 , 1
Global Log Level= 0
CheckData=True
Encroach Param= -1, 0, 0, 0
BEGIN DESCRIPTION:
Multiple Run
END DESCRIPTION:

--- TRIB 5 TO COLETO CREEK.f01 (steady flow) ---

Flow Title=Multiple
Number of Profiles=7
Profile Names=10-year,25-year,50-year,1pct_min,100-year,1pct_plu,500-year
River Rch & RM= TRIB 5 TO COLETO,Reach-1,6957
     208     309     392     243     484     966     726
River Rch & RM= TRIB 5 TO COLETO,Reach-1,4844
     670    1077    1443     937    1869    3729    3099
Boundary for River Rch & Prof#=TRIB 5 TO COLETO,Reach-1,1
Up Type=0
Dn Type=3
Dn Slope=0.005
Boundary for River Rch & Prof#=TRIB 5 TO COLETO,Reach-1,2
Up Type=0
Dn Type=3
Dn Slope=0.005
Boundary for River Rch & Prof#=TRIB 5 TO COLETO,Reach-1,3
Up Type=0
Dn Type=3
Dn Slope=0.005
Boundary for River Rch & Prof#=TRIB 5 TO COLETO,Reach-1,4
Up Type=0
Dn Type=3
Dn Slope=0.005
Boundary for River Rch & Prof#=TRIB 5 TO COLETO,Reach-1,5
Up Type=0
Dn Type=3
Dn Slope=0.005
Boundary for River Rch & Prof#=TRIB 5 TO COLETO,Reach-1,6
Up Type=0
Dn Type=3
Dn Slope=0.005
Boundary for River Rch & Prof#=TRIB 5 TO COLETO,Reach-1,7
Up Type=0
Dn Type=3
Dn Slope=0.005

--- TRIB 5 TO COLETO CREEK.g01 (geometry) ---

Geom Title=Existing Conditions
Program Version=4.10

River Reach=TRIB 5 TO COLETO,Reach-1
Reach XY= 30
        2536625.       13497225.      2536721.66     13497132.89
       2536774.9      13497167.2      2536923.44     13497128.66
      2537151.82      13497301.3      2537407.96     13497608.76
      2537481.66     13497584.31      2537608.35     13497708.32
       2537775.4     13498004.86      2537771.47     13498123.53
      2537625.55     13498314.36      2537783.48     13498522.37
      2537890.25     13498475.41      2538045.21     13498525.21
      2538128.41     13498482.82      2538268.33      13498615.7
       2538324.9     13498582.81      2538469.11     13498623.03
      2538626.65     13498478.16        2538725.     13498517.44
      2538842.22     13498458.52      2538875.27     13498395.23
      2538834.15     13498318.27      2538974.99     13498182.08
       2539385.5      13498473.8      2540035.18     13498424.54
      2540145.03     13498474.93      2540864.57     13498476.05
      2541319.74     13498830.47        2541425.       13499225.

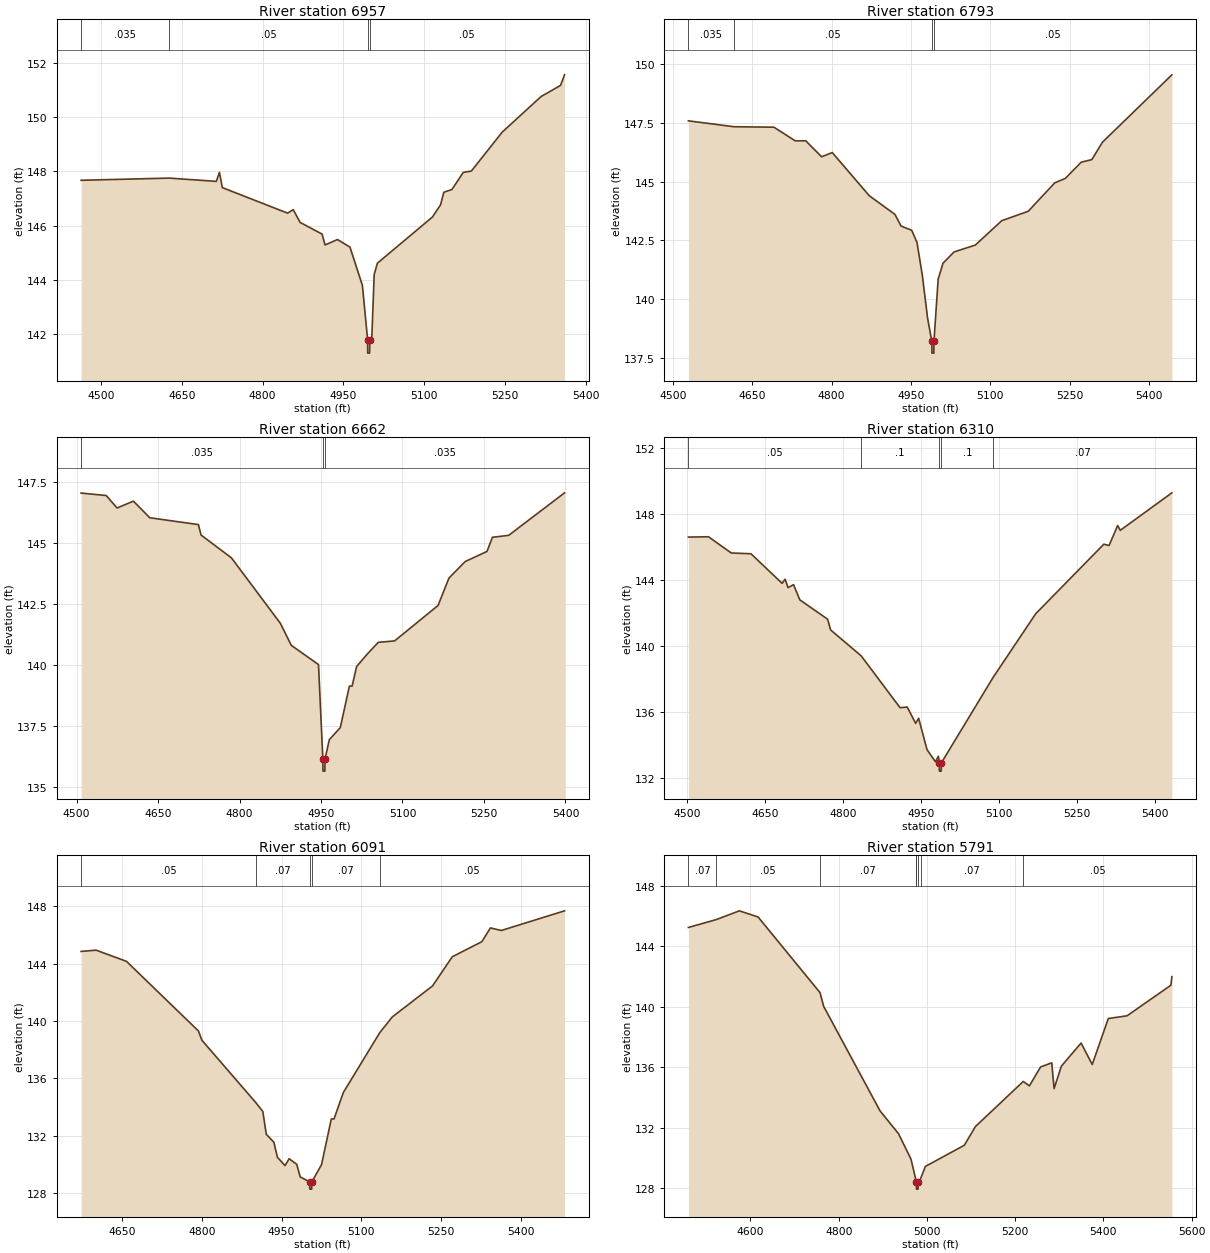
Type RM Length L Ch R = 1 ,6957    ,164,164,164
BEGIN DESCRIPTION:
TRIB 5 TO COLETO CREEK 14.0
END DESCRIPTION:
XS GIS Cut Line= 3
      2536454.24     13497663.55        2536675.       13497175.
      2536474.98     13496874.97
#Sta/Elev= 30
  4463.4  147.67  4626.8  147.75  4714.2  147.63    4720  147.96  4725.4   147.4
  4846.5  146.46  4856.9  146.59  4869.6  146.12  4910.4  145.69  4915.9  145.29
    4939  145.49  4962.1  145.21  4985.2   143.8  4994.8  141.81    4995  141.31
  4998.5  141.31  4998.8  141.81  5002.5  141.81    5007   144.2    5013  144.62
  5115.2  146.32  5130.2  146.77  5136.2  147.23  5151.2  147.33  5172.3  147.96
  5187.3  148.01  5244.4  149.44  5316.5  150.75  5352.6  151.16  5360.1  151.55
#Mann= 4 ,-1 , 0
  4463.4    .035       0  4626.8     .05       0  4994.8     .05       0
  4998.8     .05       0
Bank Sta=4994.8,4998.8
XS Rating Curve= 0 ,0
Exp/Cntr=0.3,0.1

Type RM Length L Ch R = 1 ,6793    ,131,131,131
BEGIN DESCRIPTION:
Mapping XS fd6fb888
END DESCRIPTION:
XS GIS Cut Line= 3
      2536780.19     13497616.43      2536804.63     13497131.64
      2536784.26     13496703.84
#Sta/Elev= 30
  4529.4  147.59  4615.6  147.34    4691  147.32  4731.1  146.74  4751.1  146.74
  4781.2  146.06  4801.2  146.24  4871.3   144.4  4919.6  143.61  4931.3  143.11
  4951.4  142.93  4961.4  142.41  4971.4  141.02  4981.4  139.19  4989.4   138.2
  4989.7   137.7  4993.2   137.7  4993.4   138.2  5001.4  140.85  5010.6  141.53
  5031.5  142.01  5071.5   142.3  5121.6  143.34  5171.6  143.74  5221.7  144.95
  5241.7  145.14  5271.7  145.83  5291.8  145.94  5311.8  146.68  5443.1  149.55
#Mann= 4 ,-1 , 0
  4529.4    .035       0  4615.6     .05       0  4989.4     .05       0
  4993.4     .05       0
Bank Sta=4989.4,4993.4
XS Rating Curve= 0 ,0
Exp/Cntr=0.3,0.1

Type RM Length L Ch R = 1 ,6662    ,352,352,352
BEGIN DESCRIPTION:
Mapping XS 43f9825a
END DESCRIPTION:
XS GIS Cut Line= 3
      2536896.14     13497621.11      2536927.33     13497126.47
      2536920.44     13496732.26
#Sta/Elev= 30
  4508.4  147.03  4554.6  146.93  4574.7  146.42  4604.7   146.7  4634.8  146.02
  4724.3  145.74  4729.3  145.31  4785.1  144.38  4875.2   141.7  4895.3   140.8
  4945.4  140.01  4953.4  136.15  4953.7  135.65  4957.2  135.65  4957.4  136.15
  4965.4  136.94  4985.5  137.43  5002.3  139.13  5007.3  139.13  5015.5  139.93
  5035.5  140.45  5055.5  140.92  5085.5  140.98  5165.5  142.43  5185.5  143.55
  5215.5  144.23  5255.5  144.64  5265.5  145.22  5295.5   145.3  5398.3  147.04
#Mann= 3 ,-1 , 0
  4508.4    .035       0  4953.4    .035       0  4957.4    .035       0
Bank Sta=4953.4,4957.4
XS Rating Curve= 0 ,0
Exp/Cntr=0.3,0.1

Type RM Length L Ch R = 1 ,6310    ,219,219,219
BEGIN DESCRIPTION:
Mapping XS c2e0e467
END DESCRIPTION:
XS GIS Cut Line= 3
      2536951.68     13497773.95       2537183.4     13497343.48
      2537244.16     13496905.15
#Sta/Elev= 30
    4502  146.61  4540.6  146.63  4584.4  145.65  4622.5   145.6  4682.5  143.81
  4688.3  144.06  4693.9  143.55  4704.5  143.73  4716.6  142.81  4770.2  141.64
  4775.9  140.99  4834.8  139.42  4909.7  136.28  4923.5  136.32  4939.8  135.33
  4945.5  135.64  4961.7  133.74  4977.8  133.01  4983.6  133.34  4985.3  132.94
  4985.5  132.44    4989  132.44  4989.3  132.94  5089.1  138.12  5171.1  141.97
  5302.3  146.18  5312.4   146.1  5328.9  147.31    5334  147.02  5433.4  149.29
#Mann= 5 ,-1 , 0
    4502     .05       0  4834.8      .1       0  4985.3     .05       0
  4989.3      .1       0  5089.1     .07       0
Bank Sta=4985.3,4989.3
XS Rating Curve= 0 ,0
Exp/Cntr=0.3,0.1

Type RM Length L Ch R = 1 ,6091    ,300,300,300
BEGIN DESCRIPTION:
Mapping XS ef16451e
END DESCRIPTION:
XS GIS Cut Line= 3
      2537066.21     13497816.57      2537339.65     13497491.05
      2537443.59     13497018.98
#Sta/Elev= 30
  4573.3  144.84  4601.5  144.93  4658.6  144.15  4793.8   139.3  4800.4  138.65
  4901.6  134.31  4914.8  133.69  4921.3   132.1  4935.6  131.55  4942.2   130.5
  4956.5  129.92  4964.2   130.4  4978.5  130.01  4985.1  129.13  5002.9  128.78
  5003.1  128.28  5006.6  128.28  5006.9  128.78  5025.1  129.98  5043.5  133.17
  5048.6  133.17  5066.1  135.01  5134.7  139.19  5158.2  140.28  5233.8  142.44
  5270.8  144.47  5326.4  145.52  5342.5  146.48    5363   146.3  5481.8  147.67
#Mann= 5 ,-1 , 0
  4573.3     .05       0  4901.6     .07       0  5002.9     .05       0
  5006.9     .07       0  5134.7     .05       0
Bank Sta=5002.9,5006.9
XS Rating Curve= 0 ,0
Exp/Cntr=0.3,0.1

Type RM Length L Ch R = 1 ,5791    ,205,205,205
BEGIN DESCRIPTION:
Mapping XS 5308dd4b
END DESCRIPTION:
XS GIS Cut Line= 3
      2537135.69     13497998.83      2537530.62     13497634.28
      2537721.43     13497109.56
#Sta/Elev= 30
  4459.4  145.24  4522.4  145.76  4574.9  146.34  4617.4  145.93  4757.7  140.93
    4766  140.02  4893.6  133.12  4935.5  131.61  4963.9  129.92  4974.4  128.62
  4976.1  128.44  4976.3  127.94  4979.8  127.94  4980.1  128.44  4985.5  128.62
  4996.4  129.44  5084.7  130.84    5110  132.08  5218.3  135.06  5232.3  134.77
  5257.6  136.02  5282.9  136.29  5288.2  134.59  5304.7  136.07  5349.4   137.6
  5374.6  136.18  5411.1  139.22  5453.6   139.4  5552.9  141.42  5555.2  141.99
#Mann= 8 ,-1 , 0
  4459.4     .07       0  4522.4     .05       0  4757.7     .07       0
  4974.4     .05       0  4976.1     .05       0  4980.1     .05       0
  4985.5     .07       0  5218.3     .05       0
Bank Sta=4976.1,4980.1
XS Rating Curve= 0 ,0
Exp/Cntr=0.3,0.1

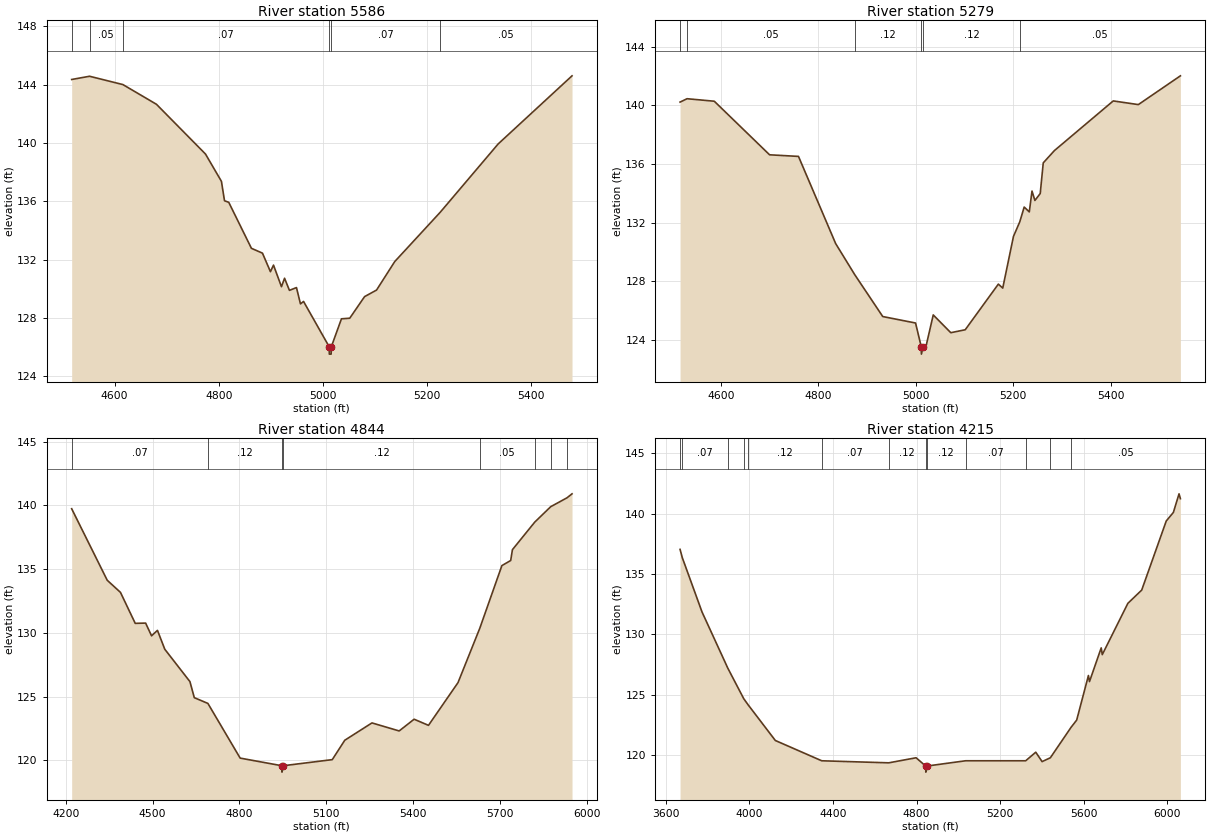
Type RM Length L Ch R = 1 ,5586    ,307,307,307
BEGIN DESCRIPTION:
Mapping XS 542434e5
END DESCRIPTION:
XS GIS Cut Line= 3
      2537239.82     13498055.29      2537639.13     13497803.55
      2537881.68      13497379.1
#Sta/Elev= 30
  4517.5  144.35  4551.8  144.57  4615.9     144  4680.3  142.65  4774.5  139.24
  4805.1  137.37    4811  136.04  4819.2  135.93  4862.7  132.78  4883.9  132.45
  4899.2  131.18  4905.1  131.63  4920.4  130.15  4926.3  130.73  4935.7   129.9
  4949.2  130.09  4956.9  128.97  4962.8  129.14  5012.1  126.03  5012.3  125.53
  5015.8  125.53  5016.1  126.03  5035.6  127.95  5051.5  127.99    5080  129.47
    5103  129.92  5137.9  131.87  5225.5  135.26  5336.5  139.93  5478.4   144.6
#Mann= 6 ,-1 , 0
  4517.5     .07       0  4551.8     .05       0  4615.9     .07       0
  5012.1     .05       0  5016.1     .07       0  5225.5     .05       0
Bank Sta=5012.1,5016.1
XS Rating Curve= 0 ,0
Exp/Cntr=0.3,0.1

Type RM Length L Ch R = 1 ,5279    ,435,435,435
BEGIN DESCRIPTION:
Mapping XS 8863ef67
END DESCRIPTION:
XS GIS Cut Line= 4
      2537300.56      13498142.1      2537769.34     13498059.63
       2537808.4     13498029.24      2538016.75     13497573.48
#Sta/Elev= 30
  4516.3  140.22  4530.7  140.45  4586.5  140.28    4700  136.63  4759.3  136.52
  4835.6  130.58  4874.6  128.47  4932.2  125.61  4999.5  125.17  5011.2  123.55
  5011.5  123.05  5015.2  123.55  5021.4  123.65  5035.8  125.72  5071.8  124.51
  5101.4  124.71  5169.4  127.82  5178.4  127.55  5200.4  131.07  5213.3  132.06
  5222.4  133.07  5232.9  132.74  5238.4  134.16  5244.4  133.52  5255.3  133.99
  5261.5  136.08  5284.5  136.92  5405.1   140.3  5456.6  140.05  5542.9  142.01
#Mann= 6 ,-1 , 0
  4516.3     .07       0  4530.7     .05       0  4874.6     .12       0
  5011.2     .05       0  5015.2     .12       0  5213.3     .05       0
Bank Sta=5011.2,5015.2
XS Rating Curve= 0 ,0
Exp/Cntr=0.3,0.1

Type RM Length L Ch R = 1 ,4844    ,629,629,629
BEGIN DESCRIPTION:
Mapping XS 7d0ced55
END DESCRIPTION:
XS GIS Cut Line= 4
      2536944.68     13498307.02      2537617.43     13498441.57
      2537799.72     13498354.76      2538251.12     13497647.28
#Sta/Elev= 30
  4220.8  139.73  4343.5  134.12  4389.2  133.17  4440.2  130.74  4476.1  130.76
  4496.5  129.76  4516.9  130.19  4542.2  128.71    4629  126.17  4644.1  124.91
    4691  124.46  4802.4  120.17  4946.5  119.57  4946.7  119.07  4950.5  119.57
  5120.4  120.05  5163.5  121.57  5257.4  122.93  5351.3   122.3  5402.9  123.22
  5452.5  122.74  5554.4  126.09  5629.7  130.36  5705.9  135.27  5736.3  135.67
  5742.3  136.52  5819.3  138.68  5874.4  139.89  5930.8  140.59    5948   140.9
#Mann= 8 ,-1 , 0
  4220.8     .07       0    4691     .12       0  4946.5     .05       0
  4950.5     .12       0  5629.7     .05       0  5819.3     .12       0
  5874.4     .05       0  5930.8     .12       0
Bank Sta=4946.5,4950.5
XS Rating Curve= 0 ,0
Exp/Cntr=0.3,0.1

Type RM Length L Ch R = 1 ,4215    ,0,0,0
BEGIN DESCRIPTION:
Mapping XS 9002daca
END DESCRIPTION:
XS GIS Cut Line= 4
      2536901.32     13498467.62       2538012.4     13498645.56
      2538298.85     13498476.29      2538450.76     13497551.86
#Sta/Elev= 30
  3667.9  137.05  3678.9  136.35  3772.9  131.87  3896.8   127.2  3972.8  124.68
  3995.2  124.14    4124  121.22  4345.9  119.54  4666.9  119.37  4797.6  119.79
  4843.9   119.1  4844.2   118.6  4847.9   119.1  5034.5  119.54  5322.3  119.54
  5370.4  120.25  5400.8  119.47  5440.3  119.79  5539.8  122.32  5566.3  122.91
  5622.5   126.6  5627.6   126.1  5683.7  128.89  5688.8  128.33  5811.3  132.58
  5877.6  133.68    5995   139.4  6029.1  140.11  6056.2  141.65  6062.7  141.25
#Mann= 13 ,-1 , 0
  3667.9    .035       0  3678.9     .07       0  3896.8     .12       0
  3972.8     .07       0  3995.2     .12       0  4345.9     .07       0
  4666.9     .12       0  4843.9     .05       0  4847.9     .12       0
  5034.5     .07       0  5322.3      .1       0  5440.3     .12       0
  5539.8     .05       0
Bank Sta=4843.9,4847.9
XS Rating Curve= 0 ,0
Exp/Cntr=0.3,0.1

Chan Stop Cuts=-1
Use User Specified Reach Order=0
Composite Channel Slope=5