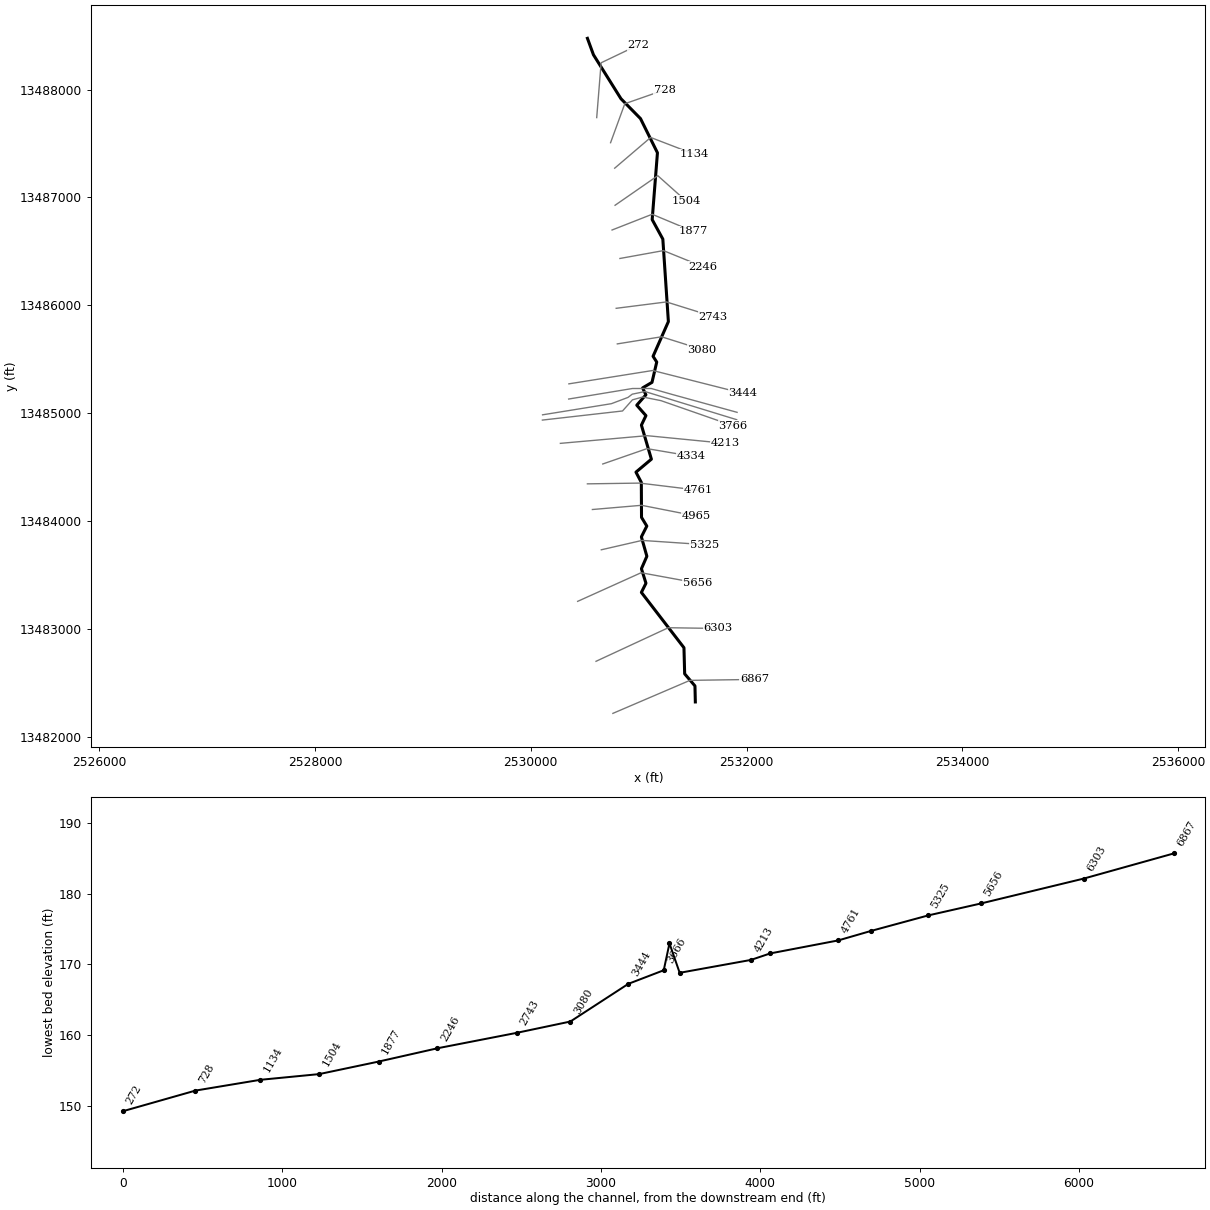
--- TRIB 5 TO HOG THIEF CREEK.prj (project) ---

Proj Title=TRIB 5 TO HOG THIEF CREEK Base Level Engineering
Current Plan=p01
Default Exp/Contr=0.3,0.1
English Units
Geom File=g01
Flow File=f01
Plan File=p01
Y Axis Title=Elevation
X Axis Title(PF)=Main Channel Distance
X Axis Title(XS)=Station
BEGIN DESCRIPTION:
TRIB 5 TO HOG THIEF CREEK
END DESCRIPTION:
DSS Export Rating Curves= 0
DSS Export Rating Curve Sorted= 0
DSS Export Volume Flow Curves= 0
DXF OffsetX= 0
DXF OffsetY= 0
DXF ScaleX= 1
DXF ScaleY= 10

--- TRIB 5 TO HOG THIEF CREEK.p01 (plan) ---

Plan Title=Multiple Run
Short Identifier=Multiple
Geom File=g01
Flow File=f01
Subcritical Flow
K Sum by GR= 0
Std Step Tol= 0.01
Critical Tol= 0.01
Num of Std Step Trials= 20
Max Error Tol= 0.3
Flow Tol Ratio= 0.001
Split Flow NTrial= 30
Split Flow Tol= 0.02
Split Flow Ratio= 0.02
Log Output Level= 0
Friction Slope Method= 1
Unsteady Friction Slope Method= 2
Unsteady Bridges Friction Slope Method= 1
Parabolic Critical Depth
Global Vel Dist=  1 , 1 , 1
Global Log Level= 0
CheckData=True
Encroach Param= -1, 0, 0, 0
BEGIN DESCRIPTION:
Multiple Run
END DESCRIPTION:

--- TRIB 5 TO HOG THIEF CREEK.f01 (steady flow) ---

Flow Title=Multiple
Number of Profiles=7
Profile Names=10-year,25-year,50-year,1pct_min,100-year,1pct_plu,500-year
River Rch & RM= TRIB 5 TO HOG TH,Reach-1,6867
     202     294     370     225     450     898     657
River Rch & RM= TRIB 5 TO HOG TH,Reach-1,4965
     385     589     763     480     957    1910    1485
Boundary for River Rch & Prof#=TRIB 5 TO HOG TH,Reach-1,1
Up Type=0
Dn Type=3
Dn Slope=0.005
Boundary for River Rch & Prof#=TRIB 5 TO HOG TH,Reach-1,2
Up Type=0
Dn Type=3
Dn Slope=0.005
Boundary for River Rch & Prof#=TRIB 5 TO HOG TH,Reach-1,3
Up Type=0
Dn Type=3
Dn Slope=0.005
Boundary for River Rch & Prof#=TRIB 5 TO HOG TH,Reach-1,4
Up Type=0
Dn Type=3
Dn Slope=0.005
Boundary for River Rch & Prof#=TRIB 5 TO HOG TH,Reach-1,5
Up Type=0
Dn Type=3
Dn Slope=0.005
Boundary for River Rch & Prof#=TRIB 5 TO HOG TH,Reach-1,6
Up Type=0
Dn Type=3
Dn Slope=0.005
Boundary for River Rch & Prof#=TRIB 5 TO HOG TH,Reach-1,7
Up Type=0
Dn Type=3
Dn Slope=0.005

--- TRIB 5 TO HOG THIEF CREEK.g01 (geometry) ---

Geom Title=Existing Conditions
Program Version=4.10

River Reach=TRIB 5 TO HOG TH,Reach-1
Reach XY= 30
        2531525.       13482325.      2531521.49     13482473.55
      2531426.06     13482585.44      2531419.54     13482827.45
      2531024.97     13483340.24       2531067.4     13483424.99
      2531025.39     13483559.72      2531075.82       13483675.
      2531024.92     13483854.91      2531075.28     13483954.82
      2531026.24      13484035.5      2531024.46      13484359.8
      2530974.69     13484454.66      2531117.69     13484574.89
      2531025.15     13484890.42      2531067.15     13484978.41
      2530982.12       13485075.      2531066.96     13485171.68
      2531036.17     13485235.29      2531123.32     13485286.83
       2531167.2      13485475.1      2531133.24     13485528.23
       2531275.2     13485849.92       2531223.8      13486614.5
      2531125.06     13486795.03       2531173.8      13487414.5
      2531016.86     13487731.06      2530835.76     13487915.32
      2530580.83      13488322.7        2530525.       13488475.

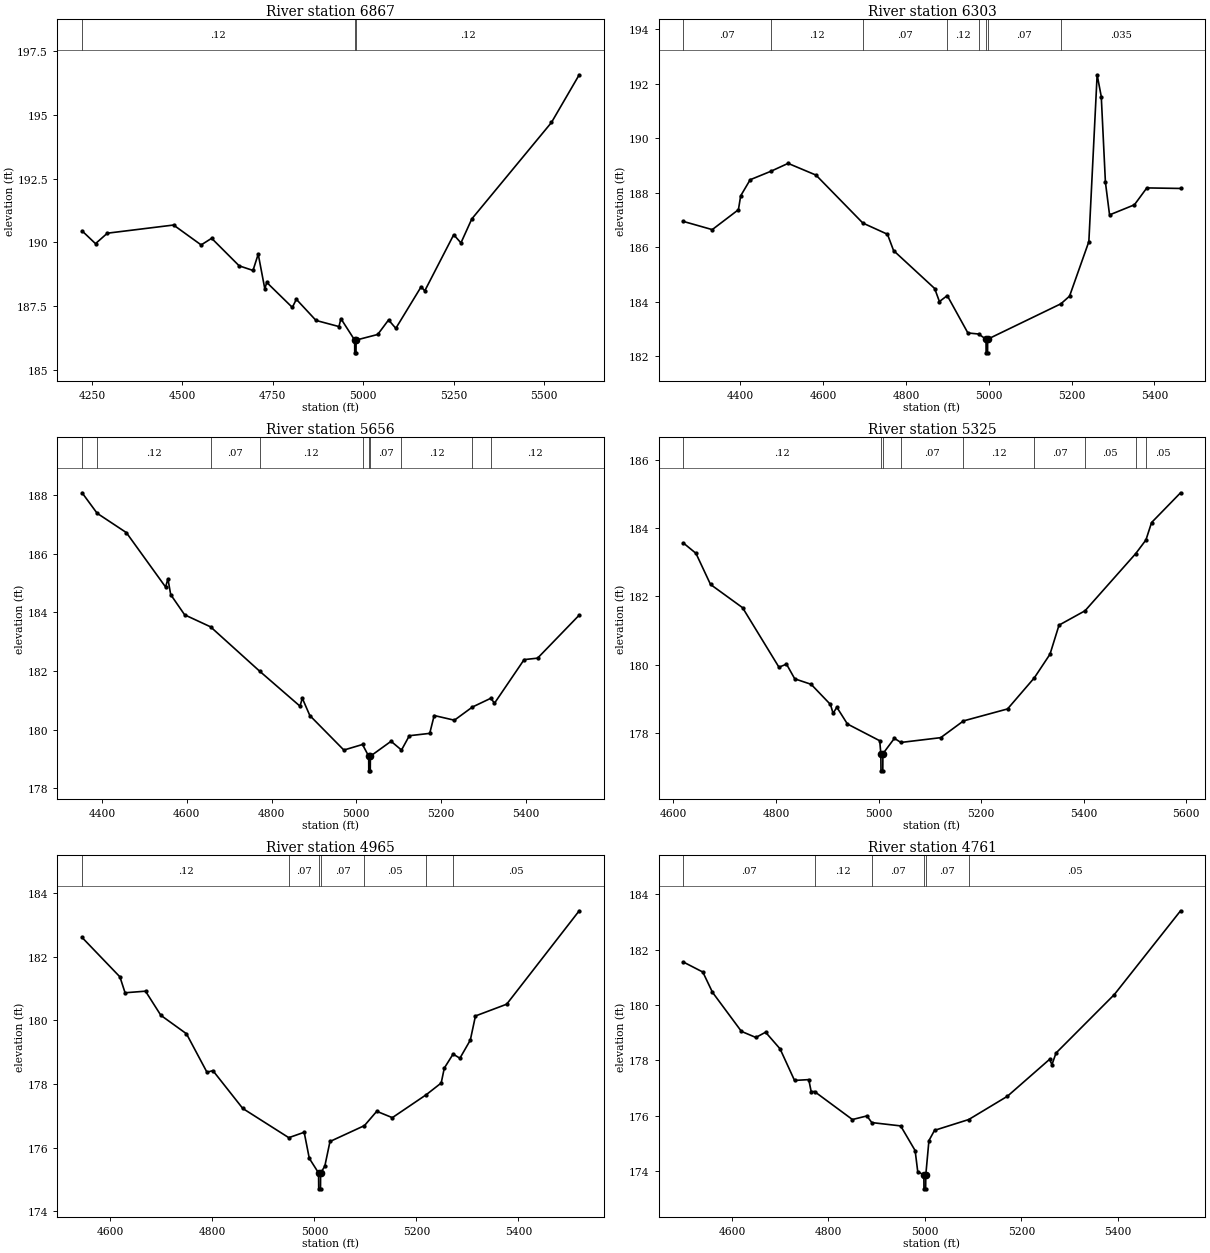
Type RM Length L Ch R = 1 ,6867    ,564,564,564
BEGIN DESCRIPTION:
TRIB 5 TO HOG THIEF CREEK 15.0
END DESCRIPTION:
XS GIS Cut Line= 3
      2530760.86     13482219.07        2531475.       13482525.
      2532071.73      13482533.7
#Sta/Elev= 30
  4223.1  190.45  4260.2  189.95  4292.9  190.36  4475.9  190.68  4552.1   189.9
  4581.1  190.16  4657.2  189.08  4695.4   188.9  4709.8  189.54    4728  188.18
  4733.4  188.43  4804.1  187.45  4815.1  187.77  4869.5  186.94  4932.9   186.7
  4938.3  187.01  4976.3  186.17  4976.5  185.67    4980  185.67  4980.3  186.17
    5040  186.39    5070  186.96    5090  186.63    5160  188.26    5170   188.1
    5250   190.3    5270  189.98    5300  190.92  5520.1   194.7  5596.8  196.57
#Mann= 3 ,-1 , 0
  4223.1     .12       0  4976.3     .05       0  4980.3     .12       0
Bank Sta=4976.3,4980.3
XS Rating Curve= 0 ,0
Exp/Cntr=0.3,0.1

Type RM Length L Ch R = 1 ,6303    ,647,647,647
BEGIN DESCRIPTION:
Mapping XS f6cea400
END DESCRIPTION:
XS GIS Cut Line= 3
       2530604.6      13482701.7      2531274.76     13483012.89
      2531736.52     13483005.95
#Sta/Elev= 30
  4262.4  186.94    4332  186.64  4395.2  187.37  4400.7  187.88  4423.6  188.47
  4473.6  188.78  4515.2  189.07  4582.6  188.64  4695.8  186.88  4755.2  186.47
    4770  185.87  4869.2  184.48  4880.7     184  4899.6  184.22  4949.4  182.85
  4975.4  182.81  4993.2  182.62  4993.5  182.12    4997  182.12  4997.2  182.62
  5174.2  183.92    5195   184.2  5241.6   186.2  5261.6  192.32  5271.6  191.52
  5281.6  188.38  5291.6  187.18  5351.6  187.55  5381.6  188.17  5463.1  188.15
#Mann= 8 ,-1 , 0
  4262.4     .07       0  4473.6     .12       0  4695.8     .07       0
  4899.6     .12       0  4975.4     .07       0  4993.2     .05       0
  4997.2     .07       0  5174.2    .035       0
Bank Sta=4993.2,4997.2
XS Rating Curve= 0 ,0
Exp/Cntr=0.3,0.1

Type RM Length L Ch R = 1 ,5656    ,331,331,331
BEGIN DESCRIPTION:
Mapping XS 87a5d2b5
END DESCRIPTION:
XS GIS Cut Line= 3
      2530434.41     13483257.24      2531022.44     13483522.44
      2531541.62     13483427.26
#Sta/Elev= 30
  4353.1  188.09  4388.6  187.39  4457.5  186.73  4550.1  184.87  4555.6  185.15
  4562.2  184.61  4595.1  183.92  4656.2  183.51  4772.4  181.99  4867.2   180.8
  4872.7  181.07  4890.4  180.48  4970.7   179.3  5014.7  179.49  5029.3  179.09
  5029.5  178.59    5033  178.59  5033.3  179.09  5082.1   179.6  5106.7   179.3
  5125.2  179.79  5173.3  179.87  5183.8  180.48  5231.5  180.32    5274  180.77
  5317.5  181.07  5326.1   180.9    5396  182.39  5427.8  182.44    5526  183.91
#Mann= 10 ,-1 , 0
  4353.1     .07       0  4388.6     .12       0  4656.2     .07       0
  4772.4     .12       0  5014.7     .07       0  5029.3     .05       0
  5033.3     .07       0  5106.7     .12       0    5274     .07       0
  5317.5     .12       0
Bank Sta=5029.3,5033.3
XS Rating Curve= 0 ,0
Exp/Cntr=0.3,0.1

Type RM Length L Ch R = 1 ,5325    ,360,360,360
BEGIN DESCRIPTION:
Mapping XS db91d7b0
END DESCRIPTION:
XS GIS Cut Line= 3
      2530653.56     13483735.12      2531031.12     13483821.92
      2531611.41     13483782.94
#Sta/Elev= 30
  4619.7  183.56  4644.1  183.26  4672.5  182.35    4735  181.67  4805.9  179.93
  4820.6  180.02  4836.7  179.59  4868.6  179.43  4906.3  178.84  4911.4  178.58
  4918.7  178.76  4939.3  178.27  5002.3  177.78  5004.5   177.4  5004.8   176.9
  5008.3   176.9  5008.5   177.4  5030.9  177.85  5043.6  177.73  5121.2  177.87
  5165.6  178.36  5251.5  178.71  5303.7  179.62  5334.2  180.31  5351.8  181.16
  5402.5  181.58  5501.2  183.25  5521.2  183.65  5532.2  184.16  5588.7  185.03
#Mann= 9 ,-1 , 0
  4619.7     .12       0  5004.5     .05       0  5008.5     .12       0
  5043.6     .07       0  5165.6     .12       0  5303.7     .07       0
  5402.5     .05       0  5501.2     .07       0  5521.2     .05       0
Bank Sta=5004.5,5008.5
XS Rating Curve= 0 ,0
Exp/Cntr=0.3,0.1

Type RM Length L Ch R = 1 ,4965    ,204,204,204
BEGIN DESCRIPTION:
Mapping XS 5a8f669b
END DESCRIPTION:
XS GIS Cut Line= 3
      2530571.03     13484108.37      2531026.78     13484147.44
      2531534.64      13484047.6
#Sta/Elev= 30
  4544.4  182.61  4618.6  181.37  4628.7  180.87  4668.8  180.92  4698.9  180.16
  4749.1  179.58  4789.3  178.37    4801  178.42  4859.5  177.23  4949.8  176.31
    4980  176.48    4990  175.66  5008.2   175.2  5008.5   174.7    5012   174.7
  5012.2   175.2  5020.4  175.41  5030.6  176.19  5098.2  176.69  5122.3  177.14
  5152.9  176.94  5219.2  177.66  5248.7  178.03  5254.8   178.5    5272  178.94
  5285.4  178.81  5305.8  179.38  5315.9  180.14  5377.1  180.51  5519.4  183.45
#Mann= 7 ,-1 , 0
  4544.4     .12       0  4949.8     .07       0  5008.2     .05       0
  5012.2     .07       0  5098.2     .05       0  5219.2     .12       0
    5272     .05       0
Bank Sta=5008.2,5012.2
XS Rating Curve= 0 ,0
Exp/Cntr=0.3,0.1

Type RM Length L Ch R = 1 ,4761    ,427,427,427
BEGIN DESCRIPTION:
Mapping XS 3e6e190b
END DESCRIPTION:
XS GIS Cut Line= 3
      2530524.77     13484346.22      2531010.87     13484353.17
      2531551.22     13484287.36
#Sta/Elev= 30
  4499.5  181.55  4539.7  181.19  4559.7  180.46  4619.7  179.05  4649.7  178.83
  4669.8  179.02  4699.8  178.42  4729.8  177.28  4759.3  177.31  4764.3  176.88
  4771.2  176.88  4849.8  175.87  4879.8     176    4890  175.76  4949.8  175.64
  4979.8  174.75  4985.2  173.99  4997.9  173.87  4998.1  173.37  5001.6  173.37
  5001.9  173.87  5008.4  175.11    5020  175.48  5090.9  175.87  5171.1  176.71
  5258.4  178.04  5263.4  177.85  5271.9  178.27  5392.8  180.38    5530   183.4
#Mann= 6 ,-1 , 0
  4499.5     .07       0  4771.2     .12       0    4890     .07       0
  4997.9     .05       0  5001.9     .07       0  5090.9     .05       0
Bank Sta=4997.9,5001.9
XS Rating Curve= 0 ,0
Exp/Cntr=0.3,0.1

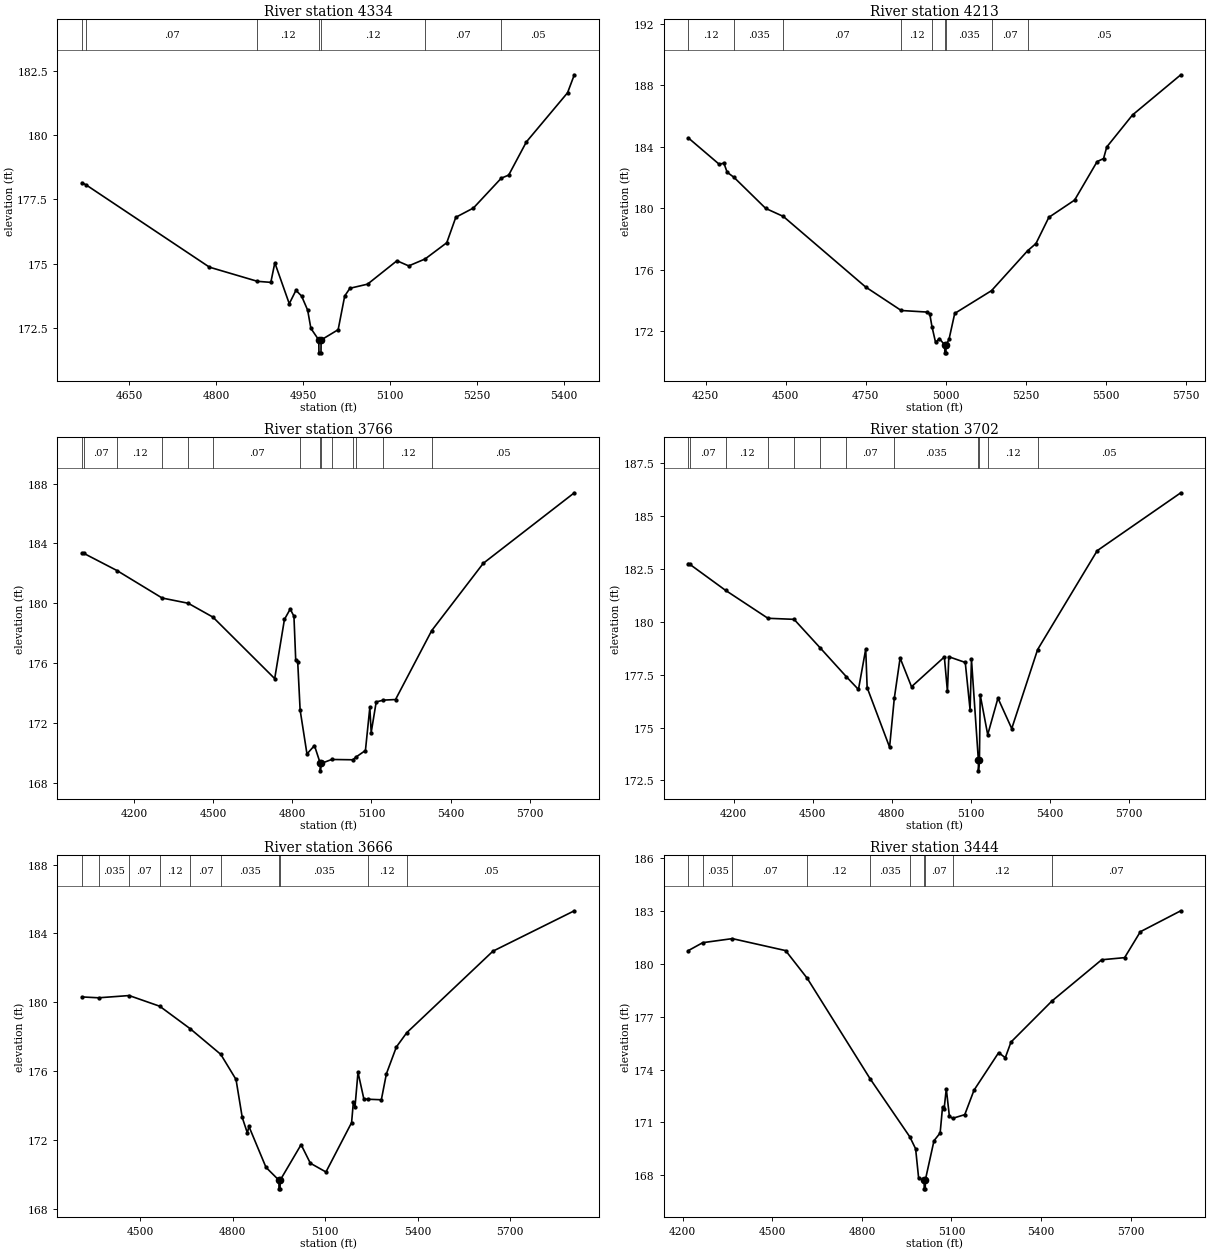
Type RM Length L Ch R = 1 ,4334    ,121,121,121
BEGIN DESCRIPTION:
Mapping XS 53cb3175
END DESCRIPTION:
XS GIS Cut Line= 3
      2530667.13     13484530.25      2531076.84     13484672.61
      2531486.56     13484603.17
#Sta/Elev= 30
  4568.6  178.14  4575.2  178.07  4788.7  174.86  4871.4  174.31  4894.5  174.27
  4901.4  175.03  4926.3  173.44  4937.8  173.96  4947.5  173.74    4958  173.19
  4963.6  172.48  4977.2  172.03  4977.5  171.53    4981  171.53  4981.2  172.03
  5010.6  172.43  5021.9  173.74  5030.9  174.04  5061.3   174.2    5112  175.11
  5132.3  174.91  5160.6  175.18  5197.9  175.81  5213.5   176.8  5243.9  177.16
  5291.9  178.32  5304.7  178.44  5335.2  179.73  5406.2  181.64  5417.9  182.34
#Mann= 7 ,-1 , 0
  4568.6     .12       0  4575.2     .07       0  4871.4     .12       0
  4977.2     .05       0  4981.2     .12       0  5160.6     .07       0
  5291.9     .05       0
Bank Sta=4977.2,4981.2
XS Rating Curve= 0 ,0
Exp/Cntr=0.3,0.1

Type RM Length L Ch R = 1 ,4213    ,447,447,447
BEGIN DESCRIPTION:
Mapping XS a207561a
END DESCRIPTION:
XS GIS Cut Line= 3
      2530274.31     13484721.47      2531077.17     13484792.75
      2531804.97     13484721.47
#Sta/Elev= 30
  4195.8  184.57  4292.1  182.86  4306.9  182.93    4317  182.34  4338.3  182.01
  4437.4  179.99  4492.3  179.47  4749.1  174.89  4860.4  173.36  4939.4  173.26
  4949.4  173.15  4956.3  172.32  4967.6  171.29  4979.6  171.54  4996.2  171.11
  4996.5  170.61    5000  170.61  5000.2  171.11  5009.7   171.5  5027.4  173.17
  5142.3  174.65  5254.9  177.24    5281  177.71  5321.2  179.41  5401.6  180.53
  5471.9  183.03    5492  183.23    5502  183.98  5582.4  186.06  5733.1  188.67
#Mann= 9 ,-1 , 0
  4195.8     .12       0  4338.3    .035       0  4492.3     .07       0
  4860.4     .12       0  4956.3    .035       0  4996.2     .05       0
  5000.2    .035       0  5142.3     .07       0  5254.9     .05       0
Bank Sta=4996.2,5000.2
XS Rating Curve= 0 ,0
Exp/Cntr=0.3,0.1

Type RM Length L Ch R = 1 ,3766    ,64,64,64
BEGIN DESCRIPTION:
Mapping XS 6d2978aa
END DESCRIPTION:
XS GIS Cut Line= 6
      2530107.44     13484937.19      2530850.21     13485021.59
      2530942.12     13485124.76      2531037.78     13485151.02
       2531206.6     13485117.26      2531874.42     13484884.65
#Sta/Elev= 30
  4003.2  183.35  4011.4  183.33    4136  182.19  4307.3  180.35  4405.9     180
  4499.8  179.07  4733.5  174.96  4770.4  178.92  4792.2  179.61  4806.4  179.13
  4813.1  176.21  4820.6   176.1  4829.8  172.86  4855.7  169.92  4884.1  170.48
  4906.1  169.29  4906.3  168.79  4910.1  169.29  4949.5  169.55  5029.1  169.53
  5042.8  169.73  5077.1  170.15  5093.8  173.03  5098.9  171.35  5117.9   173.4
  5145.2  173.52  5191.1  173.56  5328.1  178.17  5523.3  182.67  5868.2  187.39
#Mann= 14 ,-1 , 0
  4003.2     .05       0  4011.4     .07       0    4136     .12       0
  4307.3     .07       0  4405.9    .035       0  4499.8     .07       0
  4829.8     .12       0  4906.1    .035       0  4910.1     .12       0
  4949.5    .035       0  5029.1     .12       0  5042.8    .035       0
  5145.2     .12       0  5328.1     .05       0
Bank Sta=4906.1,4910.1
XS Rating Curve= 0 ,0
Exp/Cntr=0.3,0.1

Type RM Length L Ch R = 1 ,3702    ,36,36,36
BEGIN DESCRIPTION:
Mapping XS 4ad19fe3
END DESCRIPTION:
XS GIS Cut Line= 6
      2530109.24     13484985.95      2530747.04     13485089.12
      2530900.85     13485147.27      2530940.24     13485177.28
      2531058.42     13485201.67      2531908.09     13484940.95
#Sta/Elev= 30
  4027.8  182.76  4032.9  182.73  4169.5  181.49  4330.2  180.17  4429.4  180.12
  4528.5  178.77  4627.6  177.41  4673.9   176.8  4701.5  178.71  4706.9  176.89
  4792.1  174.07    4810  176.38  4832.1  178.29  4875.4  176.93  5000.1  178.34
  5011.8  176.71  5017.1  178.35  5079.5  178.08  5097.8  175.84  5103.1  178.22
  5129.3  173.45  5129.5  172.95  5133.3  173.45  5136.3  176.54  5164.8  174.66
  5203.6  176.39    5256  174.95  5354.3  178.69  5580.6  183.37    5898  186.11
#Mann= 12 ,-1 , 0
  4027.8     .05       0  4032.9     .07       0  4169.5     .12       0
  4330.2    .035       0  4429.4     .07       0  4528.5     .12       0
  4627.6     .07       0    4810    .035       0  5129.3    .035       0
  5133.3    .035       0  5164.8     .12       0  5354.3     .05       0
Bank Sta=5129.3,5133.3
XS Rating Curve= 0 ,0
Exp/Cntr=0.3,0.1

Type RM Length L Ch R = 1 ,3666    ,222,222,222
BEGIN DESCRIPTION:
Mapping XS 04a19775
END DESCRIPTION:
XS GIS Cut Line= 5
      2530351.21     13485132.26      2530942.12      13485229.8
      2531116.57      13485229.8      2531307.89     13485175.41
      2531911.92     13485008.97
#Sta/Elev= 30
  4309.8  180.31  4364.1  180.26  4463.3  180.39  4562.5  179.77  4661.6  178.46
  4760.8  176.97  4810.3  175.51  4830.5   173.3  4847.1   172.4  4852.2  172.78
  4907.6   170.4  4949.6  169.65  4949.8  169.15  4953.3  169.15  4953.6  169.65
  5021.6  171.72  5051.6  170.64  5102.3  170.13  5185.5     173  5191.4  174.22
  5196.6  173.92  5206.3  175.93  5225.3  174.38  5239.1  174.36  5282.1  174.33
  5298.5  175.84  5330.9   177.4  5364.6  178.23  5644.3  182.97  5908.6  185.32
#Mann= 10 ,-1 , 0
  4309.8     .07       0  4364.1    .035       0  4463.3     .07       0
  4562.5     .12       0  4661.6     .07       0  4760.8    .035       0
  4949.6    .035       0  4953.6    .035       0  5239.1     .12       0
  5364.6     .05       0
Bank Sta=4949.6,4953.6
XS Rating Curve= 0 ,0
Exp/Cntr=0.3,0.1

Type RM Length L Ch R = 1 ,3444    ,364,364,364
BEGIN DESCRIPTION:
Mapping XS 9be74c98
END DESCRIPTION:
XS GIS Cut Line= 3
      2530353.17     13485272.95       2531129.7     13485396.75
      2531966.33     13485184.77
#Sta/Elev= 30
  4218.6  180.75  4266.9   181.2    4366  181.43  4544.5  180.75  4616.8  179.18
  4827.7  173.47  4960.5  170.18  4979.9   169.5  4990.1  167.82  5008.4  167.73
  5008.7  167.23  5012.2  167.23  5012.4  167.73  5041.4  169.96    5062   170.4
  5070.1  171.88  5075.3  171.76  5082.6  172.91  5092.9  171.36  5103.6  171.23
  5144.5  171.44  5175.5  172.83    5258  174.96  5280.2  174.67  5299.3  175.56
  5436.5  177.89    5603  180.23  5679.8  180.35  5732.5  181.82    5868  183.01
#Mann= 10 ,-1 , 0
  4218.6     .07       0  4266.9    .035       0    4366     .07       0
  4616.8     .12       0  4827.7    .035       0  4960.5     .07       0
  5008.4     .05       0  5012.4     .07       0  5103.6     .12       0
  5436.5     .07       0
Bank Sta=5008.4,5012.4
XS Rating Curve= 0 ,0
Exp/Cntr=0.3,0.1

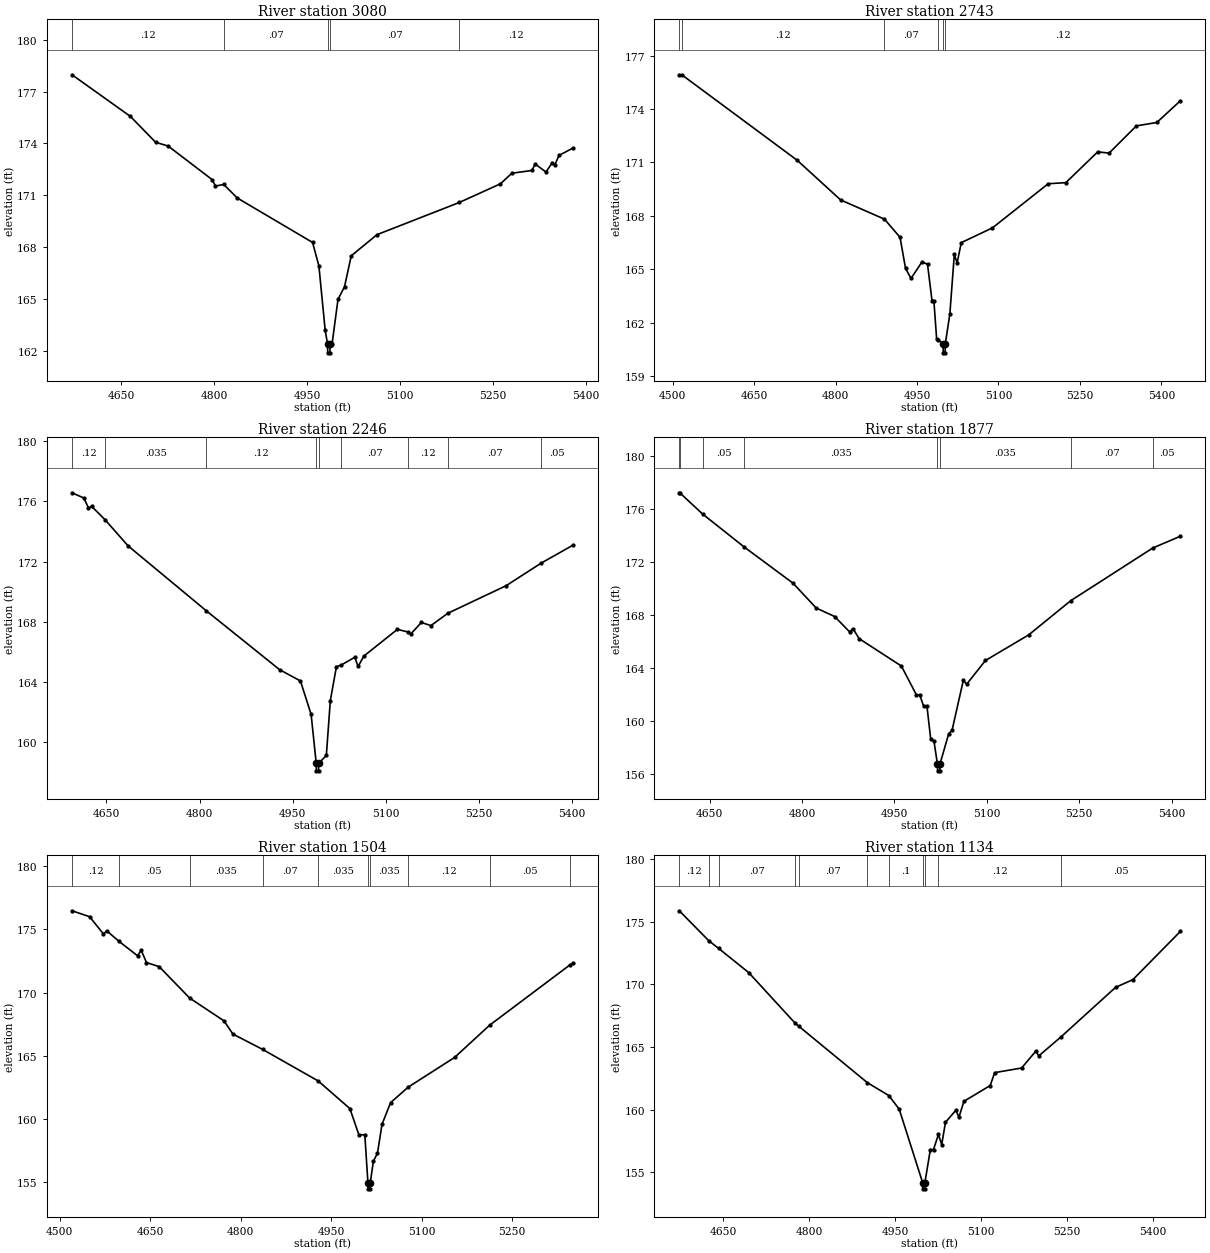
Type RM Length L Ch R = 1 ,3080    ,337,337,337
BEGIN DESCRIPTION:
Mapping XS b09bbc7e
END DESCRIPTION:
XS GIS Cut Line= 3
      2530801.91      13485643.2      2531211.68     13485709.18
      2531586.69     13485591.12
#Sta/Elev= 30
  4570.9  177.97  4665.2  175.56  4705.7  174.07    4726  173.85  4796.9  171.91
  4802.2  171.54  4815.6  171.63  4837.4  170.85  4958.9  168.28  4969.1  166.92
  4979.2  163.22  4983.1   162.4  4983.3   161.9  4986.8   161.9  4987.1   162.4
  4990.3   162.4  4999.9  164.99  5010.4  165.72  5021.3  167.51  5062.8  168.73
  5195.6  170.59    5262  171.67  5280.3  172.28  5312.7  172.44    5318  172.81
  5335.4  172.35  5345.1  172.87  5349.5  172.75  5356.4  173.31  5379.1  173.74
#Mann= 5 ,-1 , 0
  4570.9     .12       0  4815.6     .07       0  4983.1     .05       0
  4987.1     .07       0  5195.6     .12       0
Bank Sta=4983.1,4987.1
XS Rating Curve= 0 ,0
Exp/Cntr=0.3,0.1

Type RM Length L Ch R = 1 ,2743    ,497,497,497
BEGIN DESCRIPTION:
Mapping XS 8195530b
END DESCRIPTION:
XS GIS Cut Line= 3
      2530791.52     13485973.06      2531256.82      13486032.1
      2531690.38     13485896.82
#Sta/Elev= 30
  4511.9  175.92  4516.9  175.91    4729  171.12  4809.1  168.89  4889.9  167.81
  4918.6  166.79  4928.7  165.05  4938.8  164.48  4958.9   165.4  4969.2  165.28
  4977.5  163.24  4980.9  163.24  4986.1  161.06    4989  161.04    4998   160.8
  4998.2   160.3  5001.7   160.3    5002   160.8  5010.4  162.49  5018.6  165.83
  5023.8  165.35  5031.4  166.49  5088.9  167.32  5191.6   169.8  5224.1  169.86
  5282.8  171.59  5303.8  171.52  5354.1  173.05  5391.8  173.24  5435.1  174.46
#Mann= 6 ,-1 , 0
  4511.9     .07       0  4516.9     .12       0  4889.9     .07       0
    4989     .12       0    4998     .05       0    5002     .12       0
Bank Sta=4998,5002
XS Rating Curve= 0 ,0
Exp/Cntr=0.3,0.1

Type RM Length L Ch R = 1 ,2246    ,369,369,369
BEGIN DESCRIPTION:
Mapping XS 97ea427d
END DESCRIPTION:
XS GIS Cut Line= 3
      2530826.23     13486434.87      2531229.04     13486507.79
      2531597.14     13486358.47
#Sta/Elev= 30
  4594.7  176.56  4613.8  176.21  4621.2  175.55  4626.3  175.66  4647.9  174.77
  4684.9  173.04  4810.4  168.75  4928.8  164.83  4962.4  164.08  4979.6  161.86
  4987.8  158.62    4988  158.12  4991.5  158.12  4991.8  158.62  5004.1  159.14
  5010.5  162.78  5020.3  165.02  5028.2  165.14  5049.8  165.65  5055.2  165.04
  5064.5  165.73  5118.4   167.5  5135.5  167.33    5140  167.19    5157  167.96
  5172.4  167.75  5199.7  168.57  5293.6   170.4  5350.1   171.9  5401.3  173.09
#Mann= 9 ,-1 , 0
  4594.7     .12       0  4647.9    .035       0  4810.4     .12       0
  4987.8     .05       0  4991.8     .12       0  5028.2     .07       0
  5135.5     .12       0  5199.7     .07       0  5350.1     .05       0
Bank Sta=4987.8,4991.8
XS Rating Curve= 0 ,0
Exp/Cntr=0.3,0.1

Type RM Length L Ch R = 1 ,1877    ,373,373,373
BEGIN DESCRIPTION:
Mapping XS 65b4699b
END DESCRIPTION:
XS GIS Cut Line= 3
      2530753.34     13486698.76      2531124.87      13486844.6
      2531506.79     13486684.88
#Sta/Elev= 30
    4601  177.23    4602  177.22  4638.7  175.63  4706.5  173.13  4785.4  170.41
  4823.2  168.53    4853  167.89  4877.4  166.73  4882.8  166.98  4892.8  166.22
  4961.4  164.15  4985.9  161.96  4991.2  161.97  4997.5  161.11  5002.9  161.11
  5008.9  158.66  5014.3  158.47  5019.9  156.74  5020.2  156.24  5023.7  156.24
  5023.9  156.74  5038.1  159.03  5043.6   159.3  5061.9  163.07  5067.3  162.78
  5097.8  164.57  5167.9   166.5  5236.1  169.08  5369.3  173.06  5414.1  173.95
#Mann= 8 ,-1 , 0
    4601     .05       0    4602     .12       0  4638.7     .05       0
  4706.5    .035       0  5019.9    .035       0  5023.9    .035       0
  5236.1     .07       0  5369.3     .05       0
Bank Sta=5019.9,5023.9
XS Rating Curve= 0 ,0
Exp/Cntr=0.3,0.1

Type RM Length L Ch R = 1 ,1504    ,370,370,370
BEGIN DESCRIPTION:
Mapping XS 2a41fd9b
END DESCRIPTION:
XS GIS Cut Line= 3
       2530781.1     13486927.91      2531176.96     13487202.23
      2531437.14     13486969.81
#Sta/Elev= 30
  4520.7  176.48  4549.8  176.01  4572.5  174.66  4578.6  174.88  4598.3  174.07
  4629.3  172.92  4635.4  173.35  4644.1  172.38  4665.1  172.06  4715.7  169.57
  4772.5  167.77  4787.4  166.72  4836.5  165.51  4928.7  163.01  4981.3  160.82
  4996.1  158.75    5006  158.75  5011.1  154.97  5011.4  154.47  5014.9  154.47
  5015.1  154.97  5020.2  156.66    5027  157.29  5034.5  159.58  5048.7  161.29
  5077.6  162.51  5154.8  164.87  5212.8  167.42  5346.1   172.2  5351.2  172.34
#Mann= 10 ,-1 , 0
  4520.7     .12       0  4598.3     .05       0  4715.7    .035       0
  4836.5     .07       0  4928.7    .035       0  5011.1    .035       0
  5015.1    .035       0  5077.6     .12       0  5212.8     .05       0
  5346.1     .07       0
Bank Sta=5011.1,5015.1
XS Rating Curve= 0 ,0
Exp/Cntr=0.3,0.1

Type RM Length L Ch R = 1 ,1134    ,406,406,406
BEGIN DESCRIPTION:
Mapping XS 1f661133
END DESCRIPTION:
XS GIS Cut Line= 3
      2530777.65     13487271.67      2531110.99      13487556.4
      2531517.19     13487400.17
#Sta/Elev= 30
    4574  175.89  4625.3   173.5  4642.6  172.88    4695  170.95  4775.8  166.91
  4782.3  166.66  4902.1  162.14  4939.3  161.12  4957.4  160.03  4998.2  154.16
  4998.5  153.66    5002  153.66  5002.2  154.16  5011.7   156.8  5017.2   156.8
  5025.8  158.01  5031.5   157.2  5038.1  158.98  5056.1  159.94  5061.5  159.39
  5070.3  160.66  5116.1  161.92  5123.8  162.95  5170.8  163.32  5195.4  164.66
  5200.8  164.29  5238.8  165.78  5334.7  169.77  5364.7  170.38  5447.6  174.24
#Mann= 11 ,-1 , 0
    4574     .12       0  4625.3     .05       0  4642.6     .07       0
  4775.8     .12       0  4782.3     .07       0  4902.1     .12       0
  4939.3      .1       0  4998.2     .05       0  5002.2      .1       0
  5025.8     .12       0  5238.8     .05       0
Bank Sta=4998.2,5002.2
XS Rating Curve= 0 ,0
Exp/Cntr=0.3,0.1

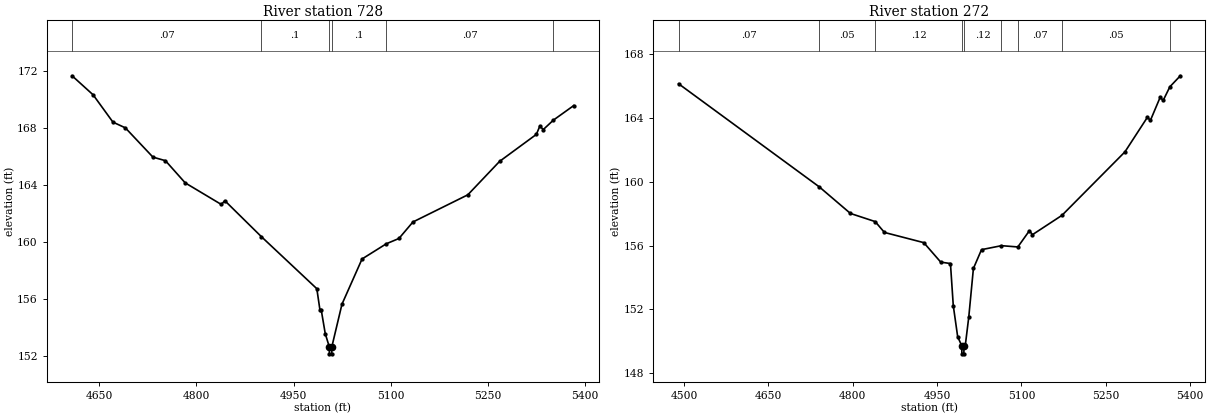
Type RM Length L Ch R = 1 ,728     ,456,456,456
BEGIN DESCRIPTION:
Mapping XS b91867da
END DESCRIPTION:
XS GIS Cut Line= 3
      2530739.44     13487507.75       2530871.4      13487868.9
      2531239.42     13487997.36
#Sta/Elev= 30
  4608.1  171.69  4640.6  170.35  4671.2  168.43  4690.3  168.03  4732.9  165.97
  4752.2  165.72  4782.7  164.16  4838.5  162.64  4843.8  162.91  4900.2  160.38
  4985.8  156.72  4990.6  155.23  4992.6  155.23  4998.8  153.56    5005  152.64
  5005.3  152.14  5008.8  152.14    5009  152.64  5024.6  155.63  5055.6  158.81
  5093.1  159.88  5112.5  160.25  5134.1  161.41  5218.8  163.32  5267.8  165.67
  5324.6  167.57  5329.9  168.15  5335.3  167.91  5350.8  168.57  5382.4   169.6
#Mann= 6 ,-1 , 0
  4608.1     .07       0  4900.2      .1       0    5005     .05       0
    5009      .1       0  5093.1     .07       0  5350.8     .05       0
Bank Sta=5005,5009
XS Rating Curve= 0 ,0
Exp/Cntr=0.3,0.1

Type RM Length L Ch R = 1 ,272     ,0,0,0
BEGIN DESCRIPTION:
TRIB 5 TO HOG THIEF CREEK 1.0
END DESCRIPTION:
XS GIS Cut Line= 3
      2530610.98     13487740.39      2530651.94     13488248.44
      2530996.94     13488413.38
#Sta/Elev= 30
  4490.3  166.15  4740.7  159.68  4795.9  158.02  4839.9  157.51  4856.3  156.83
  4926.3  156.19  4956.4  154.97  4973.7  154.88  4978.7  152.25  4986.5   150.3
  4993.8  149.72    4994  149.22  4997.5  149.22  4997.8  149.72    5000  149.72
  5006.3  151.54  5014.5  154.57  5028.9  155.75  5064.4     156  5093.5  155.92
  5114.1  156.94  5119.5  156.69  5171.9   157.9  5283.9  161.88  5323.7  164.04
  5329.3  163.86  5346.4  165.29    5352  165.11  5363.8  165.96  5382.4  166.65
#Mann= 9 ,-1 , 0
  4490.3     .07       0  4740.7     .05       0  4839.9     .12       0
  4993.8     .05       0  4997.8     .12       0  5064.4     .05       0
  5093.5     .07       0  5171.9     .05       0  5363.8     .07       0
Bank Sta=4993.8,4997.8
XS Rating Curve= 0 ,0
Exp/Cntr=0.3,0.1

Chan Stop Cuts=-1
Use User Specified Reach Order=0
Composite Channel Slope=5