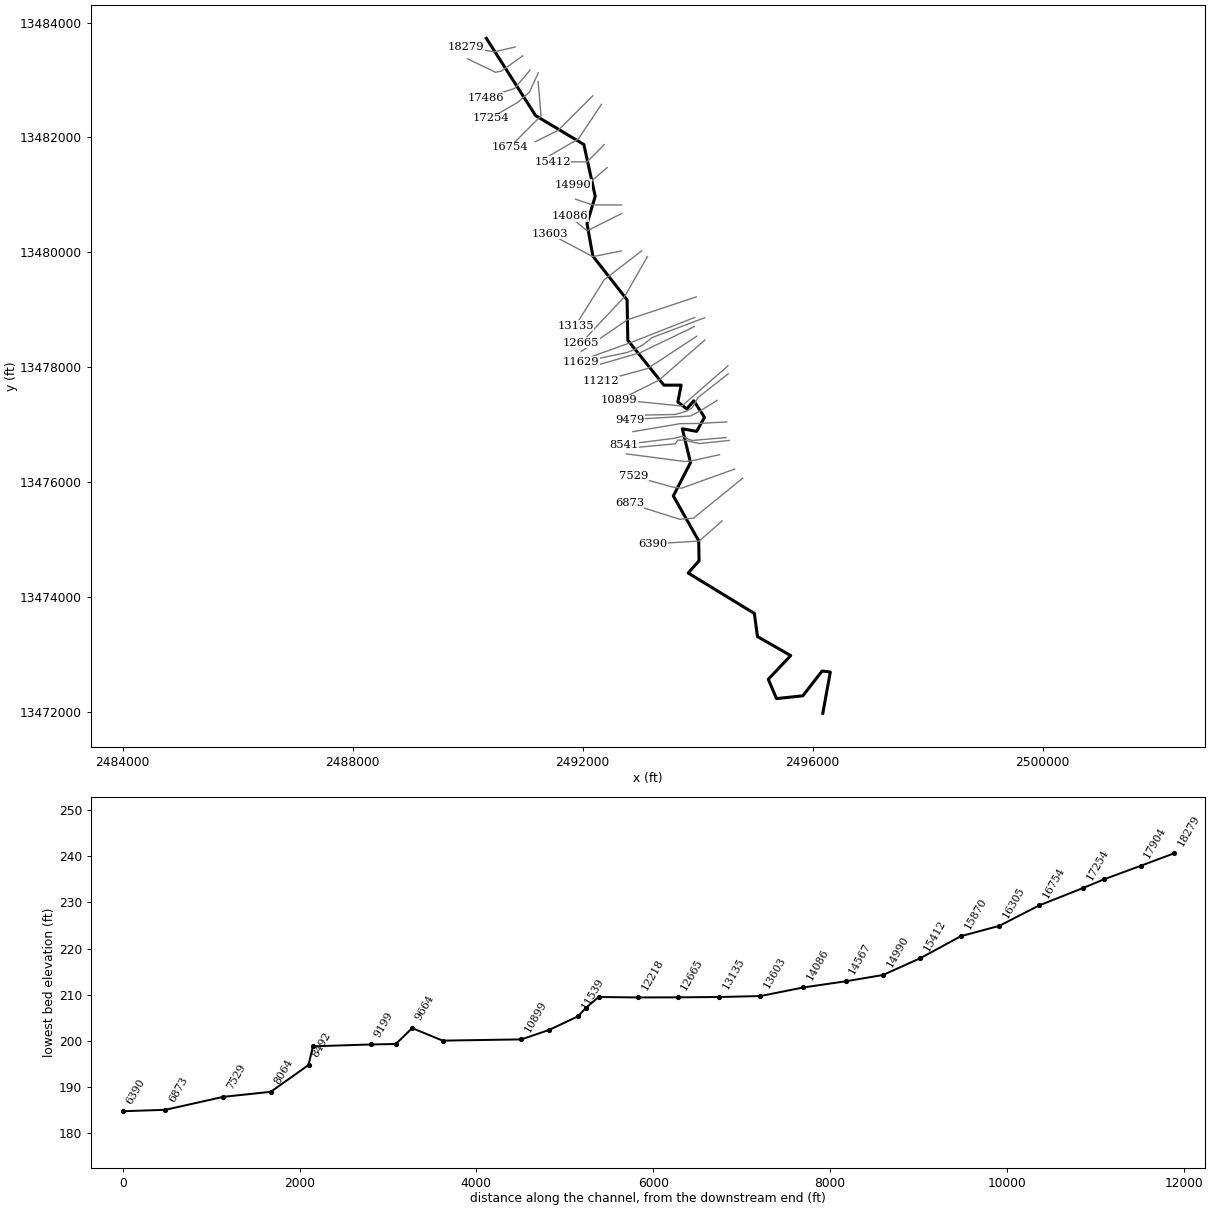
--- TRIB 5 TO PERDIDO CREEK.prj (project) ---

Proj Title=TRIB 5 TO PERDIDO CREEK Base Level Engineering
Current Plan=p01
Default Exp/Contr=0.3,0.1
English Units
Geom File=g01
Flow File=f01
Plan File=p01
Y Axis Title=Elevation
X Axis Title(PF)=Main Channel Distance
X Axis Title(XS)=Station
BEGIN DESCRIPTION:
TRIB 5 TO PERDIDO CREEK
END DESCRIPTION:
DSS Export Rating Curves= 0
DSS Export Rating Curve Sorted= 0
DSS Export Volume Flow Curves= 0
DXF OffsetX= 0
DXF OffsetY= 0
DXF ScaleX= 1
DXF ScaleY= 10

--- TRIB 5 TO PERDIDO CREEK.p01 (plan) ---

Plan Title=Multiple Run
Short Identifier=Multiple
Geom File=g01
Flow File=f01
Subcritical Flow
K Sum by GR= 0
Std Step Tol= 0.01
Critical Tol= 0.01
Num of Std Step Trials= 20
Max Error Tol= 0.3
Flow Tol Ratio= 0.001
Split Flow NTrial= 30
Split Flow Tol= 0.02
Split Flow Ratio= 0.02
Log Output Level= 0
Friction Slope Method= 1
Unsteady Friction Slope Method= 2
Unsteady Bridges Friction Slope Method= 1
Parabolic Critical Depth
Global Vel Dist=  1 , 1 , 1
Global Log Level= 0
CheckData=True
Encroach Param= -1, 0, 0, 0
BEGIN DESCRIPTION:
Multiple Run
END DESCRIPTION:

--- TRIB 5 TO PERDIDO CREEK.f01 (steady flow) ---

Flow Title=Multiple
Number of Profiles=7
Profile Names=10-year,25-year,50-year,1pct_min,100-year,1pct_plu,500-year
River Rch & RM= TRIB 5 TO PERDID,Reach-1,18279
     381     593     777     495     987    1969    1571
River Rch & RM= TRIB 5 TO PERDID,Reach-1,15870
     567     903    1203     776    1549    3091    2540
River Rch & RM= TRIB 5 TO PERDID,Reach-1,13135
    1325    2209    3033    2011    4012    8004    6948
River Rch & RM= TRIB 5 TO PERDID,Reach-1,4713
    1605    2697    3721    2476    4941    9858    8627
Boundary for River Rch & Prof#=TRIB 5 TO PERDID,Reach-1,1
Up Type=0
Dn Type=3
Dn Slope=0.005
Boundary for River Rch & Prof#=TRIB 5 TO PERDID,Reach-1,2
Up Type=0
Dn Type=3
Dn Slope=0.005
Boundary for River Rch & Prof#=TRIB 5 TO PERDID,Reach-1,3
Up Type=0
Dn Type=3
Dn Slope=0.005
Boundary for River Rch & Prof#=TRIB 5 TO PERDID,Reach-1,4
Up Type=0
Dn Type=3
Dn Slope=0.005
Boundary for River Rch & Prof#=TRIB 5 TO PERDID,Reach-1,5
Up Type=0
Dn Type=3
Dn Slope=0.005
Boundary for River Rch & Prof#=TRIB 5 TO PERDID,Reach-1,6
Up Type=0
Dn Type=3
Dn Slope=0.005
Boundary for River Rch & Prof#=TRIB 5 TO PERDID,Reach-1,7
Up Type=0
Dn Type=3
Dn Slope=0.005

--- TRIB 5 TO PERDIDO CREEK.g01 (geometry) ---

Geom Title=Existing Conditions
Program Version=4.10

River Reach=TRIB 5 TO PERDID,Reach-1
Reach XY= 30
        2490325.       13483725.      2491180.44     13482380.18
      2492019.54     13481877.45      2492217.67      13480975.1
      2492074.77     13480500.07       2492176.2      13479935.5
      2492771.46     13479173.54      2492784.43     13478468.39
      2493411.67     13477688.33      2493711.84     13477688.73
      2493654.05     13477394.98      2493809.76     13477274.84
      2493931.84     13477416.24       2494117.4     13477128.34
        2493982.     13476883.83      2493732.49     13476928.62
      2493874.61     13476340.28      2493575.24     13475759.78
       2494017.2     13474978.42      2494022.95     13474630.86
      2493833.95     13474418.33      2494984.79     13473714.47
      2495038.61     13473311.79      2495617.24     13472981.17
      2495227.05     13472569.14      2495368.93     13472232.47
      2495827.45     13472280.46       2496161.7     13472711.67
       2496305.6     13472695.67        2496175.       13471975.

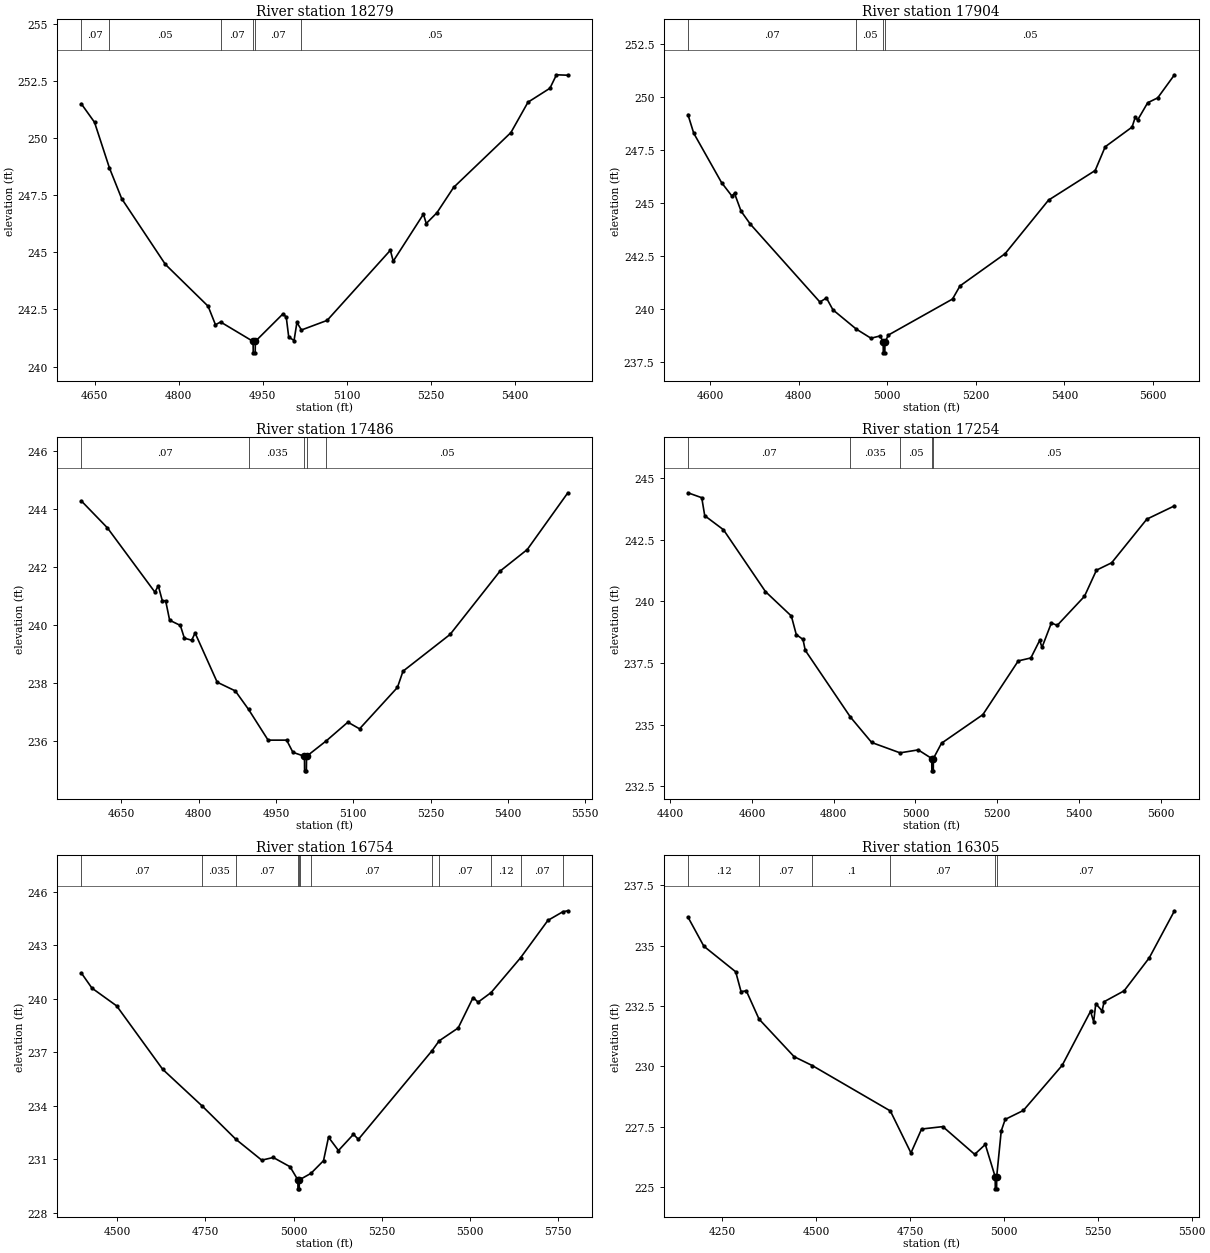
Type RM Length L Ch R = 1 ,18279   ,375,375,375
BEGIN DESCRIPTION:
TRIB 5 TO PERDIDO CREEK 31.0
END DESCRIPTION:
XS GIS Cut Line= 3
      2490825.02     13483575.01      2490461.43     13483488.24
      2489975.01       13483575.
#Sta/Elev= 30
  4626.2   251.5  4649.8  250.69  4676.4  248.69  4698.2  247.35  4776.2  244.47
  4852.4  242.64  4865.5  241.83  4874.7  241.95  4932.6   241.1  4932.9   240.6
  4936.4   240.6  4936.6   241.1  4986.1  242.31  4991.8  242.16  4996.2  241.29
  5005.7  241.14  5010.8  241.93  5018.9   241.6  5064.7  242.02  5177.5  245.09
  5182.6  244.61  5236.5  246.67  5241.5  246.26  5260.5  246.73  5290.3  247.84
  5392.5  250.24    5423  251.57  5462.1  252.18  5473.8  252.77  5494.1  252.75
#Mann= 6 ,-1 , 0
  4626.2     .07       0  4676.4     .05       0  4874.7     .07       0
  4932.6     .05       0  4936.6     .07       0  5018.9     .05       0
Bank Sta=4932.6,4936.6
XS Rating Curve= 0 ,0
Exp/Cntr=0.3,0.1

Type RM Length L Ch R = 1 ,17904   ,418,418,418
BEGIN DESCRIPTION:
Mapping XS a33f3537
END DESCRIPTION:
XS GIS Cut Line= 4
      2490956.67      13483420.5      2490587.73     13483155.73
      2490483.56     13483134.03       2489998.7     13483367.81
#Sta/Elev= 30
    4550  249.17  4563.1  248.29  4625.9  245.96  4649.1  245.33  4655.2  245.45
    4670  244.61  4690.8     244    4848  240.32  4862.8  240.51  4877.5  239.95
  4930.3  239.04  4963.4  238.61  4984.3  238.72  4990.9  238.42  4991.2  237.92
  4994.7  237.92  4994.9  238.42  5002.7  238.76  5147.5  240.46  5164.4  241.08
  5266.2   242.6  5364.3  245.13  5469.7  246.53  5492.3  247.65    5553  248.58
  5560.1  249.04  5565.7  248.92  5588.3  249.73  5610.9  249.96  5648.8  251.05
#Mann= 4 ,-1 , 0
    4550     .07       0  4930.3     .05       0  4990.9     .05       0
  4994.9     .05       0
Bank Sta=4990.9,4994.9
XS Rating Curve= 0 ,0
Exp/Cntr=0.3,0.1

Type RM Length L Ch R = 1 ,17486   ,232,232,232
BEGIN DESCRIPTION:
Mapping XS a79a9d3e
END DESCRIPTION:
XS GIS Cut Line= 3
      2491082.53     13483168.77      2490813.43     13482851.91
      2490309.93     13482691.32
#Sta/Elev= 30
  4572.1  244.29  4622.7  243.36  4714.9  241.14  4721.5  241.36  4729.2  240.85
  4735.8  240.84  4743.5  240.17  4764.3  239.99  4772.1  239.55  4786.3  239.48
  4792.9  239.73  4835.8  238.03  4870.9  237.73  4896.7  237.09  4934.6  236.03
  4970.6  236.03  4982.7  235.61  5005.2  235.47  5005.4  234.97  5008.9  234.97
  5009.2  235.47  5047.8  236.01  5089.4  236.65  5112.1  236.42  5185.6  237.85
  5196.4  238.41  5287.8  239.68  5384.4  241.86  5437.5  242.61  5516.3  244.57
#Mann= 5 ,-1 , 0
  4572.1     .07       0  4896.7    .035       0  5005.2    .035       0
  5009.2    .035       0  5047.8     .05       0
Bank Sta=5005.2,5009.2
XS Rating Curve= 0 ,0
Exp/Cntr=0.3,0.1

Type RM Length L Ch R = 1 ,17254   ,500,500,500
BEGIN DESCRIPTION:
Mapping XS bfbf6002
END DESCRIPTION:
XS GIS Cut Line= 4
      2491227.96     13483125.71      2491071.72     13482787.17
      2490868.59     13482610.09      2490394.65     13482334.06
#Sta/Elev= 30
  4443.2  244.41    4477  244.21  4484.3  243.48  4530.2  242.91    4633   240.4
  4696.3  239.41  4708.3  238.66  4724.8  238.46  4730.3  238.02  4840.9  235.31
  4892.9  234.28  4962.3  233.86  5006.8  233.98  5039.9  233.63  5040.2  233.13
  5043.7  233.13  5043.9  233.63  5063.8  234.25    5165  235.41  5251.7  237.59
  5282.5  237.71    5304  238.42  5309.8  238.14  5332.7  239.13    5347  239.03
  5413.7  240.21    5443  241.27  5480.2  241.57  5566.3  243.34    5634  243.88
#Mann= 5 ,-1 , 0
  4443.2     .07       0  4840.9    .035       0  4962.3     .05       0
  5039.9     .05       0  5043.9     .05       0
Bank Sta=5039.9,5043.9
XS Rating Curve= 0 ,0
Exp/Cntr=0.3,0.1

Type RM Length L Ch R = 1 ,16754   ,449,449,449
BEGIN DESCRIPTION:
TRIB 5 TO PERDIDO CREEK 28.0
END DESCRIPTION:
XS GIS Cut Line= 3
        2491225.     13482974.98        2491275.       13482375.
      2490724.98     13481824.98
#Sta/Elev= 30
  4397.9  241.45    4428   240.6  4498.2   239.6  4628.7  236.04  4741.2  233.97
  4836.4  232.11  4909.6  230.94  4942.3  231.09  4989.9  230.57  5012.1  229.83
  5012.4  229.33  5015.9  229.33  5016.1  229.83  5019.5  229.87  5049.3   230.2
  5084.8  230.91    5099  232.23  5127.2  231.48  5169.7  232.39  5183.8  232.11
  5392.8  237.09  5412.9  237.64  5466.7  238.36  5509.1  240.07  5523.2  239.81
  5560.2  240.35  5643.6   242.3  5721.2   244.4    5764  244.89  5777.8  244.94
#Mann= 12 ,-1 , 0
  4397.9     .07       0  4741.2    .035       0  4836.4     .07       0
  5012.1     .05       0  5016.1     .07       0  5019.5    .035       0
  5049.3     .07       0  5392.8     .12       0  5412.9     .07       0
  5560.2     .12       0  5643.6     .07       0    5764     .12       0
Bank Sta=5012.1,5016.1
XS Rating Curve= 0 ,0
Exp/Cntr=0.3,0.1

Type RM Length L Ch R = 1 ,16305   ,435,435,435
BEGIN DESCRIPTION:
TRIB 5 TO PERDIDO CREEK 27.0
END DESCRIPTION:
XS GIS Cut Line= 3
      2492174.97     13482724.97        2491575.       13482125.
        2491175.       13481925.
#Sta/Elev= 30
  4158.6  236.19    4201  234.98  4285.8  233.92    4300   233.1  4314.1  233.13
  4347.9  231.96  4441.4   230.4    4490  230.03  4697.6  228.15  4752.5  226.41
  4780.8   227.4  4837.4   227.5  4922.2  226.35  4950.5  226.76  4976.8  225.42
  4977.1  224.92  4980.6  224.92  4980.8  225.42  4992.9  227.32  5003.5   227.8
  5051.8  228.17  5155.2  230.04  5230.7  232.28  5239.1  231.85  5244.7   232.6
  5261.4   232.3    5267  232.68  5320.1  233.13  5387.2   234.5  5454.3  236.45
#Mann= 6 ,-1 , 0
  4158.6     .12       0  4347.9     .07       0    4490      .1       0
  4697.6     .07       0  4976.8     .05       0  4980.8     .07       0
Bank Sta=4976.8,4980.8
XS Rating Curve= 0 ,0
Exp/Cntr=0.3,0.1

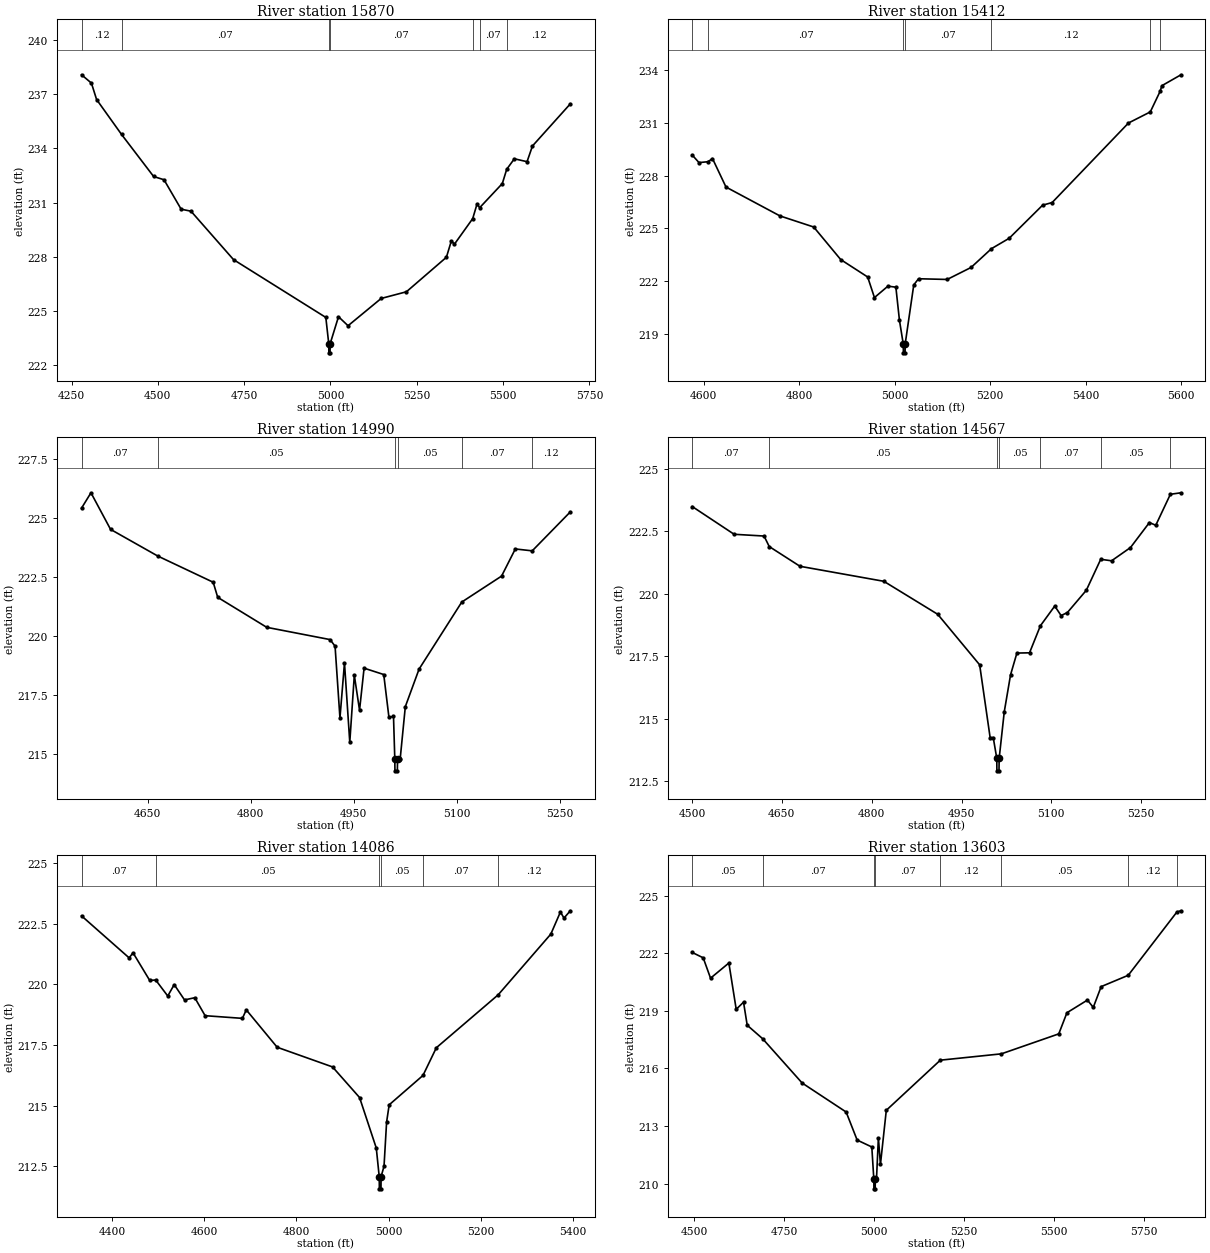
Type RM Length L Ch R = 1 ,15870   ,458,458,458
BEGIN DESCRIPTION:
TRIB 5 TO PERDIDO CREEK 26.0
END DESCRIPTION:
XS GIS Cut Line= 3
      2492325.01     13482575.02        2491925.       13481975.
      2491324.96     13481624.98
#Sta/Elev= 30
  4278.9  238.08  4307.5  237.62  4322.5  236.71  4394.7  234.78  4487.7  232.45
  4517.8  232.27  4567.4  230.64  4595.9  230.53  4719.1  227.85  4986.5  224.65
    4995  223.19  4995.3  222.69  4998.8  222.69    4999  223.19  5023.2  224.69
  5050.9  224.19  5146.8   225.7    5220  226.07  5335.8  227.98  5350.2  228.89
  5358.9   228.7    5412  230.12  5424.7  230.94    5432  230.72  5497.8  232.06
  5510.5  232.85  5532.6  233.43  5569.4  233.27  5585.1  234.14  5694.7  236.47
#Mann= 7 ,-1 , 0
  4278.9     .12       0  4394.7     .07       0    4995     .05       0
    4999     .07       0    5412     .12       0    5432     .07       0
  5510.5     .12       0
Bank Sta=4995,4999
XS Rating Curve= 0 ,0
Exp/Cntr=0.3,0.1

Type RM Length L Ch R = 1 ,15412   ,422,422,422
BEGIN DESCRIPTION:
TRIB 5 TO PERDIDO CREEK 25.0
END DESCRIPTION:
XS GIS Cut Line= 3
      2492375.03     13481875.03        2492075.       13481575.
      2491475.01       13481575.
#Sta/Elev= 30
  4575.7  229.17  4589.9  228.74  4608.7  228.79  4618.2  228.97  4646.5  227.35
  4759.6  225.71  4830.3  225.08  4886.9  223.23  4943.4  222.24  4957.6  221.07
  4985.9  221.72  5002.5  221.66    5010  219.78    5018  218.43  5018.3  217.93
  5021.8  217.93    5022  218.43    5040  221.79    5050  222.14    5110   222.1
    5160  222.78  5202.9  223.85    5240  224.44    5310  226.32    5330  226.47
    5490  230.99  5535.7  231.62  5556.1  232.78    5560  233.11    5600  233.73
#Mann= 7 ,-1 , 0
  4575.7     .12       0  4608.7     .07       0    5018     .05       0
    5022     .07       0  5202.9     .12       0  5535.7     .07       0
  5556.1     .12       0
Bank Sta=5018,5022
XS Rating Curve= 0 ,0
Exp/Cntr=0.3,0.1

Type RM Length L Ch R = 1 ,14990   ,423,423,423
BEGIN DESCRIPTION:
TRIB 5 TO PERDIDO CREEK 24.0
END DESCRIPTION:
XS GIS Cut Line= 3
      2492424.99     13481474.99        2492075.       13481175.
      2491824.96       13481175.
#Sta/Elev= 30
    4554  225.42  4567.7  226.07  4596.2  224.52  4664.9  223.39  4745.5  222.28
  4752.1  221.64  4823.4  220.37  4915.6  219.85  4922.8  219.57  4929.9  216.53
  4936.5  218.86  4944.2   215.5  4950.8  218.34  4958.4  216.86    4965  218.64
  4993.6  218.37  5001.2  216.55  5007.8   216.6  5009.7  214.79  5009.9  214.29
  5013.4  214.29  5013.7  214.79  5017.5  214.79    5025  217.01    5045   218.6
  5107.1  221.44    5165  222.54    5185  223.69  5209.6  223.61    5265  225.26
#Mann= 6 ,-1 , 0
    4554     .07       0  4664.9     .05       0  5009.7     .05       0
  5013.7     .05       0  5107.1     .07       0  5209.6     .12       0
Bank Sta=5009.7,5013.7
XS Rating Curve= 0 ,0
Exp/Cntr=0.3,0.1

Type RM Length L Ch R = 1 ,14567   ,481,481,481
BEGIN DESCRIPTION:
TRIB 5 TO PERDIDO CREEK 23.0
END DESCRIPTION:
XS GIS Cut Line= 3
      2492675.02       13480825.        2492175.       13480825.
      2491875.04     13480924.99
#Sta/Elev= 30
  4500.3  223.49  4570.3  222.38  4620.3  222.31  4628.9  221.89  4680.3   221.1
  4820.3   220.5  4910.3  219.18  4980.3  217.16  4997.8  214.25    5003  214.25
  5008.9  213.42  5009.1  212.92  5012.6  212.92  5012.9  213.42  5021.4  215.28
  5031.9  216.76  5042.5  217.63  5063.6  217.64  5081.7  218.72  5105.7  219.51
  5116.3  219.13  5126.8  219.25  5158.4  220.14  5182.5  221.38  5200.6  221.32
  5232.2  221.85  5263.8  222.85  5274.4  222.74  5298.8  223.98  5316.5  224.04
#Mann= 7 ,-1 , 0
  4500.3     .07       0  4628.9     .05       0  5008.9     .05       0
  5012.9     .05       0  5081.7     .07       0  5182.5     .05       0
  5298.8     .07       0
Bank Sta=5008.9,5012.9
XS Rating Curve= 0 ,0
Exp/Cntr=0.3,0.1

Type RM Length L Ch R = 1 ,14086   ,483,483,483
BEGIN DESCRIPTION:
TRIB 5 TO PERDIDO CREEK 22.0
END DESCRIPTION:
XS GIS Cut Line= 3
      2492674.96     13480674.98        2492075.       13480375.
      2491774.99       13480625.
#Sta/Elev= 30
  4333.3  222.82  4436.7  221.09  4445.1   221.3  4481.4  220.16  4494.3  220.18
  4520.5  219.52  4534.5  219.99  4556.9  219.36  4579.2  219.45  4601.6  218.71
  4682.6   218.6    4691  218.95  4758.1  217.41  4878.3   216.6    4937  215.34
  4973.3  213.26  4979.7  212.08    4980  211.58  4983.5  211.58  4983.7  212.08
  4990.1  212.51  4995.7  214.33  5001.3  215.04  5074.7  216.25  5103.7  217.39
    5238  219.57  5352.3  222.07  5373.1  222.98  5380.9  222.73  5394.6  223.03
#Mann= 6 ,-1 , 0
  4333.3     .07       0  4494.3     .05       0  4979.7     .05       0
  4983.7     .05       0  5074.7     .07       0    5238     .12       0
Bank Sta=4979.7,4983.7
XS Rating Curve= 0 ,0
Exp/Cntr=0.3,0.1

Type RM Length L Ch R = 1 ,13603   ,468,468,468
BEGIN DESCRIPTION:
TRIB 5 TO PERDIDO CREEK 21.0
END DESCRIPTION:
XS GIS Cut Line= 3
        2492675.       13480025.        2492175.       13479925.
        2491425.       13480325.
#Sta/Elev= 30
  4494.3  222.04  4524.9  221.76  4545.3   220.7  4596.3  221.49  4616.7  219.08
  4637.1  219.45  4647.3  218.25  4690.1  217.55  4800.2  215.24  4922.6  213.73
  4953.2  212.27    4994  211.91  4999.6  210.23  4999.9  209.73  5003.4  209.73
  5003.6  210.23    5007  210.23  5012.3  212.39    5018     211  5034.3  213.82
  5184.6  216.43  5354.5  216.76  5514.2   217.8  5536.9   218.9  5593.9  219.56
  5610.2  219.18  5632.1  220.26  5707.4  220.85    5843  224.15  5854.2  224.21
#Mann= 8 ,-1 , 0
  4494.3     .05       0  4690.1     .07       0  4999.6     .05       0
  5003.6     .07       0  5184.6     .12       0  5354.5     .05       0
  5707.4     .12       0    5843     .07       0
Bank Sta=4999.6,5003.6
XS Rating Curve= 0 ,0
Exp/Cntr=0.3,0.1

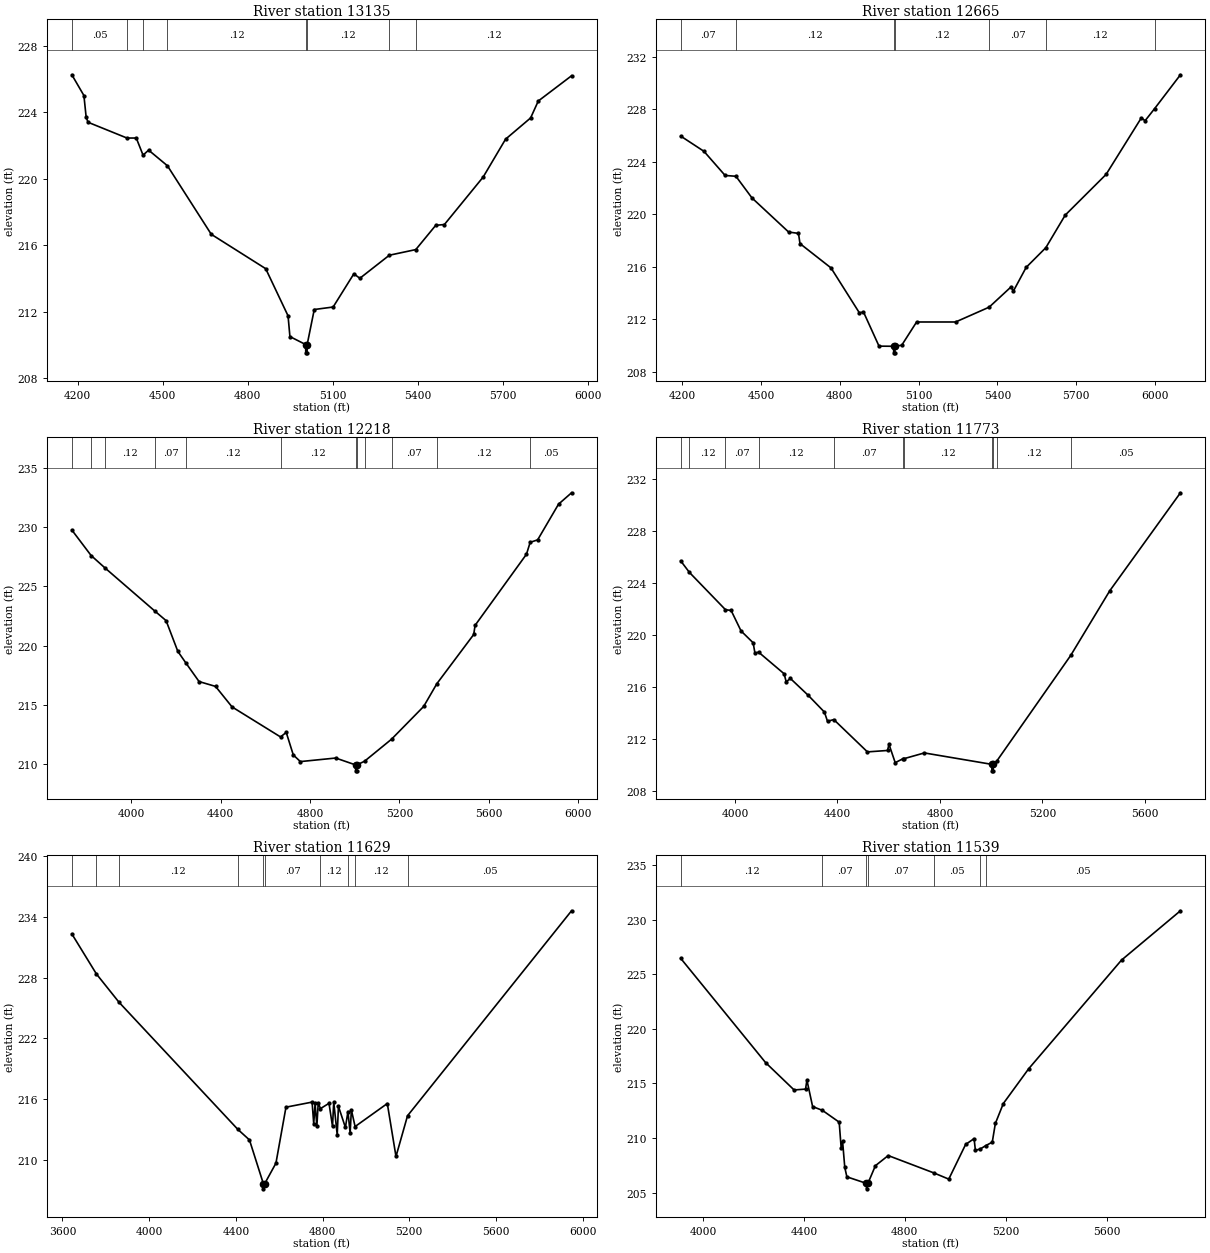
Type RM Length L Ch R = 1 ,13135   ,470,470,470
BEGIN DESCRIPTION:
TRIB 5 TO PERDIDO CREEK 20.0
END DESCRIPTION:
XS GIS Cut Line= 3
      2493025.02     13480025.01        2492375.       13479525.
      2491874.99     13478724.99
#Sta/Elev= 30
  4179.9  226.27  4222.5  225.02  4230.4  223.72    4237  223.41  4374.4  222.46
  4407.3  222.46  4431.2  221.43  4450.9  221.73  4517.2  220.79    4672  216.66
    4864  214.59  4942.9  211.75  4949.5   210.5    5005  210.02  5005.4  209.52
    5010  209.52  5010.4  210.02  5035.4  212.13    5102  212.28  5175.1  214.28
  5196.3  214.01  5300.3   215.4  5393.7  215.74    5464   217.2  5494.7  217.25
  5631.5  220.11  5710.5  222.39  5798.9  223.67    5826  224.69  5943.4  226.21
#Mann= 8 ,-1 , 0
  4179.9     .05       0  4374.4     .07       0  4431.2     .05       0
  4517.2     .12       0    5005     .05       0  5010.4     .12       0
  5300.3     .07       0  5393.7     .12       0
Bank Sta=5005,5010.4
XS Rating Curve= 0 ,0
Exp/Cntr=0.3,0.1

Type RM Length L Ch R = 1 ,12665   ,447,447,447
BEGIN DESCRIPTION:
TRIB 5 TO PERDIDO CREEK 19.0
END DESCRIPTION:
XS GIS Cut Line= 3
      2493124.98     13479924.96        2492725.       13479225.
      2491974.98     13478424.98
#Sta/Elev= 30
  4194.1  225.96  4282.6   224.8  4363.2  222.96  4404.3   222.9  4465.4  221.25
  4605.1  218.65  4642.5  218.55  4648.3  217.77  4766.3  215.92  4874.3   212.5
  4890.1  212.56  4949.2  209.96  5004.7  209.95  5005.1  209.45  5009.7  209.45
  5010.1  209.95  5035.7  210.03  5092.3   211.8  5240.8   211.8  5368.6  212.93
  5452.9  214.49  5460.2  214.13  5509.5  215.96  5584.4  217.46  5658.2  219.94
  5813.8  223.04  5948.1  227.35  5962.3  227.13  5998.5  228.05  6096.9  230.63
#Mann= 7 ,-1 , 0
  4194.1     .07       0  4404.3     .12       0  5004.7     .05       0
  5010.1     .12       0  5368.6     .07       0  5584.4     .12       0
  5998.5     .05       0
Bank Sta=5004.7,5010.1
XS Rating Curve= 0 ,0
Exp/Cntr=0.3,0.1

Type RM Length L Ch R = 1 ,12218   ,445,445,445
BEGIN DESCRIPTION:
TRIB 5 TO PERDIDO CREEK 18.0
END DESCRIPTION:
XS GIS Cut Line= 3
      2493974.97     13479224.99        2492775.       13478825.
      2491975.01       13478275.
#Sta/Elev= 30
  3734.7  229.74  3820.9  227.59  3882.5  226.55  4107.5  222.88  4156.3   222.1
    4209   219.5  4245.2  218.52  4303.9  216.96  4377.7  216.55  4451.5  214.82
  4668.3  212.29  4693.9  212.67  4725.5  210.77  4757.1  210.21  4915.3  210.51
  5004.1  209.93  5004.6  209.43  5009.4  209.43  5009.9  209.93  5044.2  210.24
  5165.1   212.1  5308.8  214.86  5367.8  216.78  5532.7  220.93  5538.8   221.7
  5768.8   227.7  5785.2   228.7  5818.7  228.91  5912.2  231.92  5970.4  232.88
#Mann= 12 ,-1 , 0
  3734.7     .12       0  3820.9     .07       0  3882.5     .12       0
  4107.5     .07       0  4245.2     .12       0  4668.3     .12       0
  5004.1     .05       0  5009.9     .12       0  5044.2     .12       0
  5165.1     .07       0  5367.8     .12       0  5785.2     .05       0
Bank Sta=5004.1,5009.9
XS Rating Curve= 0 ,0
Exp/Cntr=0.3,0.1

Type RM Length L Ch R = 1 ,11773   ,144,144,144
BEGIN DESCRIPTION:
TRIB 5 TO PERDIDO CREEK 17.0
END DESCRIPTION:
XS GIS Cut Line= 3
      2493948.01     13478866.68        2492825.       13478425.
      2492125.04     13478175.02
#Sta/Elev= 30
  3788.5   225.7  3822.6  224.81  3963.1  221.94  3985.2  221.88    4024   220.3
  4071.1  219.39  4078.2  218.59  4092.2  218.67    4192     217  4200.1  216.38
  4216.4  216.64    4286  215.34  4349.2  214.05  4361.3  213.34  4385.9  213.47
  4517.1  210.98  4595.7  211.09  4601.1  211.57  4625.5  210.15  4657.5  210.47
  4658.4  210.45  4739.2   210.9  5002.4  210.02  5002.9  209.52  5007.8  209.52
  5008.2  210.02  5022.8   210.3  5310.2  218.41  5462.5  223.39  5738.5  230.95
#Mann= 11 ,-1 , 0
  3788.5     .07       0  3822.6     .12       0  3963.1     .07       0
  4092.2     .12       0  4385.9     .07       0  4657.5     .12       0
  4658.4     .12       0  5002.4     .05       0  5008.2     .12       0
  5022.8     .12       0  5310.2     .05       0
Bank Sta=5002.4,5008.2
XS Rating Curve= 0 ,0
Exp/Cntr=0.3,0.1

Type RM Length L Ch R = 1 ,11629   ,90,90,90
BEGIN DESCRIPTION:
Mapping XS 0d55838a
END DESCRIPTION:
XS GIS Cut Line= 6
      2494121.52     13478862.09      2493205.19      13478516.3
      2493055.35     13478395.28      2492893.97     13478305.94
      2492772.94     13478256.96      2491972.31     13478089.92
#Sta/Elev= 30
  3643.5   232.3  3756.9  228.35  3860.8  225.57  4409.2  213.03  4462.8  211.99
    4527  207.67  4527.4  207.17  4532.8  207.67  4584.9   209.7  4631.2  215.22
  4751.7  215.72  4759.2  213.59  4765.6  215.59  4773.6  213.32    4780  215.65
  4790.3  215.08  4829.7   215.6  4845.8  213.32  4851.5  215.72  4867.5   212.5
  4873.2   215.3  4905.3  213.22  4917.1  214.79  4927.1  212.66  4932.8  214.95
    4950  213.31  5098.6  215.58  5138.6  210.36  5191.8  214.37  5948.4  234.58
#Mann= 10 ,-1 , 0
  3643.5    .035       0  3756.9     .07       0  3860.8     .12       0
  4409.2     .07       0    4527     .05       0  4532.8     .07       0
  4790.3     .12       0  4917.1     .05       0    4950     .12       0
  5191.8     .05       0
Bank Sta=4527,4532.8
XS Rating Curve= 0 ,0
Exp/Cntr=0.3,0.1

Type RM Length L Ch R = 1 ,11539   ,327,327,327
BEGIN DESCRIPTION:
Mapping XS 72bfefa1
END DESCRIPTION:
XS GIS Cut Line= 3
      2493940.99     13478706.93      2493003.53     13478255.56
      2492100.77     13477991.68
#Sta/Elev= 30
  3911.9  226.46  4248.3  216.91  4361.4   214.4  4406.7  214.48  4412.2   215.3
  4434.8  212.88  4473.7  212.53  4540.1  211.45  4547.9  209.12  4553.5  209.72
  4562.3   207.3  4570.6  206.44  4648.2  205.84  4648.6  205.34    4654  205.84
  4683.7  207.46  4734.5  208.39  4916.4  206.79  4974.5  206.23  5041.4  209.41
  5074.9  209.94  5080.1  208.87    5099  208.99  5121.2   209.3    5147  209.62
  5159.2  211.33  5190.9  213.16  5291.2  216.34  5659.3   226.3  5892.9  230.82
#Mann= 7 ,-1 , 0
  3911.9     .12       0  4473.7     .07       0  4648.2     .05       0
    4654     .07       0  4916.4     .05       0    5099     .12       0
  5121.2     .05       0
Bank Sta=4648.2,4654
XS Rating Curve= 0 ,0
Exp/Cntr=0.3,0.1

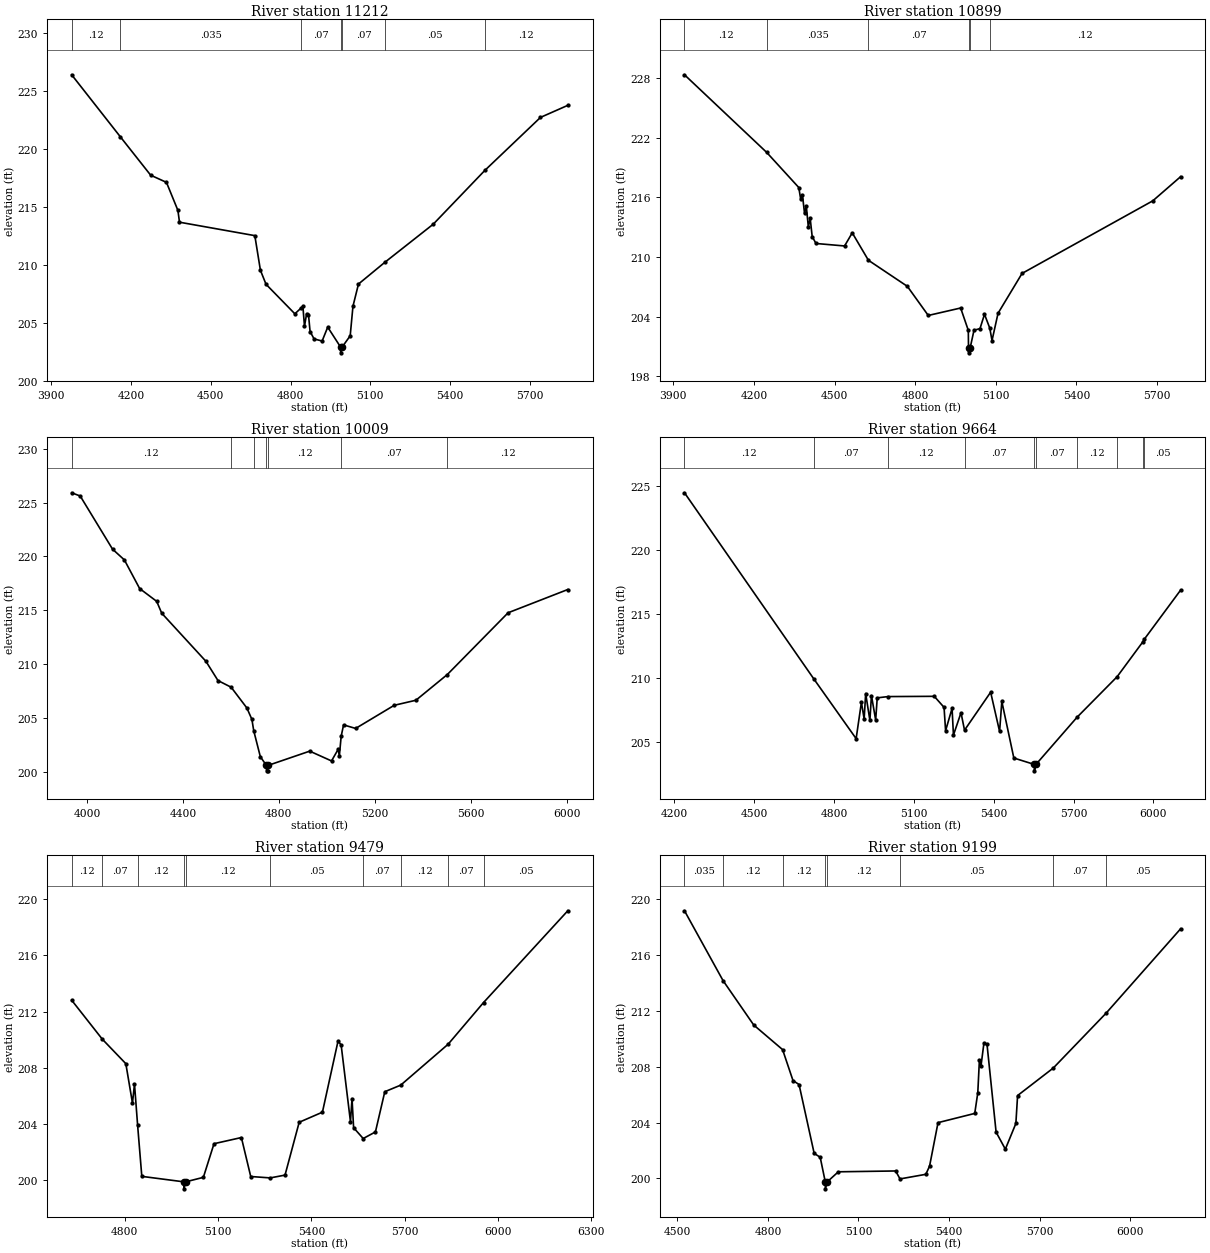
Type RM Length L Ch R = 1 ,11212   ,313,313,313
BEGIN DESCRIPTION:
Mapping XS d50eafc5
END DESCRIPTION:
XS GIS Cut Line= 3
      2493982.68     13478540.27      2493128.53     13477977.78
        2492316.     13477755.55
#Sta/Elev= 30
  3977.2   226.4  4160.4  221.04  4274.2  217.73  4333.6  217.11  4376.6  214.69
  4382.6  213.67  4665.8  212.51  4686.8  209.52  4707.9  208.31  4816.3  205.76
  4839.7  206.26  4846.5   206.4  4852.5  204.68  4860.5  205.78  4867.5   205.7
  4873.5  204.23  4888.6  203.59  4918.8  203.41  4939.8  204.61  4988.1  202.89
  4988.5  202.39    4994  202.89  5024.3  203.86  5034.7  206.41  5055.4  208.33
  5154.2   210.2  5336.6   213.5  5530.4  218.14  5739.7  222.72  5842.3  223.76
#Mann= 7 ,-1 , 0
  3977.2     .12       0  4160.4    .035       0  4839.7     .07       0
  4988.1     .05       0    4994     .07       0  5154.2     .05       0
  5530.4     .12       0
Bank Sta=4988.1,4994
XS Rating Curve= 0 ,0
Exp/Cntr=0.3,0.1

Type RM Length L Ch R = 1 ,10899   ,890,890,890
BEGIN DESCRIPTION:
TRIB 5 TO PERDIDO CREEK 15.0
END DESCRIPTION:
XS GIS Cut Line= 3
      2494125.01     13478475.01        2493325.       13477775.
      2492624.96     13477424.98
#Sta/Elev= 30
  3941.9  228.32  4247.4  220.52  4367.1  216.98  4374.2  215.81  4380.9  216.19
  4388.5  214.38  4395.1  215.11  4402.7     213  4409.4  213.91    4417  212.04
  4431.2  211.35  4537.5   211.1    4566  212.42  4626.2  209.66    4771  207.04
  4848.8  204.11  4969.3  204.86  4997.8  202.61  4998.5  200.85    4999  200.35
  5004.7  200.85  5018.9  202.62  5041.3  202.79    5058  204.23  5077.6  202.84
    5086  201.59  5108.4  204.33  5197.8  208.34  5684.1  215.64  5787.6  218.07
#Mann= 6 ,-1 , 0
  3941.9     .12       0  4247.4    .035       0  4626.2     .07       0
  4998.5     .05       0  5004.7     .07       0  5077.6     .12       0
Bank Sta=4998.5,5004.7
XS Rating Curve= 0 ,0
Exp/Cntr=0.3,0.1

Type RM Length L Ch R = 1 ,10009   ,345,345,345
BEGIN DESCRIPTION:
TRIB 5 TO PERDIDO CREEK 14.0
END DESCRIPTION:
XS GIS Cut Line= 3
      2494525.03     13478025.03        2493725.       13477325.
      2492725.05       13477425.
#Sta/Elev= 30
  3936.5  225.92  3972.1  225.62  4106.9  220.68  4156.3  219.68  4219.9  217.02
    4291  215.83  4311.9  214.73  4496.1  210.26  4546.4  208.47  4601.3  207.85
  4666.9  205.92  4687.8  204.86  4695.5   203.8  4722.9   201.4  4748.3  200.58
  4748.8  200.08    4754  200.08  4754.5  200.58  4928.9  201.91  5019.7     201
  5047.3  202.08  5052.3  201.46  5059.9  203.29  5069.9  204.35  5120.2  204.02
    5281  206.17  5371.4  206.64  5502.4  209.03  5755.8  214.77  6004.5  216.93
#Mann= 7 ,-1 , 0
  3936.5     .12       0  4601.3     .07       0  4695.5     .12       0
  4748.3     .05       0  4754.5     .12       0  5059.9     .07       0
  5502.4     .12       0
Bank Sta=4748.3,4754.5
XS Rating Curve= 0 ,0
Exp/Cntr=0.3,0.1

Type RM Length L Ch R = 1 ,9664    ,185,185,185
BEGIN DESCRIPTION:
Mapping XS 09bbdc5c
END DESCRIPTION:
XS GIS Cut Line= 6
      2494530.21     13477885.67      2494005.05     13477473.35
      2493905.23      13477295.4       2493805.4     13477234.64
      2493610.09     13477178.21      2492938.69     13477165.22
#Sta/Elev= 30
  4238.8  224.47  4723.8  209.98  4883.5   205.3  4903.3  208.13  4913.6  206.84
  4919.3  208.82  4935.2  206.72    4941  208.66  4956.9  206.75  4962.7  208.48
  5003.3  208.58  5176.9   208.6  5213.7  207.74  5219.5  205.92  5243.8  207.66
    5249  205.58  5277.4  207.32  5290.6  205.96  5388.7  208.92  5422.3  205.86
  5430.7   208.2  5475.8  203.79  5552.6  203.29  5553.1  202.79  5558.9  203.29
  5713.3  206.97  5863.8  210.13  5960.8  212.86  5966.1  213.06  6102.2  216.88
#Mann= 10 ,-1 , 0
  4238.8     .12       0  4723.8     .07       0  5003.3     .12       0
  5290.6     .07       0  5552.6     .05       0  5558.9     .07       0
  5713.3     .12       0  5863.8     .07       0  5960.8     .12       0
  5966.1     .05       0
Bank Sta=5552.6,5558.9
XS Rating Curve= 0 ,0
Exp/Cntr=0.3,0.1

Type RM Length L Ch R = 1 ,9479    ,280,280,280
BEGIN DESCRIPTION:
Mapping XS e53590a4
END DESCRIPTION:
XS GIS Cut Line= 4
      2494336.85     13477422.22      2494010.47     13477220.84
      2493871.59     13477151.39      2492818.02     13477089.01
#Sta/Elev= 30
  4629.8  212.81  4728.2  210.03  4803.9  208.28  4825.2  205.47  4831.7  206.82
  4841.7   203.9  4855.2  200.24    4990  199.85  4990.5  199.35  4996.3  199.85
    5053  200.17  5087.2  202.57  5175.2  203.01  5205.2  200.23  5267.8  200.13
  5315.4  200.33  5360.9   204.1  5435.6  204.82  5485.7  209.89  5495.7  209.62
  5525.7  204.14  5530.7  205.79  5535.8  203.71  5566.6  202.94  5605.9  203.41
    5636  206.28  5687.2  206.75  5839.6  209.67  5953.2  212.64    6224  219.19
#Mann= 10 ,-1 , 0
  4629.8     .12       0  4728.2     .07       0  4841.7     .12       0
    4990     .05       0  4996.3     .12       0  5267.8     .05       0
  5566.6     .07       0  5687.2     .12       0  5839.6     .07       0
  5953.2     .05       0
Bank Sta=4990,4996.3
XS Rating Curve= 0 ,0
Exp/Cntr=0.3,0.1

Type RM Length L Ch R = 1 ,9199    ,658,658,658
BEGIN DESCRIPTION:
Mapping XS e2f38245
END DESCRIPTION:
XS GIS Cut Line= 4
      2494504.15       13477048.      2494026.75     13477021.96
      2493692.55     13477017.62      2492872.26     13476878.74
#Sta/Elev= 30
  4523.3  219.16  4651.1  214.16  4752.8  210.98  4848.4  209.22    4883     207
    4903  206.72  4953.1  201.79  4973.1  201.51  4989.9  199.75  4990.4  199.25
  4996.3  199.75  5033.2  200.47  5223.2  200.53  5237.6  199.96  5323.2  200.29
  5335.6  200.88  5363.6  203.99  5485.3  204.65  5495.4  206.13  5500.8  208.49
  5505.9  208.03  5515.7  209.68  5525.9  209.61  5556.1  203.31  5586.7  202.09
  5621.6  203.93  5627.3  205.93  5745.6   207.9  5920.7  211.83  6167.6  217.87
#Mann= 8 ,-1 , 0
  4523.3    .035       0  4651.1     .12       0  4848.4     .12       0
  4989.9     .05       0  4996.3     .12       0  5237.6     .05       0
  5745.6     .07       0  5920.7     .05       0
Bank Sta=4989.9,4996.3
XS Rating Curve= 0 ,0
Exp/Cntr=0.3,0.1

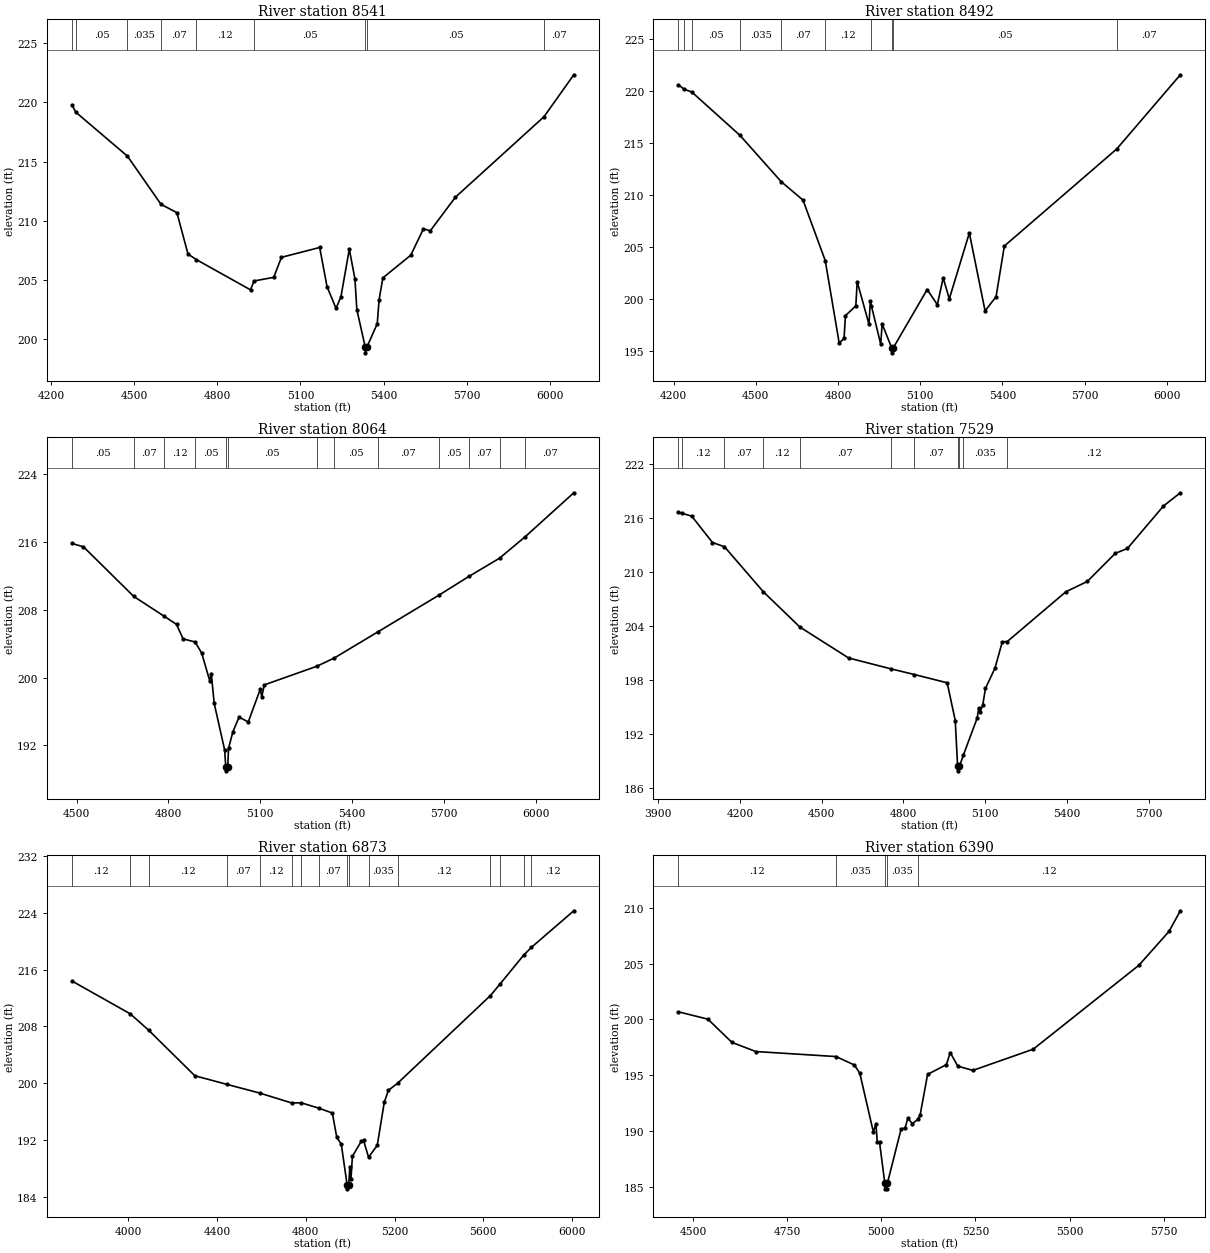
Type RM Length L Ch R = 1 ,8541    ,49,49,49
BEGIN DESCRIPTION:
Mapping XS 92f0df40
END DESCRIPTION:
XS GIS Cut Line= 6
      2494492.75     13476775.65      2493909.02     13476725.74
      2493850.43     13476740.93      2493737.58     13476799.53
      2493603.03      13476764.8      2492711.11     13476651.96
#Sta/Elev= 30
  4275.1   219.8  4288.9  219.18  4475.3  215.47  4596.5   211.4    4654  210.69
  4694.1  207.19    4724  206.73  4919.7  204.17  4932.3  204.92  5003.6  205.23
  5031.4  206.92  5169.4  207.75  5195.8  204.45  5228.5   202.6  5246.2   203.6
  5276.4  207.61  5296.6  205.09  5303.6   202.5  5333.7  199.35  5334.2  198.85
  5340.1  199.35  5377.2  201.31  5383.8  203.32  5397.4  205.18  5498.2   207.1
  5544.1  209.33  5568.7  209.16  5659.4     212  5979.3   218.8  6086.7  222.34
#Mann= 9 ,-1 , 0
  4275.1    .035       0  4288.9     .05       0  4475.3    .035       0
  4596.5     .07       0    4724     .12       0  4932.3     .05       0
  5333.7     .05       0  5340.1     .05       0  5979.3     .07       0
Bank Sta=5333.7,5340.1
XS Rating Curve= 0 ,0
Exp/Cntr=0.3,0.1

Type RM Length L Ch R = 1 ,8492    ,428,428,428
BEGIN DESCRIPTION:
Mapping XS c7cbd22b
END DESCRIPTION:
XS GIS Cut Line= 6
      2494547.08     13476725.74      2494026.21     13476671.49
      2493770.13     13476730.08      2493650.78     13476732.25
      2493611.71     13476667.15      2492765.39     13476589.02
#Sta/Elev= 30
  4217.8  220.57  4239.7  220.13  4266.1  219.89  4442.4  215.71  4592.7  211.26
  4672.3  209.49  4753.5  203.67  4804.3  195.75  4822.1  196.18  4827.2  198.38
    4865  199.31  4870.1  201.64  4913.1  197.55  4918.2  199.79    4922  199.31
    4956  195.63  4961.1  197.58  4995.7   195.3  4996.2   194.8  5002.1   195.3
  5125.6  200.89  5162.6  199.43  5183.9  202.01  5206.2  199.99  5279.4  206.33
  5336.8  198.83  5376.9   200.2  5407.1  205.07  5817.1   214.4  6049.4  221.54
#Mann= 10 ,-1 , 0
  4217.8     .05       0  4239.7    .035       0  4266.1     .05       0
  4442.4    .035       0  4592.7     .07       0  4753.5     .12       0
    4922     .05       0  4995.7     .05       0  5002.1     .05       0
  5817.1     .07       0
Bank Sta=4995.7,5002.1
XS Rating Curve= 0 ,0
Exp/Cntr=0.3,0.1

Type RM Length L Ch R = 1 ,8064    ,535,535,535
BEGIN DESCRIPTION:
Mapping XS 13df0e04
END DESCRIPTION:
XS GIS Cut Line= 4
      2494378.53     13476477.78      2493878.53     13476366.67
      2493767.42     13476359.73      2492760.45     13476491.67
#Sta/Elev= 30
    4485   215.8  4522.7   215.4    4687  209.55  4787.1   207.2  4826.7  206.26
  4847.9  204.55  4887.2  204.19  4908.6  202.89    4935  199.62  4940.1  200.47
  4949.6  196.95  4983.7  191.46  4987.3   189.5  4987.8     189  4993.8   189.5
  4996.4  191.65  5010.8  193.62  5030.8  195.33  5060.9  194.76    5100  198.61
    5105  197.74  5113.3  199.13  5284.5  201.32  5341.5  202.29  5483.5  205.36
  5682.5  209.68    5782  211.92  5881.5  214.06  5965.4  216.59  6124.1  221.77
#Mann= 13 ,-1 , 0
    4485     .05       0    4687     .07       0  4787.1     .12       0
  4887.2     .05       0  4987.3     .05       0  4993.8     .05       0
  5284.5     .07       0  5341.5     .05       0  5483.5     .07       0
  5682.5     .05       0    5782     .07       0  5881.5     .12       0
  5965.4     .07       0
Bank Sta=4987.3,4993.8
XS Rating Curve= 0 ,0
Exp/Cntr=0.3,0.1

Type RM Length L Ch R = 1 ,7529    ,656,656,656
BEGIN DESCRIPTION:
Mapping XS 3cf89717
END DESCRIPTION:
XS GIS Cut Line= 4
      2494642.41     13476227.78      2493718.81     13475894.45
      2493559.09     13475915.28      2492885.48     13476102.78
#Sta/Elev= 30
    3974  216.68  3985.6  216.57  4022.7  216.24  4098.8  213.31  4142.8  212.84
  4285.6  207.83  4419.7  203.91  4598.5  200.47  4752.8  199.27    4840  198.63
  4960.4  197.71    4990  193.51  4998.7  188.42  4999.2  187.92  5005.3  188.42
  5020.2   189.7  5070.7  193.81  5075.9  194.88    5081  194.42  5090.9  195.24
  5100.9  197.09  5135.7  199.33  5162.8  202.27    5181   202.3    5396  207.83
  5474.8  208.98  5577.4   212.1    5622  212.65  5754.4  217.37  5816.2  218.84
#Mann= 11 ,-1 , 0
    3974     .07       0  3985.6     .12       0  4142.8     .07       0
  4285.6     .12       0  4419.7     .07       0  4752.8     .12       0
    4840     .07       0  4998.7     .05       0  5005.3     .07       0
  5020.2    .035       0    5181     .12       0
Bank Sta=4998.7,5005.3
XS Rating Curve= 0 ,0
Exp/Cntr=0.3,0.1

Type RM Length L Ch R = 1 ,6873    ,483,483,483
BEGIN DESCRIPTION:
Mapping XS 8438a8da
END DESCRIPTION:
XS GIS Cut Line= 4
      2494781.28     13476068.03      2493927.14     13475373.62
      2493691.03     13475352.78      2492810.41     13475630.14
#Sta/Elev= 30
  3746.5  214.41  4009.3  209.78  4091.6  207.49  4300.3  201.05  4444.4  199.84
  4591.7  198.62    4737  197.21  4779.4  197.24    4858  196.49  4919.7   195.8
  4939.8  192.35  4959.9  191.42  4986.6  185.61  4987.1  185.11  4993.4  185.61
  4998.6  188.24  5003.6  186.44  5010.1  189.69  5050.2  191.83  5060.3  191.95
  5082.9  189.56  5122.1  191.24  5153.6  197.29  5172.1  198.99  5214.3  200.01
  5632.1  212.36  5677.1  214.05  5781.1  218.03  5816.2  219.14  6007.6  224.31
#Mann= 16 ,-1 , 0
  3746.5     .12       0  4009.3     .07       0  4091.6     .12       0
  4444.4     .07       0  4591.7     .12       0    4737     .07       0
  4779.4     .12       0    4858     .07       0  4986.6     .05       0
  4993.4     .07       0  5082.9    .035       0  5214.3     .12       0
  5632.1     .07       0  5677.1     .12       0  5781.1     .07       0
  5816.2     .12       0
Bank Sta=4986.6,4993.4
XS Rating Curve= 0 ,0
Exp/Cntr=0.3,0.1

Type RM Length L Ch R = 1 ,6390    ,936,936,936
BEGIN DESCRIPTION:
TRIB 5 TO PERDIDO CREEK 7.0
END DESCRIPTION:
XS GIS Cut Line= 3
      2494424.97     13475324.98        2494025.       13474975.
      2493225.03       13474925.
#Sta/Elev= 30
  4461.1  200.67  4539.4  200.01    4603  197.93  4666.5  197.11  4879.7  196.66
  4928.5   195.9  4942.7  195.17  4978.8  189.88  4985.5  190.63  4989.2  188.99
  4995.1  188.99  5009.2   185.3  5009.7   184.8  5015.5   184.8    5016   185.3
  5052.7  190.19  5062.7  190.23  5070.2  191.11  5082.7  190.64  5096.2  191.02
  5102.8  191.39  5122.8  195.06  5172.9  195.94  5182.9  197.02    5203   195.8
  5243.1  195.42  5403.4  197.32  5683.9  204.84  5764.1  207.88  5794.1  209.73
#Mann= 5 ,-1 , 0
  4461.1     .12       0  4879.7    .035       0  5009.2    .035       0
    5016    .035       0  5096.2     .12       0
Bank Sta=5009.2,5016
XS Rating Curve= 0 ,0
Exp/Cntr=0.3,0.1