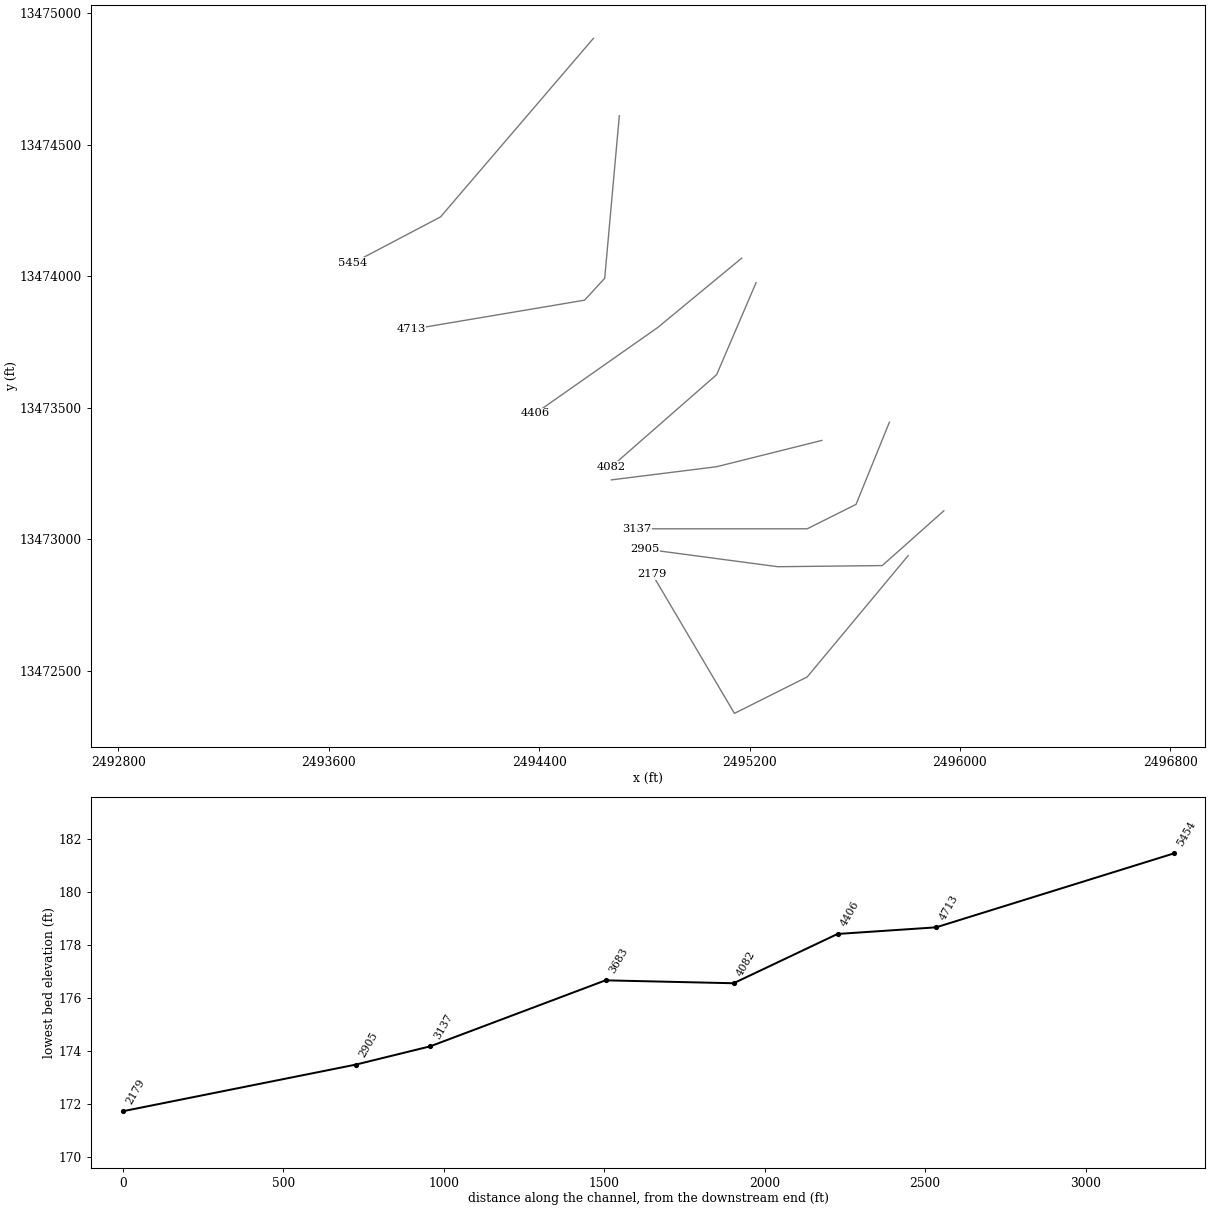
HEC-RAS study TRIB 5 TO PERDIDO CREEK.prj: TRIB 5 TO PERDIDO CREEK Base Level Engineering

--- TRIB 5 TO PERDIDO CREEK.g01 (geometry) --- (continued)

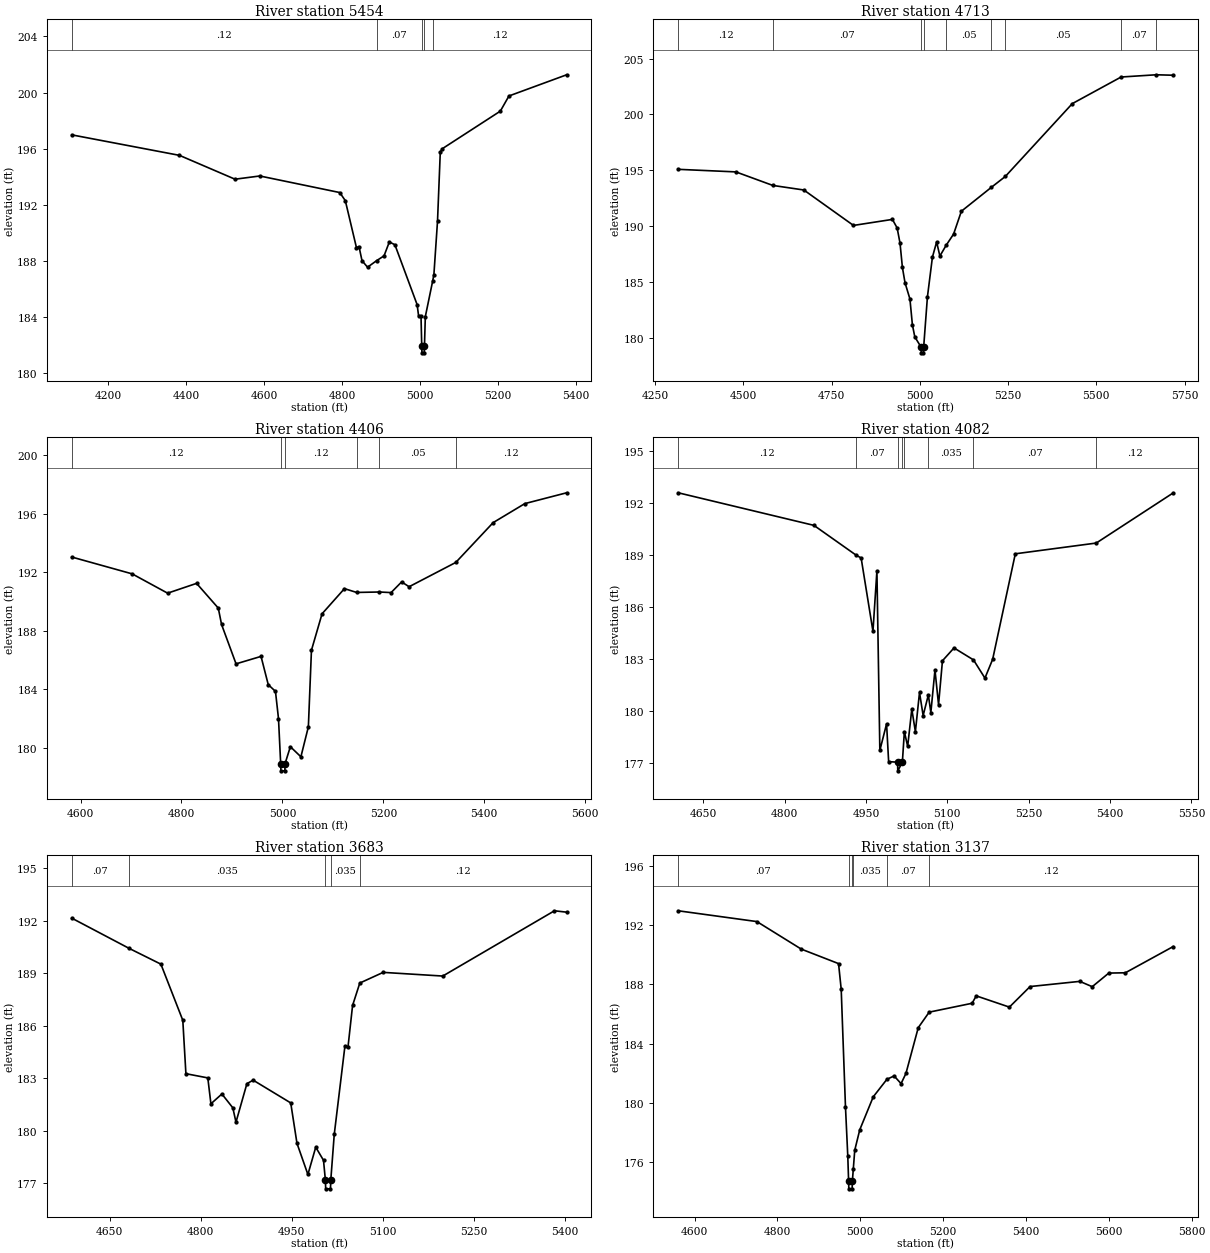
Type RM Length L Ch R = 1 ,5454    ,741,741,741
BEGIN DESCRIPTION:
TRIB 5 TO PERDIDO CREEK 6.0
END DESCRIPTION:
XS GIS Cut Line= 3
      2494606.46     13474904.09        2494025.       13474225.
      2493691.56     13474049.52
#Sta/Elev= 30
  4105.6  196.99  4382.2  195.53  4524.9  193.83  4588.5  194.06  4793.8  192.88
  4808.1   192.3  4836.6  188.96  4843.2  189.03  4850.9  188.03  4865.1  187.56
  4888.6  188.03  4907.5  188.37  4921.1  189.36  4935.4  189.16  4992.5  184.89
  4996.3  184.07  5002.4  184.07  5004.3  181.96  5004.8  181.46  5010.8  181.46
  5011.3  181.96  5013.5  184.04  5032.3  186.57  5035.5  187.03  5044.8  190.84
  5051.9  195.76  5057.5  196.01  5206.1  198.68  5228.2  199.76  5376.4  201.27
#Mann= 5 ,-1 , 0
  4105.6     .12       0  4888.6     .07       0  5004.3     .05       0
  5011.3     .07       0  5032.3     .12       0
Bank Sta=5004.3,5011.3
XS Rating Curve= 0 ,0
Exp/Cntr=0.3,0.1

Type RM Length L Ch R = 1 ,4713    ,307,307,307
BEGIN DESCRIPTION:
Mapping XS 2f091a22
END DESCRIPTION:
XS GIS Cut Line= 4
      2494704.92     13474609.69      2494649.36     13473991.67
      2494572.97     13473908.34      2493913.23     13473797.22
#Sta/Elev= 30
    4315  195.09  4478.5  194.86    4583  193.65  4671.1  193.24  4811.7  190.07
  4922.1  190.61  4935.5  189.84  4943.6  188.49  4950.4  186.31  4957.8  184.94
  4971.7  183.49  4978.7  181.18  4985.5   180.1  5003.5  179.17    5004  178.67
  5010.1  178.67  5010.6  179.17  5021.3  183.68  5035.5  187.24  5047.4  188.59
  5056.6  187.33  5074.1  188.28  5095.5   189.3  5117.5  191.34  5202.1  193.47
    5242  194.45  5431.9  200.97  5570.2  203.35  5669.4  203.55  5717.6  203.51
#Mann= 9 ,-1 , 0
    4315     .12       0    4583     .07       0  5003.5     .05       0
  5010.6     .07       0  5074.1     .05       0  5202.1     .07       0
    5242     .05       0  5570.2     .07       0  5669.4     .05       0
Bank Sta=5003.5,5010.6
XS Rating Curve= 0 ,0
Exp/Cntr=0.3,0.1

Type RM Length L Ch R = 1 ,4406    ,324,324,324
BEGIN DESCRIPTION:
Mapping XS 5663e9eb
END DESCRIPTION:
XS GIS Cut Line= 3
      2495170.16     13474068.03      2494850.75     13473804.17
      2494387.06      13473478.9
#Sta/Elev= 30
  4582.6  193.03  4702.3  191.88  4772.6  190.56    4830  191.23    4873  189.54
  4879.5  188.42  4908.2  185.73  4957.7  186.24    4972  184.31  4986.3  183.85
  4992.3  181.99  4996.6  178.92  4997.1  178.42  5004.9  178.42  5005.4  178.92
  5015.8  180.07  5036.7  179.38  5051.5  181.43  5057.6  186.66  5078.6  189.15
    5123  190.87  5147.1  190.61  5192.4  190.64  5215.4   190.6  5236.3  191.33
  5251.1     191  5343.6  192.66  5417.6  195.38  5480.4  196.68  5563.3  197.42
#Mann= 6 ,-1 , 0
  4582.6     .12       0  4996.6     .05       0  5005.4     .12       0
  5147.1     .07       0  5192.4     .05       0  5343.6     .12       0
Bank Sta=4996.6,5005.4
XS Rating Curve= 0 ,0
Exp/Cntr=0.3,0.1

Type RM Length L Ch R = 1 ,4082    ,399,399,399
BEGIN DESCRIPTION:
TRIB 5 TO PERDIDO CREEK 3.0
END DESCRIPTION:
XS GIS Cut Line= 3
      2495224.99     13473974.98        2495075.       13473625.
      2494674.98     13473274.98
#Sta/Elev= 30
    4604   192.6  4854.2  190.72  4932.5  188.99  4941.2  188.84    4963  184.61
  4970.3   188.1  4975.7  177.74  4988.1  179.27  4991.9  177.09  5008.3  177.06
  5008.8  176.56  5017.2  177.06  5020.9  178.82    5027  177.97  5034.6  180.12
  5041.2  178.82  5048.8  181.08  5055.5  179.75  5065.1  180.94  5069.7  179.92
  5077.3  182.38  5083.9  180.38  5091.1  182.91  5112.4  183.65  5148.3  182.96
  5169.4  181.91  5183.6  182.99  5225.4  189.08  5374.6   189.7  5516.3  192.59
#Mann= 8 ,-1 , 0
    4604     .12       0  4932.5     .07       0  5008.3     .05       0
  5017.2     .07       0  5020.9     .12       0  5065.1    .035       0
  5148.3     .07       0  5374.6     .12       0
Bank Sta=5008.3,5017.2
XS Rating Curve= 0 ,0
Exp/Cntr=0.3,0.1

Type RM Length L Ch R = 1 ,3683    ,546,546,546
BEGIN DESCRIPTION:
TRIB 5 TO PERDIDO CREEK 2.0
END DESCRIPTION:
XS GIS Cut Line= 3
        2495475.       13473375.        2495075.       13473275.
      2494675.02       13473225.
#Sta/Elev= 30
  4587.4  192.14  4681.5  190.42  4734.3  189.51  4770.4   186.3  4775.5  183.25
  4811.6  183.01  4816.7  181.53  4834.8  182.09  4852.8   181.3    4858  180.48
    4876  182.68  4886.3  182.88  4948.2  181.58  4958.5  179.27  4976.5  177.49
  4989.4  179.05  5002.2   178.3  5005.3  177.17  5005.8  176.67  5013.7  176.67
  5014.2  177.17  5019.9  179.78  5037.5  184.83  5042.5  184.76  5050.1  187.15
    5062  188.43  5100.5  189.04  5198.7  188.83  5382.7  192.56  5402.8  192.48
#Mann= 5 ,-1 , 0
  4587.4     .07       0  4681.5    .035       0  5005.3    .035       0
  5014.2    .035       0    5062     .12       0
Bank Sta=5005.3,5014.2
XS Rating Curve= 0 ,0
Exp/Cntr=0.3,0.1

Type RM Length L Ch R = 1 ,3137    ,232,232,232
BEGIN DESCRIPTION:
Mapping XS f9ebc841
END DESCRIPTION:
XS GIS Cut Line= 4
      2495732.11     13473444.44      2495605.19      13473131.8
      2495419.45     13473038.93      2494769.73     13473038.93
#Sta/Elev= 30
  4560.5  192.97  4750.5  192.24  4857.6  190.38  4947.6   189.4    4954  187.67
  4964.3  179.73  4969.9  176.39  4971.9  174.68  4972.4  174.18  4980.4  174.18
  4980.9  174.68  4983.3  175.55  4986.7  176.79  4998.8  178.17  5031.4   180.4
  5064.3  181.58  5081.7  181.81  5098.5  181.29  5110.3  181.98    5140  185.07
  5166.4  186.12    5270  186.72    5280  187.22    5360  186.46    5410  187.85
    5530   188.2    5560  187.84    5600  188.76    5640  188.78  5755.3  190.55
#Mann= 6 ,-1 , 0
  4560.5     .07       0  4971.9    .035       0  4980.9     .07       0
  4983.3    .035       0  5064.3     .07       0  5166.4     .12       0
Bank Sta=4971.9,4980.9
XS Rating Curve= 0 ,0
Exp/Cntr=0.3,0.1

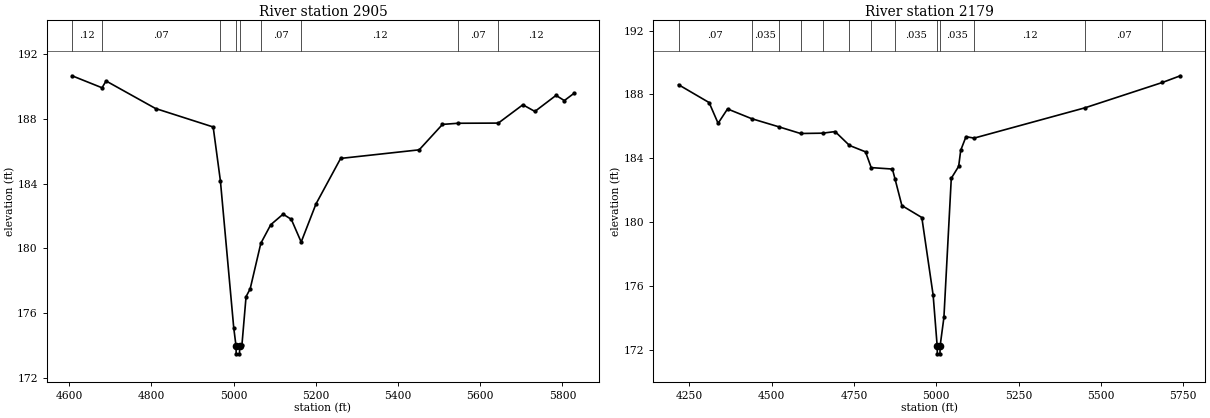
Type RM Length L Ch R = 1 ,2905    ,726,726,726
BEGIN DESCRIPTION:
Mapping XS 9d4a4531
END DESCRIPTION:
XS GIS Cut Line= 4
      2495939.14     13473107.35       2495704.8     13472899.05
      2495307.66     13472894.71      2494802.02     13472961.98
#Sta/Elev= 30
  4607.1  190.65    4680  189.91  4689.8  190.33  4810.2  188.63  4950.4  187.49
    4968  184.16  5000.4   175.1  5005.9  173.99  5006.4  173.49  5014.4  173.49
  5014.9  173.99  5020.4  174.05  5030.4  177.02  5040.4   177.5  5066.3  180.31
  5090.5  181.46  5120.5  182.11  5140.5  181.79  5164.5  180.39  5200.5  182.74
  5260.5  185.55  5451.6  186.08  5508.3  187.65  5546.3  187.72  5644.1  187.73
  5703.8  188.86  5733.1  188.45  5784.5  189.44  5804.7  189.12  5827.9  189.56
#Mann= 9 ,-1 , 0
  4607.1     .12       0    4680     .07       0    4968    .035       0
  5005.9    .035       0  5014.9    .035       0  5066.3     .07       0
  5164.5     .12       0  5546.3     .07       0  5644.1     .12       0
Bank Sta=5005.9,5014.9
XS Rating Curve= 0 ,0
Exp/Cntr=0.3,0.1

Type RM Length L Ch R = 1 ,2179    ,0,0,0
BEGIN DESCRIPTION:
Mapping XS d280c068
END DESCRIPTION:
XS GIS Cut Line= 4
       2495803.3     13472936.77      2495419.45     13472475.53
      2495142.73     13472336.98      2494829.97     13472866.59
#Sta/Elev= 30
    4217  188.61  4309.9  187.49  4337.2  186.19  4365.9  187.09  4439.1  186.48
  4523.2  185.96  4587.7  185.55  4654.6  185.57  4692.7  185.67  4736.4   184.8
  4785.1   184.4  4802.4  183.41  4866.8  183.32    4875  182.68  4895.6  181.03
  4956.2  180.28  4990.6  175.41  5002.8  172.23  5003.3  171.73  5011.3  171.73
  5011.8  172.23  5023.3  174.01  5045.7  182.74  5068.1  183.49  5074.4   184.5
  5090.4  185.35    5115  185.26  5451.7  187.16    5687  188.75  5741.6  189.17
#Mann= 13 ,-1 , 0
    4217     .07       0  4439.1    .035       0  4523.2     .12       0
  4587.7    .035       0  4654.6     .12       0  4736.4    .035       0
  4802.4     .12       0    4875    .035       0  5002.8    .035       0
  5011.8    .035       0    5115     .12       0  5451.7     .07       0
    5687     .12       0
Bank Sta=5002.8,5011.8
XS Rating Curve= 0 ,0
Exp/Cntr=0.3,0.1

Chan Stop Cuts=-1
Use User Specified Reach Order=0
Composite Channel Slope=5