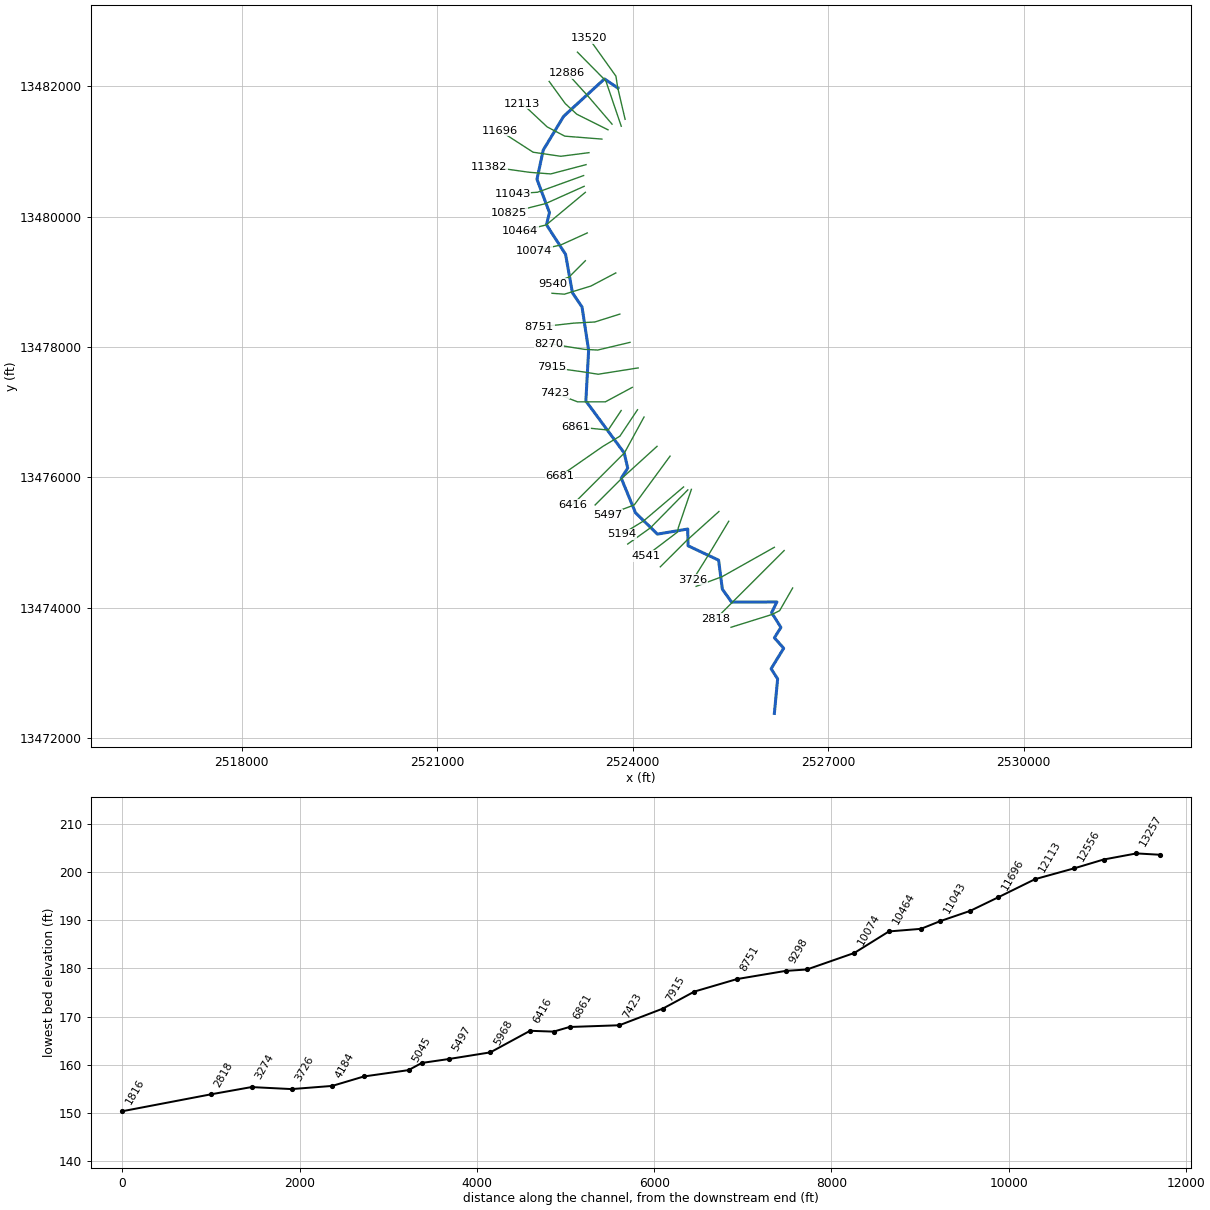
--- TRIB 5 TO TURKEY CREEK.prj (project) ---

Proj Title=TRIB 5 TO TURKEY CREEK Base Level Engineering
Current Plan=p01
Default Exp/Contr=0.3,0.1
English Units
Geom File=g01
Flow File=f01
Plan File=p01
Y Axis Title=Elevation
X Axis Title(PF)=Main Channel Distance
X Axis Title(XS)=Station
BEGIN DESCRIPTION:
TRIB 5 TO TURKEY CREEK
END DESCRIPTION:
DSS Export Rating Curves= 0
DSS Export Rating Curve Sorted= 0
DSS Export Volume Flow Curves= 0
DXF OffsetX= 0
DXF OffsetY= 0
DXF ScaleX= 1
DXF ScaleY= 10

--- TRIB 5 TO TURKEY CREEK.p01 (plan) ---

Plan Title=Multiple Run
Short Identifier=Multiple
Geom File=g01
Flow File=f01
Subcritical Flow
K Sum by GR= 0
Std Step Tol= 0.01
Critical Tol= 0.01
Num of Std Step Trials= 20
Max Error Tol= 0.3
Flow Tol Ratio= 0.001
Split Flow NTrial= 30
Split Flow Tol= 0.02
Split Flow Ratio= 0.02
Log Output Level= 0
Friction Slope Method= 1
Unsteady Friction Slope Method= 2
Unsteady Bridges Friction Slope Method= 1
Parabolic Critical Depth
Global Vel Dist=  1 , 1 , 1
Global Log Level= 0
CheckData=True
Encroach Param= -1, 0, 0, 0
BEGIN DESCRIPTION:
Multiple Run
END DESCRIPTION:

--- TRIB 5 TO TURKEY CREEK.f01 (steady flow) ---

Flow Title=Multiple
Number of Profiles=7
Profile Names=10-year,25-year,50-year,1pct_min,100-year,1pct_plu,500-year
River Rch & RM= TRIB 5 TO TURKEY,Reach-1,13520
     347     533     692     436     870    1735    1357
River Rch & RM= TRIB 5 TO TURKEY,Reach-1,9540
     674    1076    1435     926    1848    3687    3030
River Rch & RM= TRIB 5 TO TURKEY,Reach-1,6416
     968    1573    2121    1382    2758    5503    4612
Boundary for River Rch & Prof#=TRIB 5 TO TURKEY,Reach-1,1
Up Type=0
Dn Type=3
Dn Slope=0.005
Boundary for River Rch & Prof#=TRIB 5 TO TURKEY,Reach-1,2
Up Type=0
Dn Type=3
Dn Slope=0.005
Boundary for River Rch & Prof#=TRIB 5 TO TURKEY,Reach-1,3
Up Type=0
Dn Type=3
Dn Slope=0.005
Boundary for River Rch & Prof#=TRIB 5 TO TURKEY,Reach-1,4
Up Type=0
Dn Type=3
Dn Slope=0.005
Boundary for River Rch & Prof#=TRIB 5 TO TURKEY,Reach-1,5
Up Type=0
Dn Type=3
Dn Slope=0.005
Boundary for River Rch & Prof#=TRIB 5 TO TURKEY,Reach-1,6
Up Type=0
Dn Type=3
Dn Slope=0.005
Boundary for River Rch & Prof#=TRIB 5 TO TURKEY,Reach-1,7
Up Type=0
Dn Type=3
Dn Slope=0.005

--- TRIB 5 TO TURKEY CREEK.g01 (geometry) ---

Geom Title=Existing Conditions
Program Version=4.10

River Reach=TRIB 5 TO TURKEY,Reach-1
Reach XY= 30
        2523775.       13481975.      2523568.05     13482116.16
      2522941.63     13481541.71      2522628.55     13481023.53
      2522532.56       13480575.      2522724.23     13480064.31
      2522678.67     13479876.58      2522971.17     13479423.42
      2523077.07     13478830.86      2523223.92     13478614.46
      2523325.21     13477950.09      2523282.81     13477171.59
      2523871.24     13476373.44      2523925.04     13476140.34
       2523825.7      13475985.7      2524044.61     13475454.84
      2524380.86     13475127.05      2524845.76     13475205.56
      2524851.15     13474948.13      2525319.18     13474727.31
      2525377.24     13474280.93      2525518.93     13474083.13
      2526214.05     13474085.49      2526132.78      13473921.6
       2526275.4     13473695.13      2526175.55     13473535.64
      2526317.92       13473375.      2526125.02     13473059.59
      2526225.21     13472904.95        2526175.       13472375.

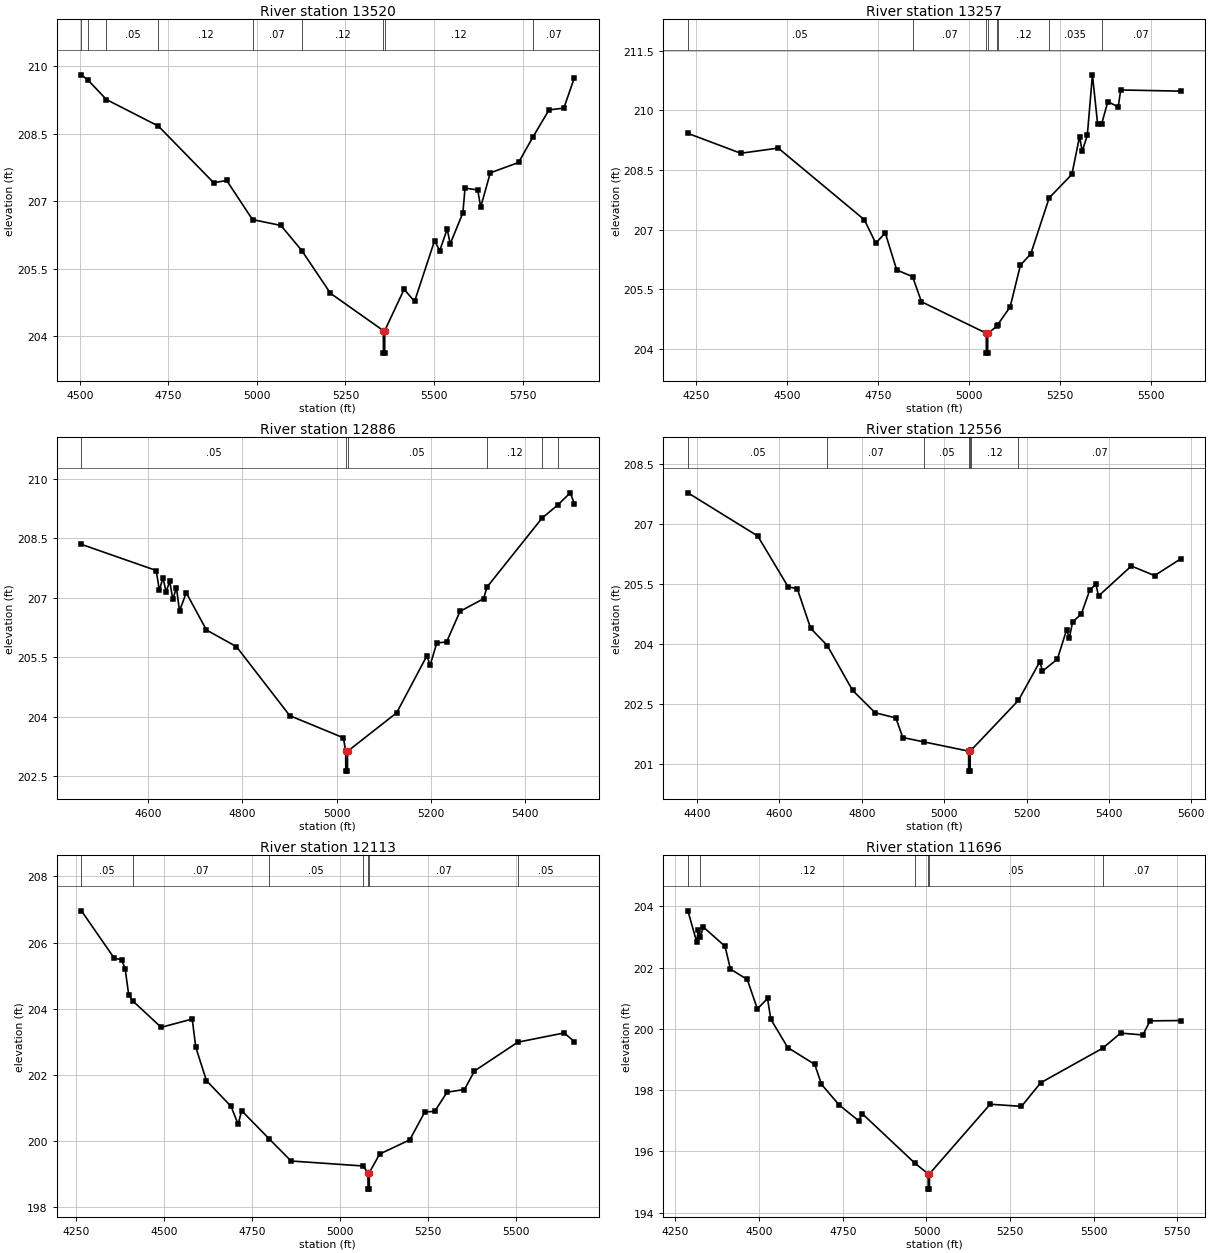
Type RM Length L Ch R = 1 ,13520   ,263,263,263
BEGIN DESCRIPTION:
TRIB 5 TO TURKEY CREEK 27.0
END DESCRIPTION:
XS GIS Cut Line= 4
      2523884.95     13481495.81        2523772.     13481978.06
      2523743.84     13482158.76      2523329.55     13482739.31
#Sta/Elev= 30
  4504.7  209.81  4523.6  209.69  4575.3  209.26  4721.9  208.67    4878  207.41
  4914.7  207.46  4987.7  206.59  5067.8  206.46  5126.9   205.9  5207.8  204.95
    5357  204.12  5357.3  203.62  5360.8  203.62    5361  204.12  5415.6  205.04
  5445.1  204.77  5501.6  206.12  5516.3   205.9  5537.2  206.38  5545.8  206.05
  5581.5  206.74  5587.6  207.29  5623.3  207.25  5631.9  206.87  5658.9  207.63
  5738.8  207.86  5779.4  208.43  5824.8  209.03  5866.6  209.07  5896.1  209.74
#Mann= 9 ,-1 , 0
  4504.7     .05       0  4523.6    .035       0  4575.3     .05       0
  4721.9     .12       0  4987.7     .07       0  5126.9     .12       0
    5357     .05       0    5361     .12       0  5779.4     .07       0
Bank Sta=5357,5361
XS Rating Curve= 0 ,0
Exp/Cntr=0.3,0.1

Type RM Length L Ch R = 1 ,13257   ,371,371,371
BEGIN DESCRIPTION:
Mapping XS 2e9d579d
END DESCRIPTION:
XS GIS Cut Line= 3
      2523825.86     13481389.77      2523589.32     13482085.84
      2523153.67     13482527.17
#Sta/Elev= 30
    4227  209.42  4372.3  208.92  4475.4  209.05  4712.2  207.25  4743.6  206.66
  4769.7  206.92  4801.1  205.99  4844.9  205.82  4869.2  205.19  5047.5   204.4
  5047.7   203.9  5051.2   203.9  5051.5   204.4  5076.4  204.57  5078.5  204.61
  5113.1  205.06  5141.4  206.11  5169.7  206.39  5220.5   207.8  5282.9  208.39
    5304  209.34  5311.2  208.97  5325.3  209.37  5339.4  210.89  5353.6  209.66
  5364.5  209.65  5381.9  210.22  5410.2  210.08  5417.2  210.51  5582.3  210.48
#Mann= 8 ,-1 , 0
    4227     .05       0  4844.9     .07       0  5047.5     .05       0
  5051.5     .07       0  5076.4    .035       0  5078.5     .12       0
  5220.5    .035       0  5364.5     .07       0
Bank Sta=5047.5,5051.5
XS Rating Curve= 0 ,0
Exp/Cntr=0.3,0.1

Type RM Length L Ch R = 1 ,12886   ,330,330,330
BEGIN DESCRIPTION:
Mapping XS a4ecd07a
END DESCRIPTION:
XS GIS Cut Line= 3
      2523685.05     13481421.51       2523330.9     13481834.69
      2522994.07     13482206.25
#Sta/Elev= 30
  4458.5  208.35  4617.2  207.69  4623.8  207.19  4631.5  207.51  4638.1  207.15
  4645.8  207.42  4652.4  206.96    4660  207.26  4666.6  206.67  4680.9  207.13
  4723.7  206.19  4787.4  205.77  4900.4  204.03  5014.4  203.47  5019.1  203.13
  5019.4  202.63  5022.9  202.63  5023.1  203.13  5127.2   204.1  5191.5  205.54
  5198.2   205.3  5212.4  205.86  5233.3  205.89  5261.7  206.66  5311.8  206.98
  5318.8  207.27  5435.6  209.01  5469.8  209.35  5495.6  209.65  5504.2  209.38
#Mann= 6 ,-1 , 0
  4458.5     .05       0  5019.1     .05       0  5023.1     .05       0
  5318.8     .12       0  5435.6     .07       0  5469.8     .12       0
Bank Sta=5019.1,5023.1
XS Rating Curve= 0 ,0
Exp/Cntr=0.3,0.1

Type RM Length L Ch R = 1 ,12556   ,443,443,443
BEGIN DESCRIPTION:
Mapping XS bd932cd2
END DESCRIPTION:
XS GIS Cut Line= 4
      2523622.58     13481334.68       2523143.4     13481574.27
      2522966.32     13481737.46      2522719.88     13482077.62
#Sta/Elev= 30
  4377.9  207.77  4547.4  206.69  4621.2  205.42  4643.5  205.37    4676  204.38
  4716.3  203.95  4777.7  202.83  4832.5  202.27  4882.8  202.14  4899.6  201.65
  4951.3  201.54  5059.4  201.31  5059.6  200.81  5063.1  200.81  5063.4  201.31
  5066.1  201.34  5180.4  202.58  5232.5  203.55  5238.7  203.31  5274.9  203.61
  5297.5  204.35  5303.7  204.13  5311.9  204.54  5333.1  204.74  5353.9  205.35
  5368.6  205.48  5374.8  205.19  5454.5  205.94  5510.9   205.7  5574.5  206.12
#Mann= 7 ,-1 , 0
  4377.9     .05       0  4716.3     .07       0  4951.3     .05       0
  5059.4     .05       0  5063.4     .05       0  5066.1     .12       0
  5180.4     .07       0
Bank Sta=5059.4,5063.4
XS Rating Curve= 0 ,0
Exp/Cntr=0.3,0.1

Type RM Length L Ch R = 1 ,12113   ,417,417,417
BEGIN DESCRIPTION:
Mapping XS 3a8e403d
END DESCRIPTION:
XS GIS Cut Line= 4
       2523528.8     13481192.33      2522959.37     13481237.46
      2522688.54     13481379.83      2522306.62     13481737.44
#Sta/Elev= 30
  4264.6  206.96  4357.7  205.53  4378.8  205.48  4388.8  205.21  4398.8  204.43
  4410.1  204.24  4491.2  203.44  4579.4  203.69  4589.4  202.84  4619.7  201.83
  4689.7  201.05  4709.8  200.51  4719.8  200.92  4797.9  200.07  4860.2   199.4
  5064.5  199.25  5078.7  199.05  5078.9  198.55  5082.4  198.55  5082.7  199.05
  5111.9  199.61  5197.6  200.04  5240.1  200.88  5268.4   200.9  5303.6  201.48
  5352.9  201.56  5381.3  202.12  5504.3  202.99  5636.2  203.27    5665  203.01
#Mann= 7 ,-1 , 0
  4264.6     .05       0  4410.1     .07       0  4797.9     .05       0
  5064.5     .07       0  5078.7     .05       0  5082.7     .07       0
  5504.3     .05       0
Bank Sta=5078.7,5082.7
XS Rating Curve= 0 ,0
Exp/Cntr=0.3,0.1

Type RM Length L Ch R = 1 ,11696   ,314,314,314
BEGIN DESCRIPTION:
Mapping XS 4dede096
END DESCRIPTION:
XS GIS Cut Line= 4
      2523330.93       13480984.      2522896.87     13480928.44
      2522473.26     13480990.94      2521963.46      13481320.4
#Sta/Elev= 30
  4287.2  203.85  4313.3  202.84  4318.5  203.23  4324.4  203.01  4333.5  203.32
  4398.2  202.69  4414.2  201.95  4464.6  201.61  4494.8  200.65  4525.1  200.99
  4535.1  200.31  4585.5  199.39  4666.2  198.84  4686.4  198.19  4738.7  197.52
  4797.5     197  4808.3  197.23  4966.1  195.61  5005.1  195.27  5005.4  194.77
  5008.9  194.77  5009.1  195.27  5190.4  197.54    5284  197.47  5341.4  198.24
    5527  199.37  5580.3  199.86  5646.9   199.8    5668  200.26    5760  200.27
#Mann= 6 ,-1 , 0
  4287.2     .07       0  4324.4     .12       0  4966.1     .05       0
  5005.1     .05       0  5009.1     .05       0    5527     .07       0
Bank Sta=5005.1,5009.1
XS Rating Curve= 0 ,0
Exp/Cntr=0.3,0.1

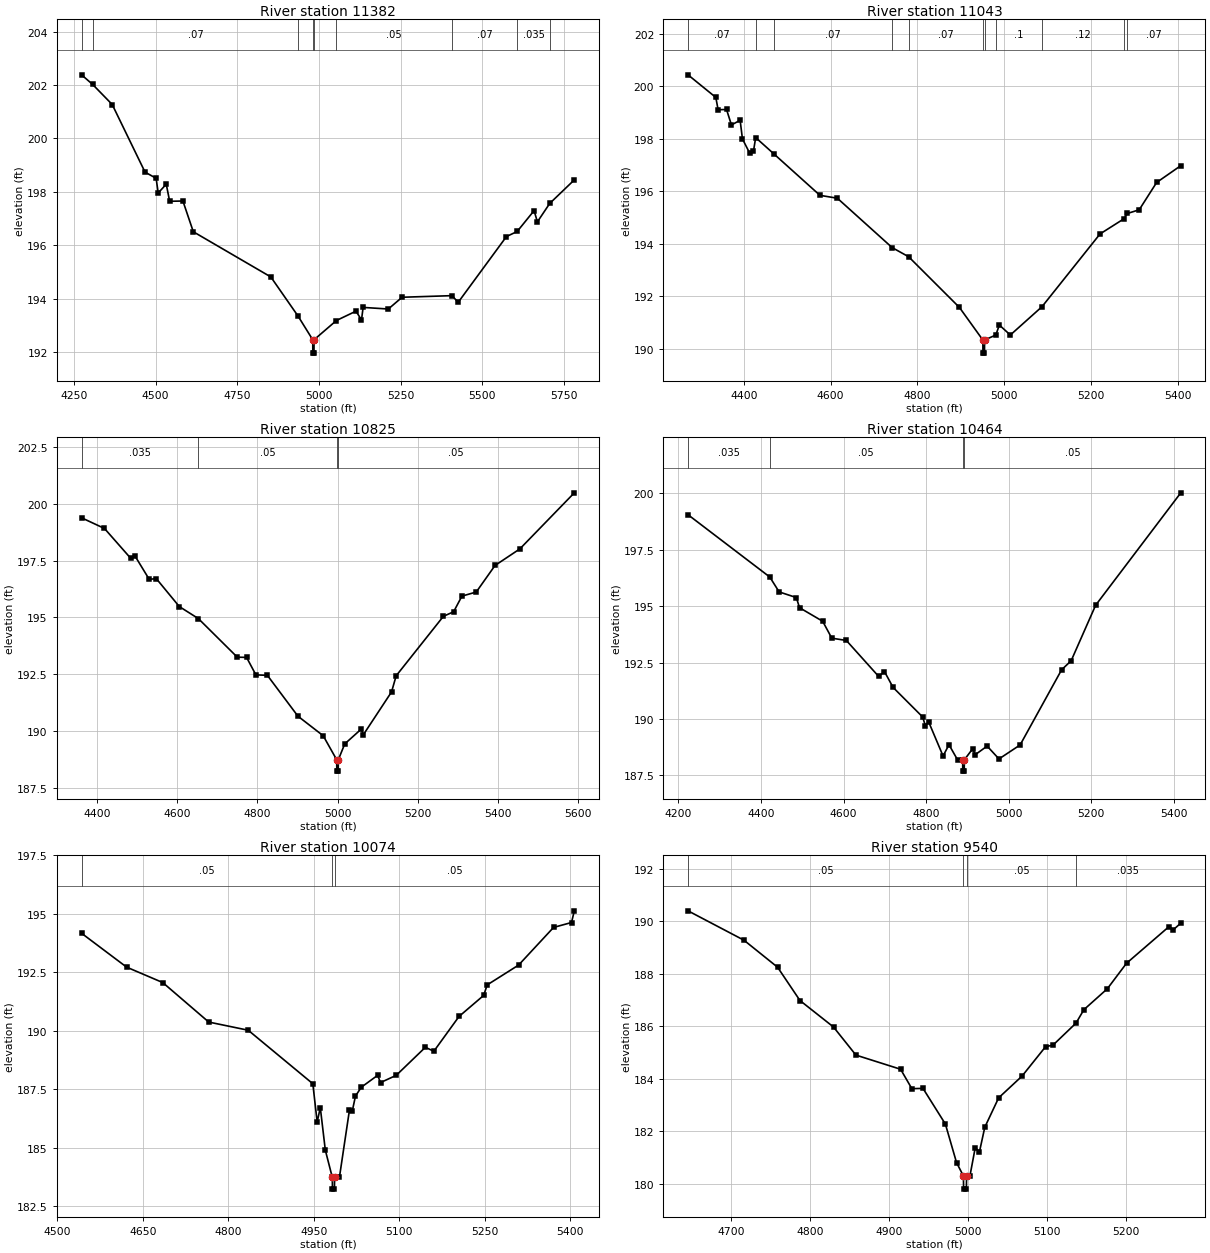
Type RM Length L Ch R = 1 ,11382   ,339,339,339
BEGIN DESCRIPTION:
Mapping XS c23bb084
END DESCRIPTION:
XS GIS Cut Line= 4
      2523285.72     13480799.95       2522744.1      13480657.6
      2522421.18     13480681.91      2521803.09     13480768.72
#Sta/Elev= 30
  4273.5  202.38  4307.5  202.02  4367.3  201.27  4467.8  198.74  4501.7  198.51
  4508.1  197.96  4532.7  198.29  4543.1  197.65  4583.7  197.66  4615.5  196.51
  4852.7  194.82  4935.8  193.36    4981  192.47  4981.3  191.97  4984.8  191.97
    4985  192.47  5053.5  193.19  5113.4  193.54  5130.2  193.21  5135.2  193.68
  5212.3  193.62  5254.5  194.06  5407.3  194.12  5426.1  193.87  5573.8  196.33
  5606.6  196.52  5658.4   197.3  5668.5  196.88  5706.3  197.57  5781.5  198.45
#Mann= 9 ,-1 , 0
  4273.5     .12       0  4307.5     .07       0  4935.8      .1       0
    4981     .05       0    4985      .1       0  5053.5     .05       0
  5407.3     .07       0  5606.6    .035       0  5706.3     .12       0
Bank Sta=4981,4985
XS Rating Curve= 0 ,0
Exp/Cntr=0.3,0.1

Type RM Length L Ch R = 1 ,11043   ,218,218,218
BEGIN DESCRIPTION:
Mapping XS 4c2f3011
END DESCRIPTION:
XS GIS Cut Line= 3
      2523248.39     13480632.45      2522540.92     13480376.37
      2522159.49     13480350.36
#Sta/Elev= 30
  4271.7  200.43  4335.7  199.57    4341   199.1  4360.4  199.11  4371.7  198.52
  4391.7   198.7    4397  197.99  4413.6  197.45  4422.3  197.51  4427.5  198.04
  4469.3  197.42  4575.5  195.84  4615.6  195.73  4741.7  193.85  4779.8   193.5
  4896.7  191.57  4950.6  190.33  4950.9  189.83  4954.4  189.83  4954.6  190.33
  4980.5  190.52  4988.6   190.9  5013.9  190.52  5086.9   191.6  5220.5  194.37
  5274.9  194.94  5283.6  195.15  5310.7  195.29  5350.8  196.33  5406.4  196.97
#Mann= 11 ,-1 , 0
  4271.7     .07       0  4427.5    .035       0  4469.3     .07       0
  4741.7    .035       0  4779.8     .07       0  4950.6     .05       0
  4954.6     .07       0  4980.5      .1       0  5086.9     .12       0
  5274.9     .05       0  5283.6     .07       0
Bank Sta=4950.6,4954.6
XS Rating Curve= 0 ,0
Exp/Cntr=0.3,0.1

Type RM Length L Ch R = 1 ,10825   ,361,361,361
BEGIN DESCRIPTION:
Mapping XS 86a06a8c
END DESCRIPTION:
XS GIS Cut Line= 3
      2523257.07     13480467.51      2522666.78     13480202.76
      2522103.49     13480059.77
#Sta/Elev= 30
  4361.8  199.39  4418.9  198.92  4484.6   197.6  4495.6  197.69  4530.4  196.68
  4548.1  196.71  4605.4  195.48  4652.9  194.95  4749.9  193.25  4773.1  193.24
  4796.3  192.47  4824.9  192.45  4901.1  190.65    4964  189.79  4997.7  188.73
    4998  188.23  5001.5  188.23  5001.7  188.73  5017.8  189.43  5058.8  190.08
    5064  189.83  5134.4  191.72  5145.9  192.43  5263.6  195.05  5289.1  195.25
  5309.8  195.94  5345.5  196.12  5392.3  197.29  5454.2  198.02  5589.9  200.49
#Mann= 4 ,-1 , 0
  4361.8    .035       0  4652.9     .05       0  4997.7     .05       0
  5001.7     .05       0
Bank Sta=4997.7,5001.7
XS Rating Curve= 0 ,0
Exp/Cntr=0.3,0.1

Type RM Length L Ch R = 1 ,10464   ,390,390,390
BEGIN DESCRIPTION:
TRIB 5 TO TURKEY CREEK 22.0
END DESCRIPTION:
XS GIS Cut Line= 3
      2523275.03     13480375.02        2522675.       13479875.
      2522274.97     13479774.99
#Sta/Elev= 30
  4223.2  199.05  4421.2  196.29  4443.9  195.63  4485.5  195.38  4493.3  194.93
  4549.3  194.33  4571.4  193.58  4606.6  193.48  4684.7  191.89    4699   192.1
  4719.8   191.4  4791.4  190.09  4797.9  189.71  4805.8  189.88  4840.9  188.36
  4855.2  188.86    4876  188.19  4888.4  188.19  4888.6  187.69  4892.1  187.69
  4892.4  188.19  4912.5  188.68    4919  188.42  4947.6   188.8  4976.3  188.23
  5027.5  188.85    5128  192.18  5151.1  192.58  5210.4  195.04  5416.6  200.02
#Mann= 4 ,-1 , 0
  4223.2    .035       0  4421.2     .05       0  4888.4     .05       0
  4892.4     .05       0
Bank Sta=4888.4,4892.4
XS Rating Curve= 0 ,0
Exp/Cntr=0.3,0.1

Type RM Length L Ch R = 1 ,10074   ,534,534,534
BEGIN DESCRIPTION:
Mapping XS af647b77
END DESCRIPTION:
XS GIS Cut Line= 3
      2523304.78     13479751.35      2522892.48     13479564.73
      2522489.46     13479478.06
#Sta/Elev= 30
  4542.4  194.17  4621.5  192.72  4684.9  192.06  4765.6  190.37  4834.9  190.02
  4948.3  187.73  4955.9  186.09  4961.4  186.71  4970.2  184.89  4982.5  183.72
  4982.7  183.22  4986.2  183.22  4986.5  183.72    4995  183.73  5012.6  186.61
  5017.7  186.58  5023.1   187.2  5033.3  187.58    5062  188.09  5067.1  187.78
  5094.7  188.09  5145.8  189.29  5160.7  189.12  5204.9  190.61  5248.1  191.51
  5254.3  191.96  5309.5  192.81  5370.8  194.42  5402.3  194.63  5407.2  195.13
#Mann= 3 ,-1 , 0
  4542.4     .05       0  4982.5     .05       0  4986.5     .05       0
Bank Sta=4982.5,4986.5
XS Rating Curve= 0 ,0
Exp/Cntr=0.3,0.1

Type RM Length L Ch R = 1 ,9540    ,242,242,242
BEGIN DESCRIPTION:
TRIB 5 TO TURKEY CREEK 20.0
END DESCRIPTION:
XS GIS Cut Line= 3
      2523275.02     13479325.02        2523025.       13479075.
      2522775.04     13478975.02
#Sta/Elev= 30
    4646   190.4  4716.7  189.28  4759.2  188.25  4787.5  186.98  4829.9  185.97
  4858.2   184.9  4914.7  184.36  4928.9  183.62    4943  183.63  4971.3  182.27
  4985.4   180.8  4994.1  180.29  4994.3  179.79  4997.8  179.79  4998.1  180.29
  5002.3  180.29    5009  181.37  5014.4  181.22  5021.1  182.15  5038.6  183.27
  5068.2   184.1  5097.9  185.22  5107.3  185.28  5136.4  186.12  5146.3  186.63
    5176  187.43  5200.2   188.4    5254   189.8  5259.4  189.68  5268.8  189.93
#Mann= 4 ,-1 , 0
    4646     .05       0  4994.1     .05       0  4998.1     .05       0
  5136.4    .035       0
Bank Sta=4994.1,4998.1
XS Rating Curve= 0 ,0
Exp/Cntr=0.3,0.1

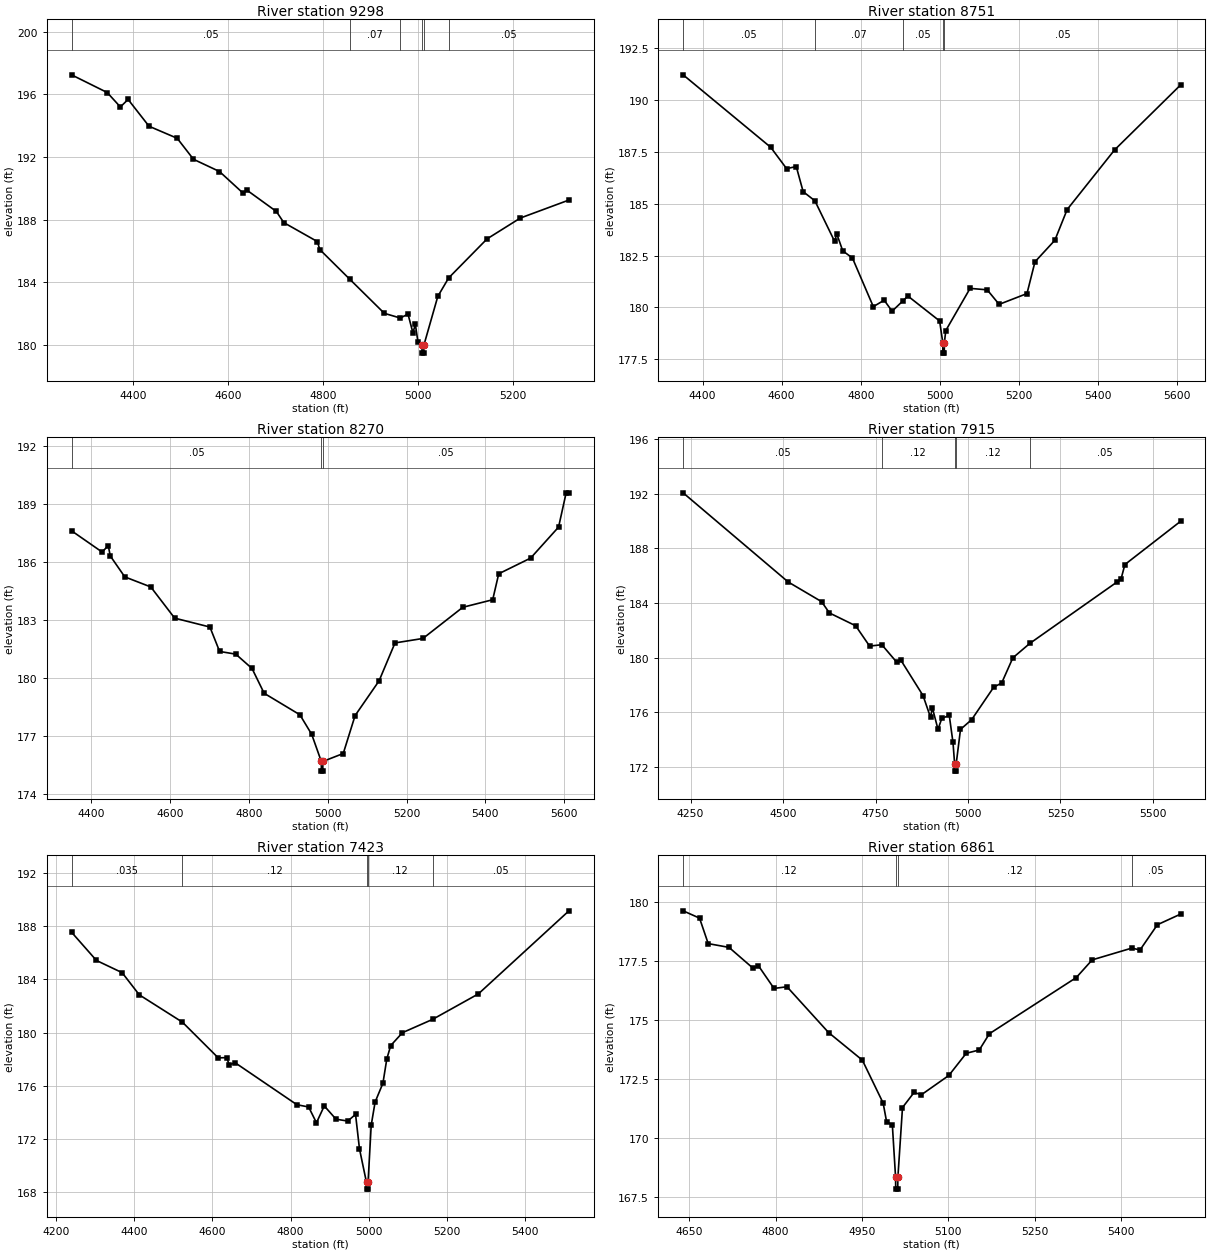
Type RM Length L Ch R = 1 ,9298    ,547,547,547
BEGIN DESCRIPTION:
Mapping XS 29380430
END DESCRIPTION:
XS GIS Cut Line= 4
      2523741.98     13479137.45      2523360.07     13478936.08
      2522953.82     13478811.08      2522762.82     13478824.97
#Sta/Elev= 30
  4269.8  197.25    4345  196.12  4372.7   195.2    4389  195.68  4433.1  193.97
  4492.5   193.2  4526.8  191.86  4581.6  191.08  4631.3   189.7  4639.4  189.89
  4701.5  188.53  4717.1  187.82  4787.8  186.61    4793   186.1  4856.7  184.19
    4929  182.03  4962.6  181.73  4978.9  181.98  4989.2  180.79  4994.4  181.32
  4999.8  180.22  5008.3  179.99  5008.5  179.49    5012  179.49  5012.3  179.99
  5041.7  183.11  5064.6  184.29  5145.5  186.78  5215.6  188.11  5318.1  189.26
#Mann= 6 ,-1 , 0
  4269.8     .05       0  4856.7     .07       0  4962.6     .12       0
  5008.3     .05       0  5012.3     .12       0  5064.6     .05       0
Bank Sta=5008.3,5012.3
XS Rating Curve= 0 ,0
Exp/Cntr=0.3,0.1

Type RM Length L Ch R = 1 ,8751    ,481,481,481
BEGIN DESCRIPTION:
Mapping XS 7df5dad0
END DESCRIPTION:
XS GIS Cut Line= 4
       2523804.5     13478505.51       2523419.1     13478383.99
      2523096.18     13478366.63      2522569.16     13478307.69
#Sta/Elev= 30
    4351  191.21  4572.4  187.72  4612.6  186.69  4637.1  186.79  4654.5  185.58
  4684.2  185.14  4734.2  183.18  4739.4  183.55  4754.6  182.73  4779.2  182.38
  4831.9  180.04  4859.4  180.35  4879.4  179.82  4907.4  180.33  4919.4  180.55
  4999.6  179.35  5007.6   178.3  5007.8   177.8  5011.3   177.8  5011.6   178.3
  5015.2  178.89  5076.6  180.92  5119.9  180.85  5150.1  180.15  5220.5  180.67
  5240.7   182.2    5291  183.24  5322.1  184.72  5441.9  187.59  5608.8  190.72
#Mann= 5 ,-1 , 0
    4351     .05       0  4684.2     .07       0  4907.4     .05       0
  5007.6     .05       0  5011.6     .05       0
Bank Sta=5007.6,5011.6
XS Rating Curve= 0 ,0
Exp/Cntr=0.3,0.1

Type RM Length L Ch R = 1 ,8270    ,355,355,355
BEGIN DESCRIPTION:
Mapping XS 942bfd09
END DESCRIPTION:
XS GIS Cut Line= 4
      2523960.74     13478071.49      2523464.24     13477953.44
      2523262.85     13477963.85       2522718.9     13478050.47
#Sta/Elev= 30
  4349.6  187.61  4427.4  186.51  4442.7  186.85    4448  186.31  4484.8  185.23
  4550.8  184.71  4611.4   183.1  4700.9  182.64  4725.5  181.38  4766.6  181.24
  4807.8   180.5  4838.6  179.22  4929.3  178.11  4959.3   177.1  4983.7   175.7
  4983.9   175.2  4987.4   175.2  4987.7   175.7  5039.4  176.11  5069.5  178.07
  5130.3  179.86  5170.8  181.82  5241.7  182.05  5342.9  183.66  5418.8  184.05
  5434.1  185.39  5515.1   186.2    5586   187.8  5605.3  189.57  5612.4  189.55
#Mann= 3 ,-1 , 0
  4349.6     .05       0  4983.7     .05       0  4987.7     .05       0
Bank Sta=4983.7,4987.7
XS Rating Curve= 0 ,0
Exp/Cntr=0.3,0.1

Type RM Length L Ch R = 1 ,7915    ,492,492,492
BEGIN DESCRIPTION:
Mapping XS dd127caf
END DESCRIPTION:
XS GIS Cut Line= 4
      2524085.74     13477679.13      2523471.18     13477581.91
      2523252.43     13477616.63      2522755.95     13477686.07
#Sta/Elev= 30
  4229.8  192.08    4514  185.54  4604.1   184.1  4625.4  183.27  4696.3  182.33
    4734  180.84  4767.1  180.94  4807.6  179.65  4817.8  179.84  4878.5  177.21
  4898.7  175.62  4903.7  176.32    4919  174.73  4929.1  175.53  4949.4  175.76
  4959.5  173.77    4964  172.17  4964.2  171.67  4967.7  171.67    4968  172.17
  4979.8  174.73  5010.1  175.45  5069.7  177.83  5091.1  178.13  5121.4  179.98
  5167.4  181.04  5404.1  185.56  5414.2  185.79  5424.3  186.82  5574.8  189.99
#Mann= 5 ,-1 , 0
  4229.8     .05       0  4767.1     .12       0    4964     .05       0
    4968     .12       0  5167.4     .05       0
Bank Sta=4964,4968
XS Rating Curve= 0 ,0
Exp/Cntr=0.3,0.1

Type RM Length L Ch R = 1 ,7423    ,562,562,562
BEGIN DESCRIPTION:
Mapping XS 54fe9fb7
END DESCRIPTION:
XS GIS Cut Line= 4
      2523995.47     13477380.51      2523582.29      13477158.3
      2523155.21      13477158.3      2522804.47     13477293.73
#Sta/Elev= 30
  4239.9  187.56  4303.6  185.43  4369.3  184.51  4413.2  182.84  4523.5  180.78
  4615.1  178.09  4637.1  178.11  4642.8  177.58    4659  177.71  4816.3  174.56
  4846.3  174.39  4866.3   173.2  4886.3  174.47  4916.3  173.47  4946.3  173.33
  4966.3  173.83  4976.3  171.24  4994.3   168.7  4994.6   168.2  4998.1   168.2
  4998.3   168.7  5006.3  173.01  5016.3  174.76  5036.3  176.18  5046.3  178.02
  5056.3  179.02  5086.3  179.99  5163.3  180.99  5280.4  182.91  5512.1  189.17
#Mann= 5 ,-1 , 0
  4239.9    .035       0  4523.5     .12       0  4994.3     .05       0
  4998.3     .12       0  5163.3     .05       0
Bank Sta=4994.3,4998.3
XS Rating Curve= 0 ,0
Exp/Cntr=0.3,0.1

Type RM Length L Ch R = 1 ,6861    ,180,180,180
BEGIN DESCRIPTION:
TRIB 5 TO TURKEY CREEK 14.0
END DESCRIPTION:
XS GIS Cut Line= 3
      2523824.98     13477024.96        2523625.       13476725.
        2523125.       13476775.
#Sta/Elev= 30
  4639.7  179.64  4668.2  179.33  4683.2  178.25  4719.3  178.09  4761.3   177.2
  4770.4  177.31  4797.4  176.35  4819.9  176.42    4892  174.48  4950.6  173.31
  4986.7  171.49  4992.7   170.7  5002.7  170.56  5008.3  168.34  5008.5  167.84
    5012  167.84  5012.3  168.34  5020.3   171.3  5040.4  171.94    5053  171.84
  5100.7  172.66  5130.9   173.6  5153.5  173.74  5171.1  174.43  5321.8  176.81
  5349.4  177.56  5418.2  178.06  5432.4  177.98  5462.5  179.05  5502.7   179.5
#Mann= 4 ,-1 , 0
  4639.7     .12       0  5008.3     .05       0  5012.3     .12       0
  5418.2     .05       0
Bank Sta=5008.3,5012.3
XS Rating Curve= 0 ,0
Exp/Cntr=0.3,0.1

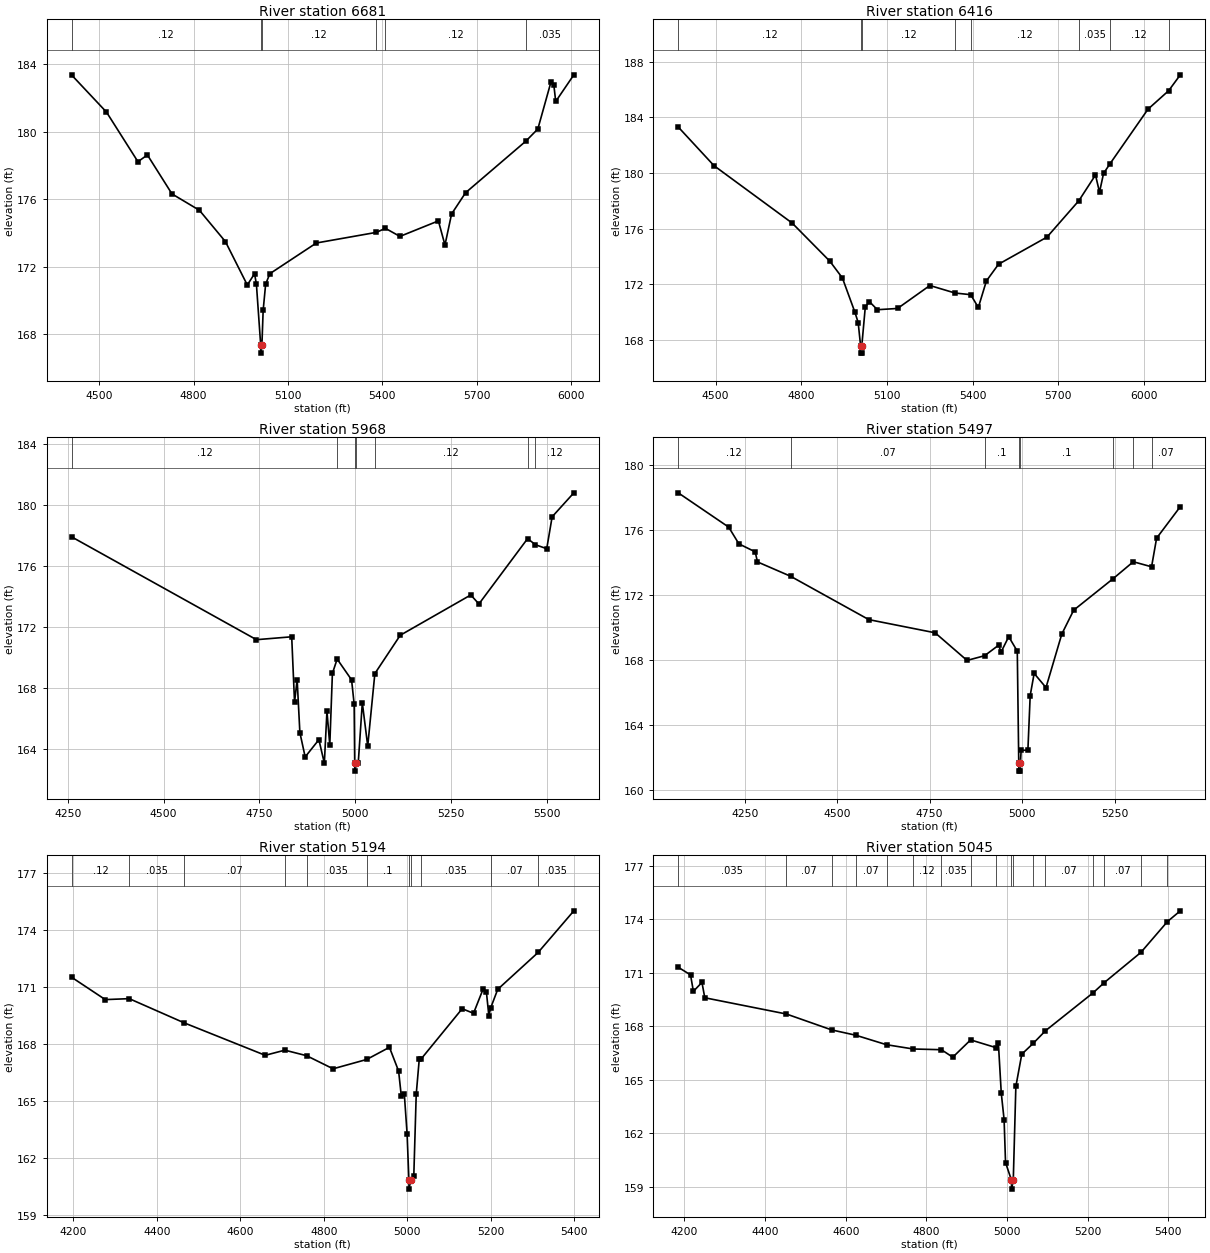
Type RM Length L Ch R = 1 ,6681    ,265,265,265
BEGIN DESCRIPTION:
Mapping XS 059b6216
END DESCRIPTION:
XS GIS Cut Line= 4
      2524075.37     13477036.81      2523804.51     13476630.52
       2523544.1     13476474.27      2522884.38     13476015.94
#Sta/Elev= 30
    4413  183.36  4523.3  181.17  4623.2  178.23  4653.3  178.63  4731.4  176.32
  4818.5  175.35  4901.3  173.49  4970.7  170.92  4993.8  171.59  4999.7  170.96
  5013.2  167.38  5013.5  166.88  5017.2  167.38  5021.1  169.41    5029  170.97
  5042.4  171.59  5190.2  173.41  5380.9  174.04  5409.4  174.28  5455.7   173.8
  5577.9  174.72  5598.8  173.29  5619.8  175.13  5664.3  176.39  5855.9  179.45
  5893.9  180.17  5935.8  182.97  5944.6   182.8  5950.7   181.8  6008.3  183.38
#Mann= 6 ,-1 , 0
    4413     .12       0  5013.2     .05       0  5017.2     .12       0
  5380.9     .05       0  5409.4     .12       0  5855.9    .035       0
Bank Sta=5013.2,5017.2
XS Rating Curve= 0 ,0
Exp/Cntr=0.3,0.1

Type RM Length L Ch R = 1 ,6416    ,448,448,448
BEGIN DESCRIPTION:
TRIB 5 TO TURKEY CREEK 13.0
END DESCRIPTION:
XS GIS Cut Line= 3
      2524174.99     13476924.99        2523875.       13476375.
      2523074.97     13475574.97
#Sta/Elev= 30
    4369   183.3  4494.3  180.52  4767.7   176.4  4900.1  173.65  4943.8  172.45
  4987.4     170    4999  169.25  5007.6  167.55  5007.9  167.05  5011.4  167.05
  5011.6  167.55  5023.8  170.34  5037.9  170.76  5066.2  170.17  5136.9  170.26
    5250  171.91    5338  171.37    5393  171.25  5419.7  170.33    5448  172.24
  5490.5  173.44  5660.2  175.39  5771.9  178.01  5829.9  179.85    5844  178.62
  5858.2  179.97  5880.8  180.66  6013.7  184.58  6086.1  185.91  6126.9  187.05
#Mann= 8 ,-1 , 0
    4369     .12       0  5007.6     .05       0  5011.6     .12       0
    5338      .1       0    5393     .12       0  5771.9    .035       0
  5880.8     .12       0  6086.1    .035       0
Bank Sta=5007.6,5011.6
XS Rating Curve= 0 ,0
Exp/Cntr=0.3,0.1

Type RM Length L Ch R = 1 ,5968    ,471,471,471
BEGIN DESCRIPTION:
TRIB 5 TO TURKEY CREEK 12.0
END DESCRIPTION:
XS GIS Cut Line= 3
      2524375.01     13476475.01        2523825.       13475975.
        2523425.       13475575.
#Sta/Elev= 30
  4260.7  177.91  4742.2  171.18  4834.1  171.37  4841.5  167.08  4848.3  168.57
  4855.4   165.1  4869.2   163.5    4905  164.63  4919.2  163.09    4926   166.5
  4933.4  164.27  4940.2  168.97  4952.6  169.91  4990.2  168.55  4996.9  166.97
  4998.4  163.07  4998.7  162.57  5002.8  163.07  5007.5  163.07  5018.2  167.05
  5032.3  164.21  5050.9  168.96  5117.1  171.47    5301  174.11  5322.2  173.52
  5449.1   177.8  5469.6   177.4    5499  177.14  5513.1  179.23  5569.7   180.8
#Mann= 7 ,-1 , 0
  4260.7     .12       0  4952.6      .1       0  4998.4     .05       0
  5002.8      .1       0  5050.9     .12       0  5449.1    .035       0
  5469.6     .12       0
Bank Sta=4998.4,5002.8
XS Rating Curve= 0 ,0
Exp/Cntr=0.3,0.1

Type RM Length L Ch R = 1 ,5497    ,303,303,303
BEGIN DESCRIPTION:
TRIB 5 TO TURKEY CREEK 11.0
END DESCRIPTION:
XS GIS Cut Line= 3
      2524574.98     13476324.98        2524025.       13475575.
      2523625.03     13475425.01
#Sta/Elev= 30
  4070.5   178.3  4206.9  176.19  4234.5  175.16  4278.5  174.67  4284.7  174.05
    4374  173.17  4585.7   170.5  4764.9  169.69  4851.2  167.99  4898.6  168.28
  4936.8  168.93    4943   168.5  4963.9  169.45    4987  168.56    4991  161.68
  4991.3  161.18  4995.2  161.18  4995.5  161.68  4997.4  162.45  5015.7  162.48
  5021.9  165.83  5032.6  167.19  5064.6  166.32  5107.3  169.61  5139.4  171.08
  5246.1  173.02  5300.6  174.06    5350  173.75  5363.6  175.51  5427.7  177.45
#Mann= 8 ,-1 , 0
  4070.5     .12       0    4374     .07       0  4898.6      .1       0
    4991     .05       0  4995.5      .1       0  5246.1     .12       0
  5300.6    .035       0    5350     .07       0
Bank Sta=4991,4995.5
XS Rating Curve= 0 ,0
Exp/Cntr=0.3,0.1

Type RM Length L Ch R = 1 ,5194    ,149,149,149
BEGIN DESCRIPTION:
Mapping XS f414c837
END DESCRIPTION:
XS GIS Cut Line= 3
      2524781.86     13475851.47      2524169.87     13475330.62
      2523829.54     13475121.44
#Sta/Elev= 30
    4196  171.51  4276.3  170.34  4333.7  170.39  4466.1  169.11  4659.6  167.41
  4706.6  167.68  4758.6  167.39  4822.2   166.7  4902.6  167.19  4957.2  167.83
  4979.2  166.58  4985.7  165.25  4992.9  165.36  4999.5  163.29  5003.8  160.87
  5004.1  160.37  5008.3  160.87  5015.6  161.08  5021.4  165.36  5028.8  167.24
  5033.6  167.23  5131.5  169.86  5158.7  169.62  5181.4  170.88  5189.5  170.75
  5195.4   169.5  5200.1  169.92  5216.7  170.88  5313.5  172.82  5399.1  175.01
#Mann= 11 ,-1 , 0
    4196     .12       0  4333.7    .035       0  4466.1     .07       0
  4706.6     .12       0  4758.6    .035       0  4902.6      .1       0
  5003.8     .05       0  5008.3      .1       0  5033.6    .035       0
  5200.1     .07       0  5313.5    .035       0
Bank Sta=5003.8,5008.3
XS Rating Curve= 0 ,0
Exp/Cntr=0.3,0.1

Type RM Length L Ch R = 1 ,5045    ,504,504,504
BEGIN DESCRIPTION:
TRIB 5 TO TURKEY CREEK 10.0
END DESCRIPTION:
XS GIS Cut Line= 3
      2524847.14     13475806.07        2524275.       13475225.
      2523924.99     13474974.99
#Sta/Elev= 30
  4184.5  171.31    4215  170.88  4222.1  169.96  4243.3  170.46  4250.4   169.6
  4452.8  168.69    4565   167.8  4625.2   167.5  4701.2  166.97  4767.6  166.73
  4837.4  166.69  4865.6  166.27  4909.9  167.24  4973.7   166.8  4978.8  167.04
  4985.9  164.26  4992.9  162.78  4996.5  160.37  5011.2  159.38  5011.5  158.88
  5015.7  159.38  5022.1  164.63  5036.8  166.44  5064.9  167.04  5095.5  167.75
  5213.9  169.88  5241.5  170.45  5332.3  172.14  5398.3  173.87  5430.1  174.47
#Mann= 17 ,-1 , 0
  4184.5    .035       0  4452.8     .07       0    4565    .035       0
  4625.2     .07       0  4701.2    .035       0  4767.6     .12       0
  4837.4    .035       0  4909.9     .12       0  4973.7    .035       0
  5011.2    .035       0  5015.7    .035       0  5064.9     .12       0
  5095.5     .07       0  5213.9    .035       0  5241.5     .07       0
  5332.3    .035       0  5398.3     .07       0
Bank Sta=5011.2,5015.7
XS Rating Curve= 0 ,0
Exp/Cntr=0.3,0.1

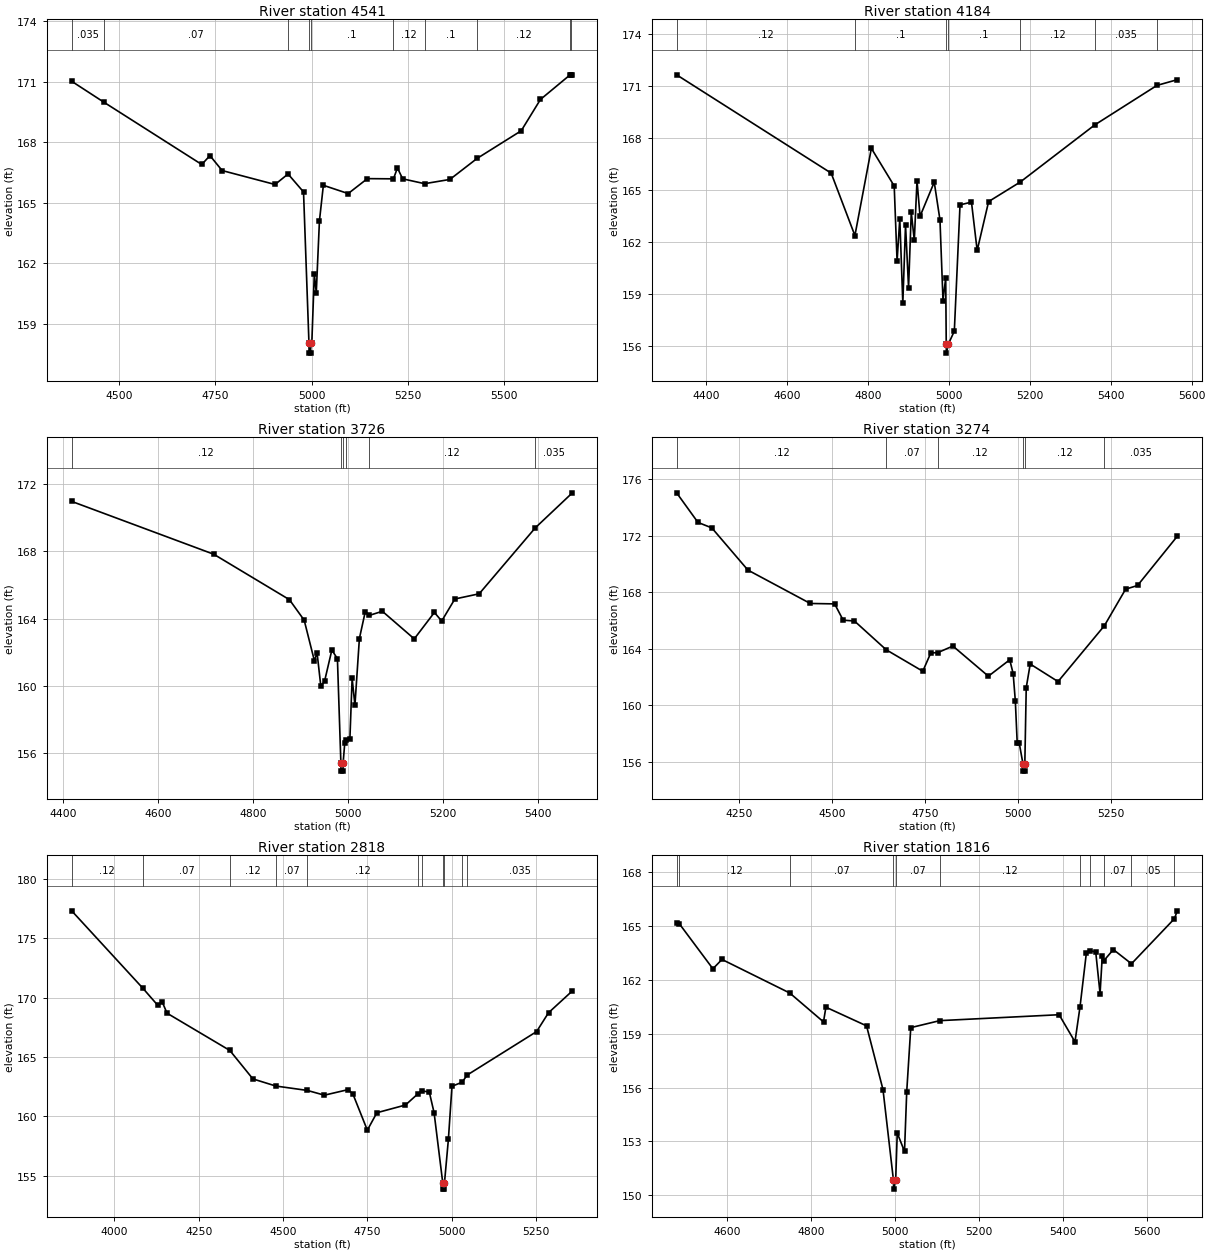
Type RM Length L Ch R = 1 ,4541    ,357,357,357
BEGIN DESCRIPTION:
Mapping XS 0b29a828
END DESCRIPTION:
XS GIS Cut Line= 4
      2524902.01     13475814.69      2524702.37      13475228.8
      2524689.35     13475159.35      2524203.23     13474790.42
#Sta/Elev= 30
  4377.4  171.02  4460.5  169.99  4715.1   166.9  4736.3  167.34    4768   166.6
  4905.3  165.91  4939.1  166.43  4979.3  165.54  4993.4  158.06  4993.7  157.56
  4997.7  157.56  4998.1  158.06  5000.8  158.06  5007.3  161.48  5012.4  160.55
  5020.6  164.11  5030.8  165.87  5095.2  165.46  5145.1   166.2  5212.8  166.19
  5223.1  166.73  5236.7  166.19  5293.7  165.95  5359.3  166.16  5429.9   167.2
  5544.5  168.57  5594.4  170.12  5671.5  171.34  5674.1  171.32  5677.3  171.32
#Mann= 10 ,-1 , 0
  4377.4    .035       0  4460.5     .07       0  4939.1      .1       0
  4993.4     .05       0  4998.1      .1       0  5212.8     .12       0
  5293.7      .1       0  5429.9     .12       0  5671.5    .035       0
  5674.1     .12       0
Bank Sta=4993.4,4998.1
XS Rating Curve= 0 ,0
Exp/Cntr=0.3,0.1

Type RM Length L Ch R = 1 ,4184    ,458,458,458
BEGIN DESCRIPTION:
TRIB 5 TO TURKEY CREEK 8.0
END DESCRIPTION:
XS GIS Cut Line= 3
      2525325.02     13475475.02        2524825.       13475025.
        2524425.       13474625.
#Sta/Elev= 30
  4326.1  171.65  4708.4  165.98  4767.1  162.38  4807.8  167.41  4864.3  165.24
  4871.4   160.9  4878.1  163.35  4885.6  158.48  4892.3     163  4899.8  159.37
  4906.5  163.73    4914   162.1  4920.7  165.55  4928.2  163.49  4963.3  165.46
  4977.5  163.28    4985  158.63  4991.7  159.95    4993   156.1  4993.4   155.6
  4997.8   156.1    5013  156.87  5027.1  164.15  5055.4  164.31  5069.5  161.52
  5097.8  164.34  5176.2  165.47  5360.3  168.76  5514.2  171.04  5564.5  171.37
#Mann= 7 ,-1 , 0
  4326.1     .12       0  4767.1      .1       0    4993     .05       0
  4997.8      .1       0  5176.2     .12       0  5360.3    .035       0
  5514.2     .12       0
Bank Sta=4993,4997.8
XS Rating Curve= 0 ,0
Exp/Cntr=0.3,0.1

Type RM Length L Ch R = 1 ,3726    ,452,452,452
BEGIN DESCRIPTION:
TRIB 5 TO TURKEY CREEK 7.0
END DESCRIPTION:
XS GIS Cut Line= 3
      2525475.01     13475325.01        2525175.       13474825.
      2524925.01     13474425.01
#Sta/Elev= 30
  4417.4  170.97  4716.7  167.83  4876.1  165.13  4907.2  163.91  4928.6  161.51
  4934.4  161.96  4942.2     160    4950  160.27  4965.5  162.14  4977.2  161.62
  4984.5  155.44  4984.9  154.94    4989  154.94  4989.3  155.44  4992.7  156.63
  4996.3   156.8  5003.5  156.86  5008.2  160.46  5014.1  158.85  5023.5  162.82
  5035.9  164.42  5043.8  164.19  5071.9  164.44  5139.1   162.8  5181.5  164.37
  5196.9  163.86  5224.6  165.17  5275.9  165.48  5394.1   169.4  5472.2  171.48
#Mann= 6 ,-1 , 0
  4417.4     .12       0  4984.5     .05       0  4989.3     .12       0
  4996.3      .1       0  5043.8     .12       0  5394.1    .035       0
Bank Sta=4984.5,4989.3
XS Rating Curve= 0 ,0
Exp/Cntr=0.3,0.1

Type RM Length L Ch R = 1 ,3274    ,456,456,456
BEGIN DESCRIPTION:
TRIB 5 TO TURKEY CREEK 6.0
END DESCRIPTION:
XS GIS Cut Line= 3
      2526174.96     13474924.98        2525375.       13474475.
      2524975.03     13474325.01
#Sta/Elev= 30
  4082.2  175.03  4139.5  172.94  4176.8  172.55  4273.7  169.57  4441.3  167.21
  4506.7  167.18  4529.6  166.03  4559.9  165.97  4645.1  163.94  4743.5  162.42
  4765.1  163.72  4783.3  163.73  4824.4   164.2  4919.7  162.07  4977.1  163.23
  4986.3  162.25  4992.1  160.32  4997.2  157.33  5002.7  157.33  5012.7  155.86
  5013.1  155.36  5017.3  155.36  5017.6  155.86  5021.4  161.26  5032.1  162.93
  5106.8  161.69  5231.4  165.64  5288.4  168.22  5320.4  168.48  5427.2  171.96
#Mann= 6 ,-1 , 0
  4082.2     .12       0  4645.1     .07       0  4783.3     .12       0
  5012.7     .05       0  5017.6     .12       0  5231.4    .035       0
Bank Sta=5012.7,5017.6
XS Rating Curve= 0 ,0
Exp/Cntr=0.3,0.1

Type RM Length L Ch R = 1 ,2818    ,1002,1002,1002
BEGIN DESCRIPTION:
TRIB 5 TO TURKEY CREEK 5.0
END DESCRIPTION:
XS GIS Cut Line= 3
      2526324.99     13474874.99        2525525.       13474075.
      2525275.01     13473825.01
#Sta/Elev= 30
  3873.4  177.32  4084.6  170.79  4127.9  169.38  4142.1  169.62  4156.2  168.69
  4342.4  165.55  4410.8  163.15  4478.9  162.55  4572.2  162.18  4622.9  161.78
  4693.6  162.25  4707.8  161.85  4750.2  158.83  4778.5   160.3  4863.3  160.95
  4900.8  161.91  4911.3  162.15    4934  162.04  4948.2   160.3    4974  154.36
  4974.4  153.86  4978.6  153.86  4978.9  154.36  4990.6  158.06  5001.2  162.53
  5031.1  162.87  5046.5  163.48  5252.2  167.14  5287.6  168.73  5358.3  170.57
#Mann= 11 ,-1 , 0
  3873.4     .12       0  4084.6     .07       0  4342.4     .12       0
  4478.9     .07       0  4572.2     .12       0  4900.8      .1       0
  4911.3     .12       0    4974     .05       0  4978.9     .12       0
  5031.1      .1       0  5046.5    .035       0
Bank Sta=4974,4978.9
XS Rating Curve= 0 ,0
Exp/Cntr=0.3,0.1

Type RM Length L Ch R = 1 ,1816    ,254,254,254
BEGIN DESCRIPTION:
Mapping XS 843fce4c
END DESCRIPTION:
XS GIS Cut Line= 4
      2526455.83     13474299.95      2526256.19     13473952.76
      2526134.67     13473891.99      2525509.83     13473696.73
#Sta/Elev= 30
  4480.4  165.16  4486.5  165.14  4566.7  162.62  4588.3  163.14  4749.5  161.27
  4829.8  159.66  4835.5  160.48  4932.2  159.44  4971.3  155.89  4996.2  150.84
  4996.6  150.34  5001.5  150.84  5005.2  153.47  5022.5  152.44  5027.8  155.78
  5037.4  159.34  5106.4  159.73  5390.3  160.06    5428  158.55    5440   160.5
  5455.2  163.52  5464.7  163.63  5477.4  163.55  5487.7  161.24    5493  163.35
  5495.9  163.05  5519.3  163.69  5562.4   162.9  5664.5  165.41  5671.4  165.85
#Mann= 11 ,-1 , 0
  4480.4     .07       0  4486.5     .12       0  4749.5     .07       0
  4996.2     .05       0  5001.5     .07       0  5106.4     .12       0
    5440     .07       0  5464.7     .05       0  5495.9     .07       0
  5562.4     .05       0  5664.5     .12       0
Bank Sta=4996.2,5001.5
XS Rating Curve= 0 ,0
Exp/Cntr=0.3,0.1