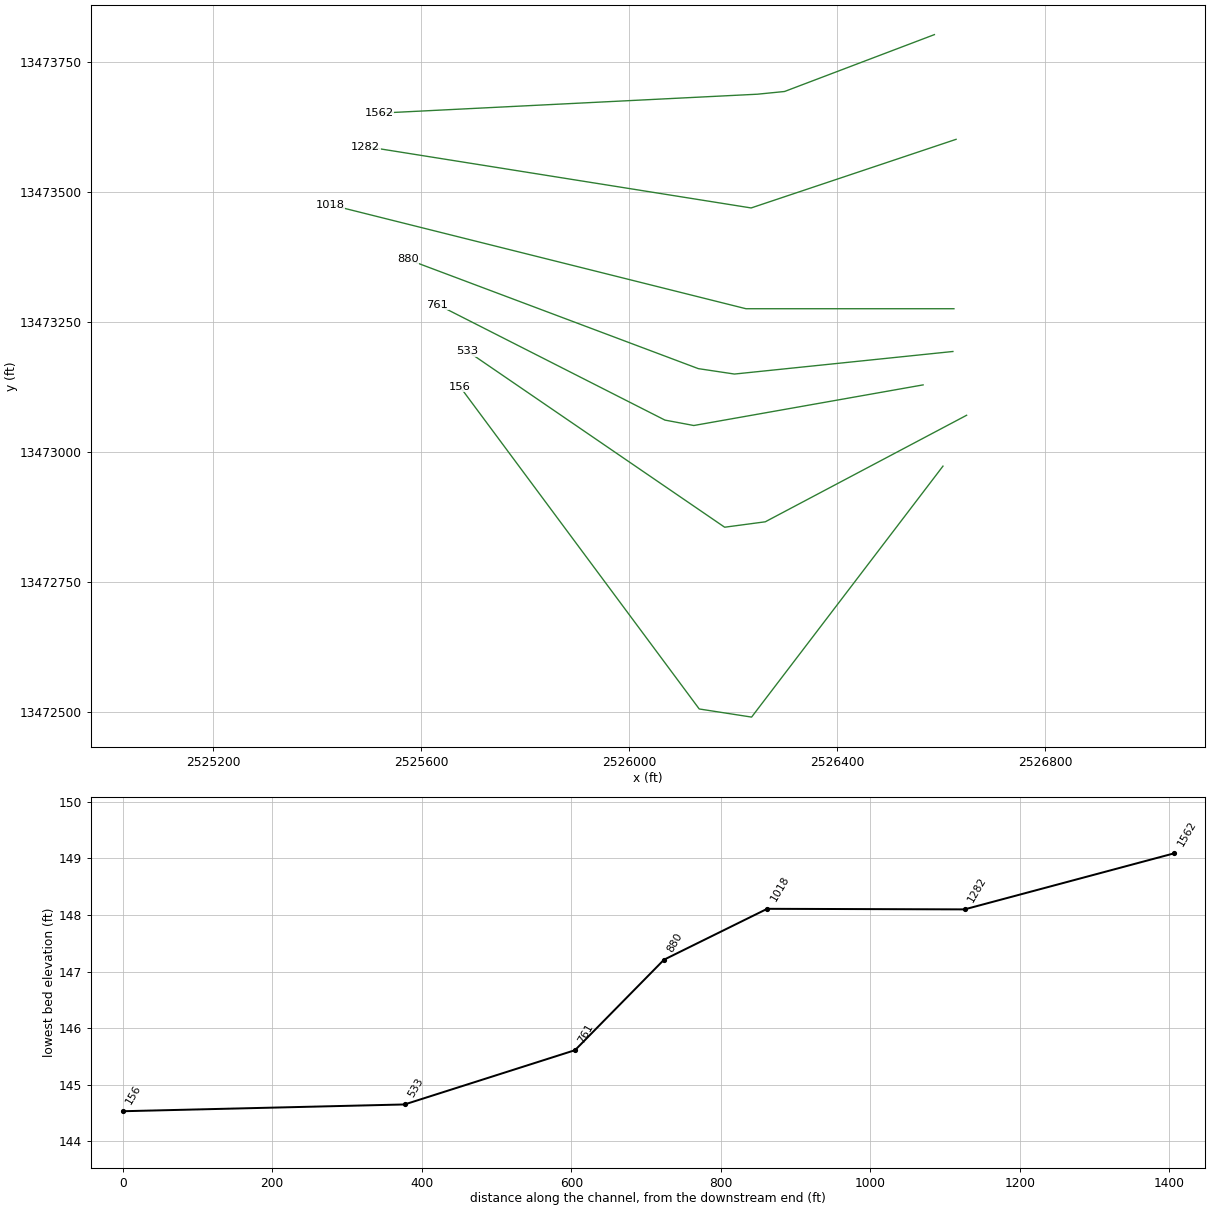
HEC-RAS study TRIB 5 TO TURKEY CREEK.prj: TRIB 5 TO TURKEY CREEK Base Level Engineering

--- TRIB 5 TO TURKEY CREEK.g01 (geometry) --- (continued)

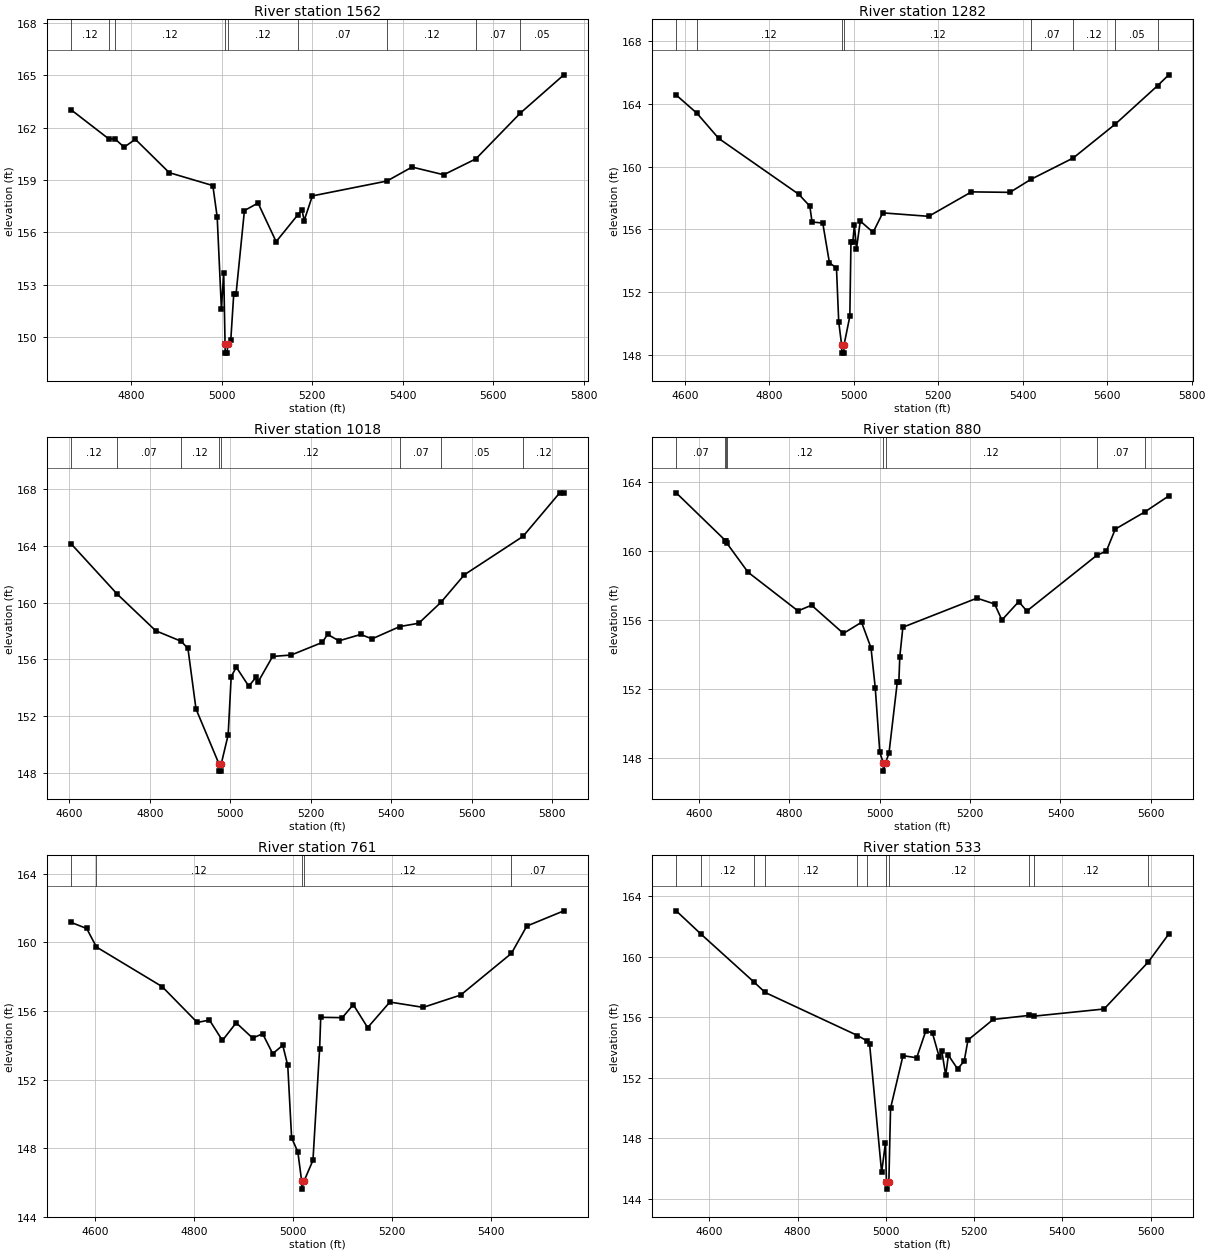
Type RM Length L Ch R = 1 ,1562    ,280,280,280
BEGIN DESCRIPTION:
Mapping XS 8a1217d6
END DESCRIPTION:
XS GIS Cut Line= 4
      2526587.37     13473802.15      2526299.16     13473692.77
      2526247.08     13473687.56       2525519.8     13473651.11
#Sta/Elev= 30
  4667.5  163.01    4751  161.34  4763.7  161.36  4784.3  160.88  4809.1  161.33
    4884  159.42  4980.4  158.68    4990  156.88  4999.3  151.63  5004.4  153.68
  5007.4  149.59  5007.8  149.09  5012.3  149.09  5012.8  149.59  5020.1  149.86
  5026.6  152.48  5031.7  152.48  5050.2  157.25  5080.3  157.68  5120.3  155.47
  5168.7  157.02  5177.3   157.3  5182.3  156.68  5200.4  158.09  5365.2  158.94
  5420.7  159.74  5490.8   159.3  5561.8  160.21  5660.1  162.83  5756.3  165.02
#Mann= 9 ,-1 , 0
  4667.5     .12       0    4751     .07       0  4763.7     .12       0
  5007.4     .05       0  5012.8     .12       0  5168.7     .07       0
  5365.2     .12       0  5561.8     .07       0  5660.1     .05       0
Bank Sta=5007.4,5012.8
XS Rating Curve= 0 ,0
Exp/Cntr=0.3,0.1

Type RM Length L Ch R = 1 ,1282    ,264,264,264
BEGIN DESCRIPTION:
Mapping XS ae0f360c
END DESCRIPTION:
XS GIS Cut Line= 3
      2526629.04     13473600.77      2526234.93     13473468.81
      2525493.59     13473586.87
#Sta/Elev= 30
  4579.5  164.57  4628.5  163.41  4680.2   161.8  4869.6  158.24  4895.9  157.48
  4901.1  156.47  4926.5   156.4  4942.3  153.87    4959  153.53  4964.3   150.1
  4971.3   148.6  4971.7   148.1  4976.3   148.1  4976.7   148.6  4990.6  150.45
  4993.3   155.2  4997.6   155.2  5001.4  156.27  5006.4  154.76  5015.3  156.53
  5045.7  155.81  5068.6  157.05  5177.3  156.83  5278.6  158.39  5369.7  158.36
  5419.4  159.19  5519.4  160.55  5619.4  162.72  5719.4  165.17  5745.8  165.86
#Mann= 8 ,-1 , 0
  4579.5     .07       0  4628.5     .12       0  4971.3     .05       0
  4976.7     .12       0  5419.4     .07       0  5519.4     .12       0
  5619.4     .05       0  5719.4     .12       0
Bank Sta=4971.3,4976.7
XS Rating Curve= 0 ,0
Exp/Cntr=0.3,0.1

Type RM Length L Ch R = 1 ,1018    ,138,138,138
BEGIN DESCRIPTION:
TRIB 5 TO TURKEY CREEK 2.0
END DESCRIPTION:
XS GIS Cut Line= 3
      2526624.96       13473275.        2526225.       13473275.
      2525424.98     13473475.01
#Sta/Elev= 30
  4604.8  164.13  4718.5  160.61  4814.8  158.01    4878  157.27  4894.8  156.76
  4914.8   152.5  4972.1  148.61  4972.5  148.11  4977.1  148.11  4977.5  148.61
  4994.8  150.67  5002.3  154.78  5015.1  155.44    5046   154.1    5064  154.73
  5069.2   154.4  5105.3   156.2  5151.6   156.3    5229  157.19  5241.8  157.76
  5270.2   157.3  5324.3  157.75  5352.6  157.44  5421.8  158.31  5468.6  158.54
  5523.9  160.02    5582  161.96  5727.9  164.67  5819.1  167.74  5829.4   167.7
#Mann= 8 ,-1 , 0
  4604.8     .12       0  4718.5     .07       0    4878     .12       0
  4972.1     .05       0  4977.5     .12       0  5421.8     .07       0
  5523.9     .05       0  5727.9     .12       0
Bank Sta=4972.1,4977.5
XS Rating Curve= 0 ,0
Exp/Cntr=0.3,0.1

Type RM Length L Ch R = 1 ,880     ,119,119,119
BEGIN DESCRIPTION:
Mapping XS 75c8a7c7
END DESCRIPTION:
XS GIS Cut Line= 4
      2526622.95     13473192.77      2526202.81     13473149.37
      2526133.36     13473159.79      2525574.33     13473369.86
#Sta/Elev= 30
  4549.8  163.38  4658.6  160.61  4659.4  160.57  4661.2  160.48  4708.6  158.77
  4819.2  156.52  4849.3  156.85  4919.7  155.21  4959.9  155.86  4980.8  154.37
  4990.2  152.05  5000.3   148.3  5007.7  147.71  5008.1  147.21  5013.1  147.71
  5020.5  148.24    5039  152.39  5042.4  152.39  5044.5  153.86  5051.3  155.57
  5215.2  157.26  5254.3  156.92  5270.4  155.99  5307.7  157.06  5325.5  156.51
  5479.9  159.74  5501.6     160  5521.2  161.27    5586  162.26  5639.6   163.2
#Mann= 8 ,-1 , 0
  4549.8     .07       0  4658.6     .12       0  4659.4     .07       0
  4661.2     .12       0  5007.7     .05       0  5013.1     .12       0
  5479.9     .07       0    5586     .05       0
Bank Sta=5007.7,5013.1
XS Rating Curve= 0 ,0
Exp/Cntr=0.3,0.1

Type RM Length L Ch R = 1 ,761     ,228,228,228
BEGIN DESCRIPTION:
Mapping XS af586080
END DESCRIPTION:
XS GIS Cut Line= 4
      2526565.64     13473128.53      2526124.68     13473050.41
      2526069.13     13473060.83      2525631.58     13473283.07
#Sta/Elev= 30
    4552  161.16  4583.1  160.81  4602.8  159.73  4735.5  157.42  4806.5  155.33
  4831.1  155.47  4857.3  154.28  4885.1  155.31  4918.3  154.42  4938.6  154.67
  4958.9  153.51  4979.2     154  4989.3  152.82  4997.1   148.6  5009.7  147.78
  5017.2  146.11  5017.6  145.61  5022.6  146.11  5040.2  147.29  5053.7  153.81
  5055.9  155.63  5099.5  155.61  5121.7  156.37  5150.7  155.03  5195.6  156.52
  5262.9  156.21  5338.7  156.93  5441.2  159.36  5472.2  160.95  5547.1  161.84
#Mann= 5 ,-1 , 0
    4552     .07       0  4602.8     .12       0  5017.2     .05       0
  5022.6     .12       0  5441.2     .07       0
Bank Sta=5017.2,5022.6
XS Rating Curve= 0 ,0
Exp/Cntr=0.3,0.1

Type RM Length L Ch R = 1 ,533     ,377,377,377
BEGIN DESCRIPTION:
Mapping XS 252e166c
END DESCRIPTION:
XS GIS Cut Line= 4
       2526649.3      13473070.1      2526262.12     13472865.23
        2526184.     13472854.81      2525689.61     13473193.08
#Sta/Elev= 30
  4525.2  163.02  4581.5  161.48  4702.1   158.3  4726.8  157.63  4935.9  154.79
  4957.2  154.44  4963.2  154.26  4990.6  145.75  4999.2   147.7  5001.5  145.15
    5002  144.65    5007  145.15  5010.8  149.99    5039  153.46    5070  153.32
    5091  155.12  5105.9  154.93  5120.8   153.4  5126.9  153.75  5135.8  152.16
  5141.8  153.49  5162.8  152.58  5177.7  153.11  5186.2  154.49  5243.4  155.85
  5325.5  156.12  5336.6  156.07  5494.6  156.54  5594.6  159.64  5641.1  161.49
#Mann= 11 ,-1 , 0
  4525.2     .07       0  4581.5     .12       0  4702.1     .07       0
  4726.8     .12       0  4935.9      .1       0  4957.2     .12       0
  5001.5     .05       0    5007     .12       0  5325.5     .07       0
  5336.6     .12       0  5594.6     .07       0
Bank Sta=5001.5,5007
XS Rating Curve= 0 ,0
Exp/Cntr=0.3,0.1

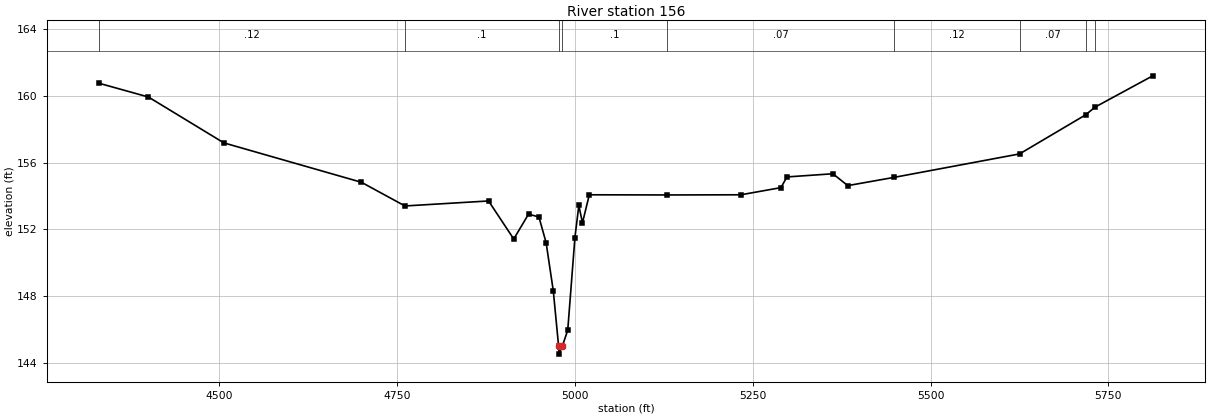
Type RM Length L Ch R = 1 ,156     ,0,0,0
BEGIN DESCRIPTION:
TRIB 5 TO TURKEY CREEK 1.0
END DESCRIPTION:
XS GIS Cut Line= 4
      2526603.85     13472972.29      2526235.79     13472489.65
       2526135.1     13472505.27      2525675.01     13473124.98
#Sta/Elev= 30
  4331.6  160.76  4400.6  159.94  4506.7  157.19    4700  154.83  4761.2  153.41
  4878.7  153.71  4914.1  151.43  4934.9  152.92  4949.5  152.75  4959.6  151.21
  4969.7  148.32  4977.1  145.03  4977.6  144.53  4982.6  145.03    4990  145.97
  5000.1  151.52  5005.6  153.44  5010.7   152.4  5020.3  154.08  5129.9  154.07
  5233.4  154.08  5289.7  154.51  5298.1  155.15  5362.7  155.34  5383.6  154.63
  5448.3  155.12  5625.1  156.53  5717.9  158.87  5731.4  159.34  5812.3  161.21
#Mann= 9 ,-1 , 0
  4331.6     .12       0  4761.2      .1       0  4977.1     .05       0
  4982.6      .1       0  5129.9     .07       0  5448.3     .12       0
  5625.1     .07       0  5717.9     .05       0  5731.4     .07       0
Bank Sta=4977.1,4982.6
XS Rating Curve= 0 ,0
Exp/Cntr=0.3,0.1

Chan Stop Cuts=-1
Use User Specified Reach Order=0
Composite Channel Slope=5