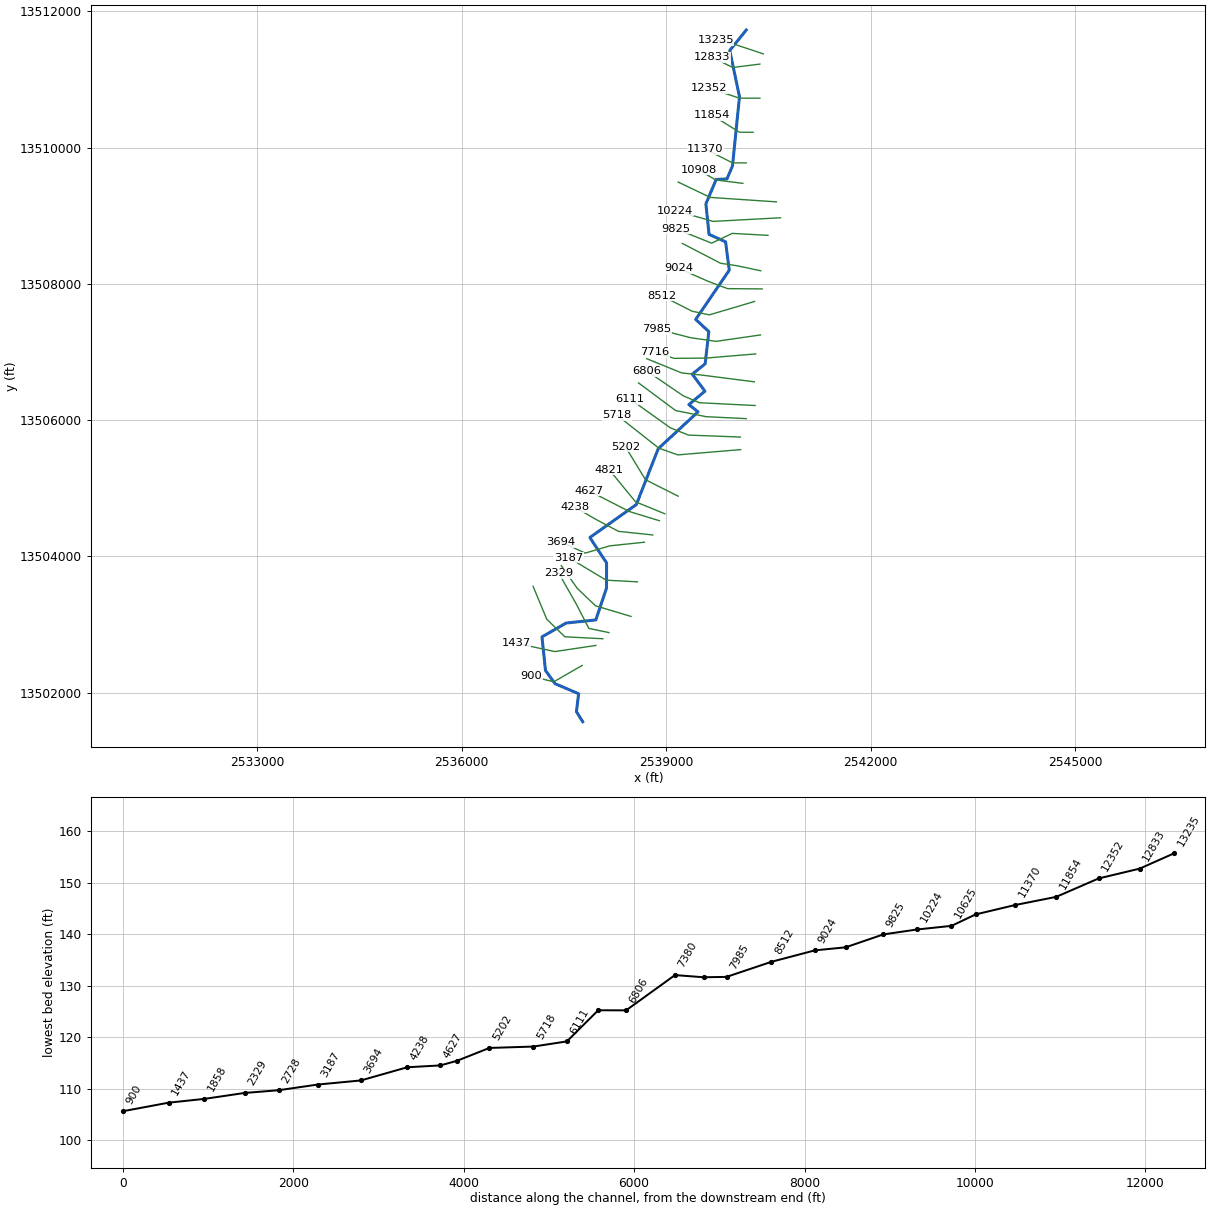
--- TRIB 5A TO COLETO CREEK.prj (project) ---

Proj Title=TRIB 5A TO COLETO CREEK Base Level Engineering
Current Plan=p01
Default Exp/Contr=0.3,0.1
English Units
Geom File=g01
Flow File=f01
Plan File=p01
Y Axis Title=Elevation
X Axis Title(PF)=Main Channel Distance
X Axis Title(XS)=Station
BEGIN DESCRIPTION:
TRIB 5A TO COLETO CREEK
END DESCRIPTION:
DSS Export Rating Curves= 0
DSS Export Rating Curve Sorted= 0
DSS Export Volume Flow Curves= 0
DXF OffsetX= 0
DXF OffsetY= 0
DXF ScaleX= 1
DXF ScaleY= 10

--- TRIB 5A TO COLETO CREEK.p01 (plan) ---

Plan Title=Multiple Run
Short Identifier=Multiple
Geom File=g01
Flow File=f01
Subcritical Flow
K Sum by GR= 0
Std Step Tol= 0.01
Critical Tol= 0.01
Num of Std Step Trials= 20
Max Error Tol= 0.3
Flow Tol Ratio= 0.001
Split Flow NTrial= 30
Split Flow Tol= 0.02
Split Flow Ratio= 0.02
Log Output Level= 0
Friction Slope Method= 1
Unsteady Friction Slope Method= 2
Unsteady Bridges Friction Slope Method= 1
Parabolic Critical Depth
Global Vel Dist=  1 , 1 , 1
Global Log Level= 0
CheckData=True
Encroach Param= -1, 0, 0, 0
BEGIN DESCRIPTION:
Multiple Run
END DESCRIPTION:

--- TRIB 5A TO COLETO CREEK.f01 (steady flow) ---

Flow Title=Multiple
Number of Profiles=7
Profile Names=10-year,25-year,50-year,1pct_min,100-year,1pct_plu,500-year
River Rch & RM= TRIB 5A TO COLET,Reach-1,13235
    1216    2009    2742    1809    3609    7200    6181
River Rch & RM= TRIB 5A TO COLET,Reach-1,8512
    1307    2167    2965    1959    3909    7800    6724
River Rch & RM= TRIB 5A TO COLET,Reach-1,6111
    1678    2818    3889    2590    5167   10310    9029
River Rch & RM= TRIB 5A TO COLET,Reach-1,5202
    1771    2979    4114    2741    5470   10914    9569
River Rch & RM= TRIB 5A TO COLET,Reach-1,2728
    1972    3327    4605    3073    6132   12236   10764
Boundary for River Rch & Prof#=TRIB 5A TO COLET,Reach-1,1
Up Type=0
Dn Type=3
Dn Slope=0.005
Boundary for River Rch & Prof#=TRIB 5A TO COLET,Reach-1,2
Up Type=0
Dn Type=3
Dn Slope=0.005
Boundary for River Rch & Prof#=TRIB 5A TO COLET,Reach-1,3
Up Type=0
Dn Type=3
Dn Slope=0.005
Boundary for River Rch & Prof#=TRIB 5A TO COLET,Reach-1,4
Up Type=0
Dn Type=3
Dn Slope=0.005
Boundary for River Rch & Prof#=TRIB 5A TO COLET,Reach-1,5
Up Type=0
Dn Type=3
Dn Slope=0.005
Boundary for River Rch & Prof#=TRIB 5A TO COLET,Reach-1,6
Up Type=0
Dn Type=3
Dn Slope=0.005
Boundary for River Rch & Prof#=TRIB 5A TO COLET,Reach-1,7
Up Type=0
Dn Type=3
Dn Slope=0.005

--- TRIB 5A TO COLETO CREEK.g01 (geometry) ---

Geom Title=Existing Conditions
Program Version=4.10

River Reach=TRIB 5A TO COLET,Reach-1
Reach XY= 30
        2540175.       13511725.      2539932.53     13511425.01
      2540075.36     13510745.15      2539972.74     13509730.94
      2539892.16     13509541.11      2539733.04     13509531.42
      2539582.59     13509174.99      2539628.44     13508726.22
       2539871.5     13508616.54      2539925.21     13508199.91
      2539432.83     13507478.23      2539625.53     13507300.12
      2539571.55     13506826.25      2539382.28      13506675.1
      2539568.03     13506424.76      2539332.76     13506228.05
      2539467.24     13506121.95      2538883.14     13505581.06
      2538561.68     13504761.37      2537879.98     13504277.55
      2538125.04     13503905.02      2538123.95     13503535.43
       2537967.2     13503068.16      2537530.94     13503022.74
      2537177.05     13502819.16      2537228.55     13502326.47
      2537368.66     13502133.02      2537714.68     13501985.17
      2537682.78     13501721.58        2537775.       13501575.

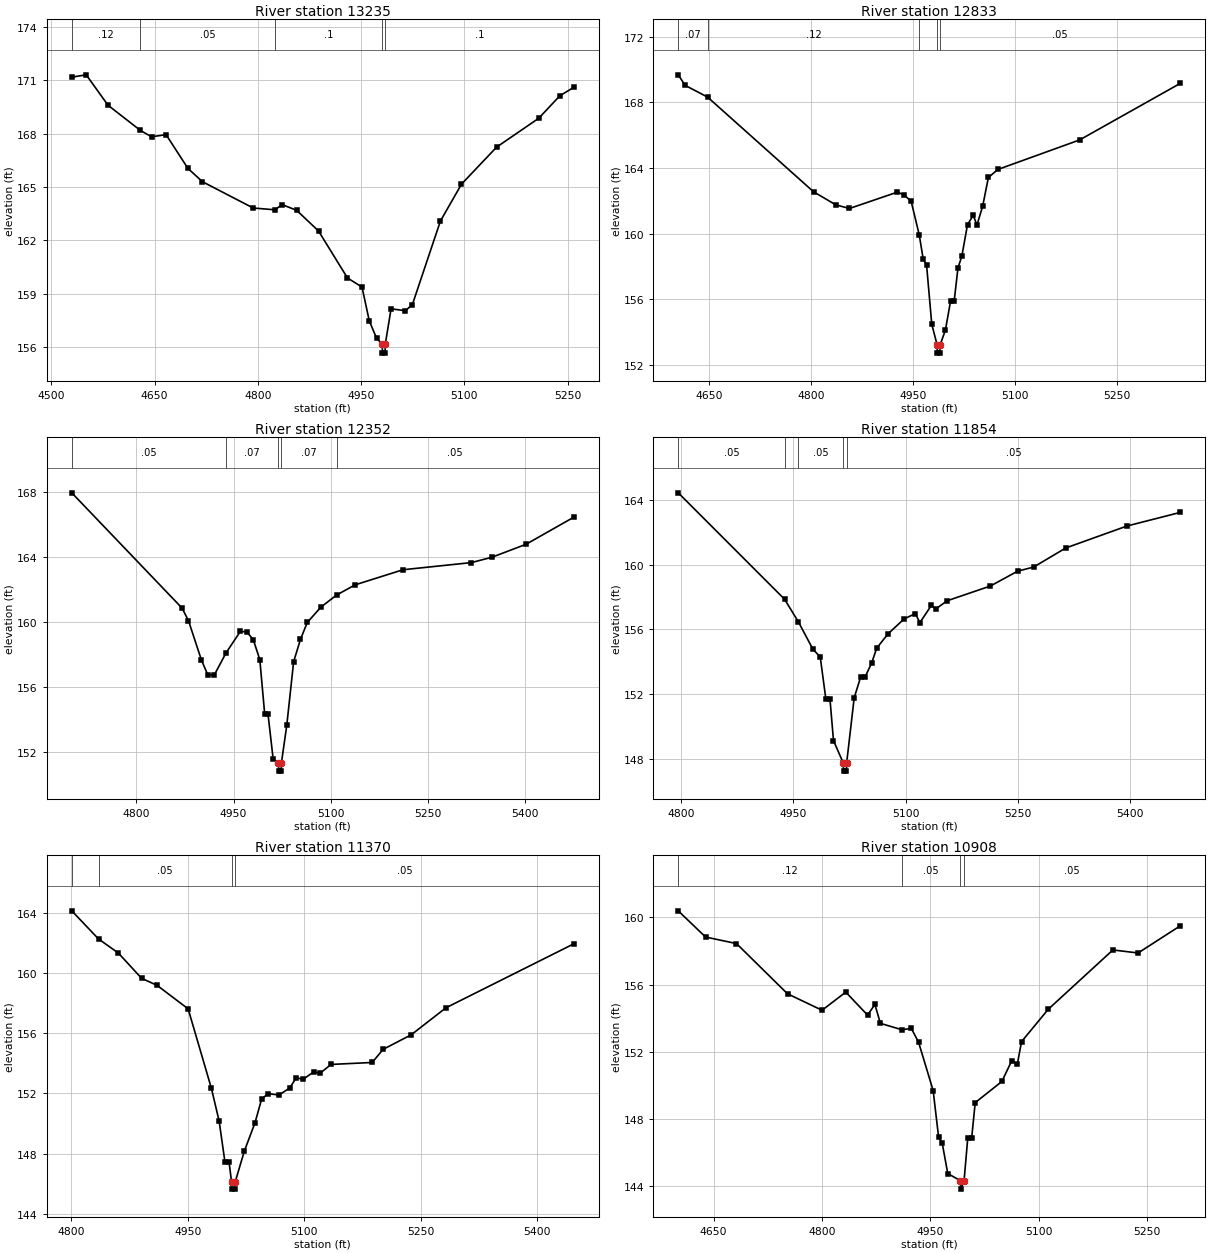
Type RM Length L Ch R = 1 ,13235   ,402,402,402
BEGIN DESCRIPTION:
TRIB 5A TO COLETO CREEK 29.0
END DESCRIPTION:
XS GIS Cut Line= 3
      2540424.96     13511375.01        2539975.       13511525.
      2539724.95     13511575.01
#Sta/Elev= 30
  4529.8  171.17  4550.8   171.3  4582.5  169.59  4629.4  168.18  4645.7  167.82
  4666.8  167.94  4698.4  166.05  4719.5   165.3  4793.3  163.82  4824.8  163.72
  4835.4  164.01  4856.5  163.69  4888.2  162.53  4930.3  159.89  4951.4  159.38
  4961.9  157.49  4972.5  156.51  4980.8  156.17  4981.1  155.67  4984.9  155.67
  4985.2  156.17  4993.6  158.16  5014.3  158.05  5024.5  158.39  5065.3  163.09
  5095.9  165.16  5146.9  167.24  5208.1  168.86  5238.7  170.12  5259.1   170.6
#Mann= 5 ,-1 , 0
  4529.8     .12       0  4629.4     .05       0  4824.8      .1       0
  4980.8     .05       0  4985.2      .1       0
Bank Sta=4980.8,4985.2
XS Rating Curve= 0 ,0
Exp/Cntr=0.3,0.1

Type RM Length L Ch R = 1 ,12833   ,481,481,481
BEGIN DESCRIPTION:
TRIB 5A TO COLETO CREEK 28.0
END DESCRIPTION:
XS GIS Cut Line= 3
      2540374.99       13511225.        2539975.       13511175.
      2539675.02     13511324.99
#Sta/Elev= 30
  4604.9  169.68    4615  169.04  4648.1  168.32  4803.9  162.55  4836.7  161.75
  4856.8  161.53  4927.4  162.53  4937.5  162.34  4947.5  161.97  4959.4  159.92
  4965.2  158.45  4970.2  158.07  4977.8  154.48  4985.7  153.21    4986  152.71
  4989.8  152.71  4990.1  153.21  4997.9  154.12  5005.5  155.89  5010.8  155.89
  5016.4  157.92    5022  158.61  5030.4  160.55  5038.8  161.11  5044.3  160.52
  5052.7  161.67  5061.1  163.42  5075.1  163.91  5195.3  165.71  5343.4  169.16
#Mann= 5 ,-1 , 0
  4604.9     .07       0  4648.1     .12       0  4959.4     .05       0
  4985.7     .05       0  4990.1     .05       0
Bank Sta=4985.7,4990.1
XS Rating Curve= 0 ,0
Exp/Cntr=0.3,0.1

Type RM Length L Ch R = 1 ,12352   ,498,498,498
BEGIN DESCRIPTION:
TRIB 5A TO COLETO CREEK 27.0
END DESCRIPTION:
XS GIS Cut Line= 3
        2540375.       13510725.        2540075.       13510725.
      2539625.04     13510874.99
#Sta/Elev= 30
  4700.4  167.96  4870.4  160.86  4880.4  160.08  4900.4  157.65  4910.4  156.72
  4920.4  156.75  4938.2  158.09  4960.4  159.42  4970.4  159.39  4980.4   158.9
  4990.4  157.68  4997.9  154.34    5003  154.34  5010.9  151.58  5019.2  151.31
  5019.6  150.81  5023.4  150.81  5023.7  151.31    5032  153.64  5042.6  157.56
  5053.1  158.93  5063.6  159.97  5084.7  160.92  5108.8  161.66  5137.4  162.29
  5211.2  163.22  5316.6  163.66  5348.3  163.99    5401  164.79  5474.7  166.46
#Mann= 5 ,-1 , 0
  4700.4     .05       0  4938.2     .07       0  5019.2     .05       0
  5023.7     .07       0  5108.8     .05       0
Bank Sta=5019.2,5023.7
XS Rating Curve= 0 ,0
Exp/Cntr=0.3,0.1

Type RM Length L Ch R = 1 ,11854   ,484,484,484
BEGIN DESCRIPTION:
TRIB 5A TO COLETO CREEK 26.0
END DESCRIPTION:
XS GIS Cut Line= 3
      2540275.01       13510225.        2540075.       13510225.
      2539675.01     13510474.99
#Sta/Elev= 30
  4795.8  164.43  4938.1  157.85  4956.5  156.46  4975.8  154.78  4985.8  154.28
  4993.3  151.68  4998.8  151.68  5003.5  149.12  5016.6  147.73  5016.9  147.23
  5020.8  147.23  5021.1  147.73  5031.2  151.76    5040  153.07  5045.9  153.06
  5054.8  153.94  5061.3  154.83  5076.6  155.72  5097.8  156.63  5113.1  156.97
    5119   156.4  5134.4  157.47  5140.3  157.25  5155.6  157.76  5213.4  158.67
  5249.9  159.59  5271.2  159.84  5314.2  161.02  5396.2  162.38  5467.5  163.22
#Mann= 5 ,-1 , 0
  4795.8     .05       0  4938.1     .12       0  4956.5     .05       0
  5016.6     .05       0  5021.1     .05       0
Bank Sta=5016.6,5021.1
XS Rating Curve= 0 ,0
Exp/Cntr=0.3,0.1

Type RM Length L Ch R = 1 ,11370   ,462,462,462
BEGIN DESCRIPTION:
TRIB 5A TO COLETO CREEK 25.0
END DESCRIPTION:
XS GIS Cut Line= 3
      2540175.01       13509775.        2539975.       13509775.
      2539575.02     13509974.99
#Sta/Elev= 30
  4800.4  164.12  4834.9  162.25  4860.4  161.32  4890.4  159.64  4910.4  159.17
  4950.4  157.61  4980.4  152.33  4990.4  150.15  4997.9  147.42  5003.2  147.42
  5006.3  146.14  5006.7  145.64  5010.9  145.64  5011.2  146.14  5022.8  148.16
  5036.7  150.06  5045.1  151.62  5053.5  151.98  5067.5  151.89  5081.5  152.36
  5089.8  153.05  5098.2  152.92  5112.2  153.42  5120.6  153.34  5134.6  153.92
  5187.7  154.05  5201.7  154.92    5238  155.89  5282.7  157.68  5447.6  161.93
#Mann= 4 ,-1 , 0
  4800.4     .07       0  4834.9     .05       0  5006.3     .05       0
  5011.2     .05       0
Bank Sta=5006.3,5011.2
XS Rating Curve= 0 ,0
Exp/Cntr=0.3,0.1

Type RM Length L Ch R = 1 ,10908   ,283,283,283
BEGIN DESCRIPTION:
TRIB 5A TO COLETO CREEK 24.0
END DESCRIPTION:
XS GIS Cut Line= 3
        2540125.       13509475.        2539725.       13509525.
      2539474.96     13509675.02
#Sta/Elev= 30
  4601.2  160.39    4639  158.83  4681.8  158.44  4752.4  155.45  4800.2  154.47
    4833  155.55  4863.2  154.18  4873.3  154.82  4880.9  153.69  4910.7  153.31
  4923.7  153.39  4933.8  152.56  4953.9  149.69  4961.5   146.9  4966.5  146.55
  4974.1  144.75  4991.7  144.32  4992.1  143.82  4996.7  144.32  5001.8  146.86
  5007.2  146.86  5012.1  148.97    5049  150.23  5062.6  151.46  5070.4  151.26
  5076.2   152.6  5113.2  154.53  5202.6  158.06  5237.5  157.88  5295.9   159.5
#Mann= 4 ,-1 , 0
  4601.2     .12       0  4910.7     .05       0  4991.7     .05       0
  4996.7     .05       0
Bank Sta=4991.7,4996.7
XS Rating Curve= 0 ,0
Exp/Cntr=0.3,0.1

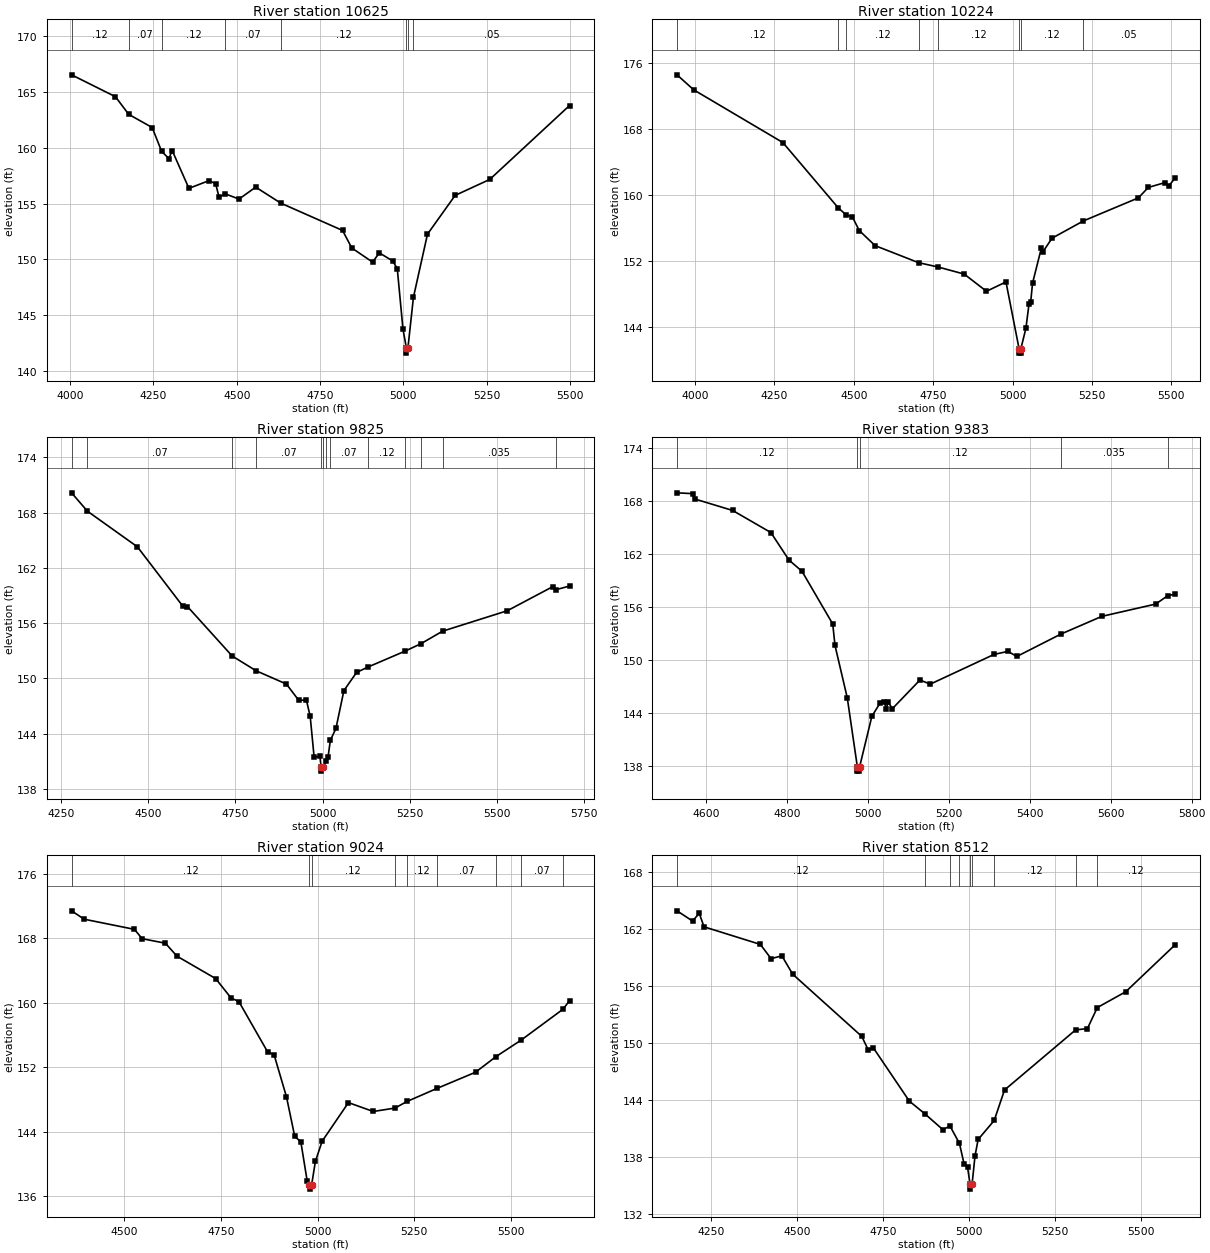
Type RM Length L Ch R = 1 ,10625   ,401,401,401
BEGIN DESCRIPTION:
Mapping XS 56aae43a
END DESCRIPTION:
XS GIS Cut Line= 3
      2540616.38     13509203.19      2539646.11     13509268.69
      2539175.36     13509493.83
#Sta/Elev= 30
  4004.4  166.53  4136.1  164.57  4175.9  162.99  4246.3  161.81  4274.6  159.68
  4296.4  159.03  4306.5  159.74  4356.6  156.36  4416.7  157.05  4436.8  156.78
  4446.8  155.59  4466.3  155.86  4506.9   155.4    4557  156.47    4632  155.04
  4817.6  152.59  4845.3  151.02  4907.8  149.75  4927.9  150.58    4968  149.86
  4981.8  149.17  4998.9  143.75  5008.9   142.1  5009.2   141.6  5013.9   142.1
  5030.3   146.6  5072.5  152.26  5155.5  155.73  5259.4  157.16  5498.7  163.78
#Mann= 8 ,-1 , 0
  4004.4     .12       0  4175.9     .07       0  4274.6     .12       0
  4466.3     .07       0    4632     .12       0  5008.9     .05       0
  5013.9     .12       0  5030.3     .05       0
Bank Sta=5008.9,5013.9
XS Rating Curve= 0 ,0
Exp/Cntr=0.3,0.1

Type RM Length L Ch R = 1 ,10224   ,399,399,399
BEGIN DESCRIPTION:
Mapping XS 9efa9f8b
END DESCRIPTION:
XS GIS Cut Line= 3
      2540677.75     13508969.84      2539687.05     13508916.62
      2539134.38     13509076.28
#Sta/Elev= 30
  3943.7  174.56  3996.5  172.74  4276.9  166.37  4451.7  158.45  4476.3  157.62
  4496.1  157.35  4517.3  155.73  4567.3   153.9  4704.2  151.84  4765.1  151.32
  4847.7  150.46  4917.9  148.38  4979.2  149.51  5020.6   141.4  5021.1   140.9
  5025.5   140.9  5025.9   141.4    5042  143.91  5051.7  146.85  5056.9  147.06
  5062.9  149.37  5090.5  153.59  5095.7  153.16  5124.1   154.8    5223  156.89
    5396  159.68  5427.2  160.94  5479.2  161.52  5491.7  161.12  5511.1  162.06
#Mann= 8 ,-1 , 0
  3943.7     .12       0  4451.7     .07       0  4476.3     .12       0
  4704.2     .07       0  4765.1     .12       0  5020.6     .05       0
  5025.9     .12       0    5223     .05       0
Bank Sta=5020.6,5025.9
XS Rating Curve= 0 ,0
Exp/Cntr=0.3,0.1

Type RM Length L Ch R = 1 ,9825    ,442,442,442
BEGIN DESCRIPTION:
Mapping XS 5e6b736b
END DESCRIPTION:
XS GIS Cut Line= 4
      2540493.56     13508711.93      2539969.52     13508740.58
      2539666.58      13508597.3      2539139.43     13508809.79
#Sta/Elev= 30
  4279.8  170.15  4325.2  168.16  4468.6  164.29  4598.8  157.85  4612.3   157.8
  4740.4  152.44  4808.8  150.84  4896.1  149.39  4931.3  147.63  4953.4  147.65
  4964.3  145.87  4975.6  141.43  4992.1  141.56  4995.5  140.44  4995.9  139.94
  5000.8  140.44    5011  141.02  5015.4  141.45  5022.1  143.29  5038.1  144.57
  5060.9  148.68  5097.2  150.65  5129.4  151.23  5236.6  152.97  5281.8  153.77
  5343.9  155.13  5529.6  157.35  5659.8  159.96  5669.8  159.64  5708.1  160.03
#Mann= 13 ,-1 , 0
  4279.8     .12       0  4325.2     .07       0  4740.4     .12       0
  4808.8     .07       0  4995.5     .05       0  5000.8     .07       0
    5011     .12       0  5022.1     .07       0  5129.4     .12       0
  5236.6    .035       0  5281.8     .12       0  5343.9    .035       0
  5669.8     .05       0
Bank Sta=4995.5,5000.8
XS Rating Curve= 0 ,0
Exp/Cntr=0.3,0.1

Type RM Length L Ch R = 1 ,9383    ,359,359,359
BEGIN DESCRIPTION:
Mapping XS dfd8d2fb
END DESCRIPTION:
XS GIS Cut Line= 4
      2540387.12       13508192.      2540039.12      13508265.7
      2539797.58     13508302.54      2539238.37     13508592.35
#Sta/Elev= 30
  4528.9  168.95  4567.2  168.86  4572.3  168.26  4666.5  166.95  4760.8  164.45
  4805.4  161.34  4837.7  160.06  4913.6  154.09  4919.1  151.67  4949.5  145.72
  4974.3  137.93  4974.7  137.43  4979.5  137.43    4980  137.93  5010.2  143.64
  5030.4  145.13  5040.5  145.28  5045.7  144.51  5050.7  145.26  5060.8   144.5
    5129  147.75  5154.4  147.28  5312.1  150.65  5346.1  150.99  5368.4  150.42
    5477  152.95  5578.3  154.96  5711.1  156.35  5741.3  157.31  5758.8  157.46
#Mann= 5 ,-1 , 0
  4528.9     .12       0  4974.3     .05       0    4980     .12       0
    5477    .035       0  5741.3     .05       0
Bank Sta=4974.3,4980
XS Rating Curve= 0 ,0
Exp/Cntr=0.3,0.1

Type RM Length L Ch R = 1 ,9024    ,512,512,512
BEGIN DESCRIPTION:
Mapping XS 8acdf6b3
END DESCRIPTION:
XS GIS Cut Line= 4
      2540407.61     13507925.91      2539899.93     13507930.01
      2539617.45     13508036.44      2539179.68     13508228.74
#Sta/Elev= 30
    4364   171.4  4396.6  170.36  4526.6   169.1  4546.6  167.94  4606.6  167.38
  4636.6  165.77  4736.6  162.99  4776.6  160.57  4796.6  160.14  4871.3  153.86
  4887.6  153.55  4919.7  148.32  4941.1   143.4  4956.9  142.72  4973.1  137.92
    4979  137.35  4979.4  136.85  4984.7  137.35  4994.5  140.29    5012   142.8
    5080  147.59  5144.1  146.49  5200.1  146.91  5231.4  147.73  5308.8  149.35
  5408.6  151.36  5461.8  153.31  5526.3  155.34    5635  159.19  5651.7  160.25
#Mann= 9 ,-1 , 0
    4364     .12       0    4979     .05       0  4984.7     .12       0
  5200.1     .07       0  5231.4     .12       0  5308.8     .07       0
  5461.8     .12       0  5526.3     .07       0    5635     .12       0
Bank Sta=4979,4984.7
XS Rating Curve= 0 ,0
Exp/Cntr=0.3,0.1

Type RM Length L Ch R = 1 ,8512    ,527,527,527
BEGIN DESCRIPTION:
Mapping XS 812463a3
END DESCRIPTION:
XS GIS Cut Line= 4
      2540297.07      13507741.7      2539633.83     13507545.18
      2539380.01      13507598.4      2538938.89     13507823.05
#Sta/Elev= 30
  4151.9  163.88    4197  162.81  4216.6  163.62  4230.3   162.2  4393.9  160.35
  4425.2  158.85  4456.5  159.15  4487.8  157.22  4688.5  150.68  4706.8  149.29
  4721.8  149.49  4826.7  143.87    4871  142.56  4924.2  140.87  4944.6  141.26
  4972.1  139.43  4985.5  137.29  4995.7  136.93    5003  135.12  5003.5  134.62
  5008.8  135.12  5017.3   138.1  5026.4  139.84  5073.1  141.84    5103  145.04
  5309.5  151.36  5343.8   151.5  5372.5  153.71    5455  155.37    5598  160.29
#Mann= 9 ,-1 , 0
  4151.9     .12       0    4871     .07       0  4944.6     .05       0
  4972.1     .07       0    5003     .05       0  5008.8     .07       0
  5073.1     .12       0  5309.5     .07       0  5372.5     .12       0
Bank Sta=5003,5008.8
XS Rating Curve= 0 ,0
Exp/Cntr=0.3,0.1

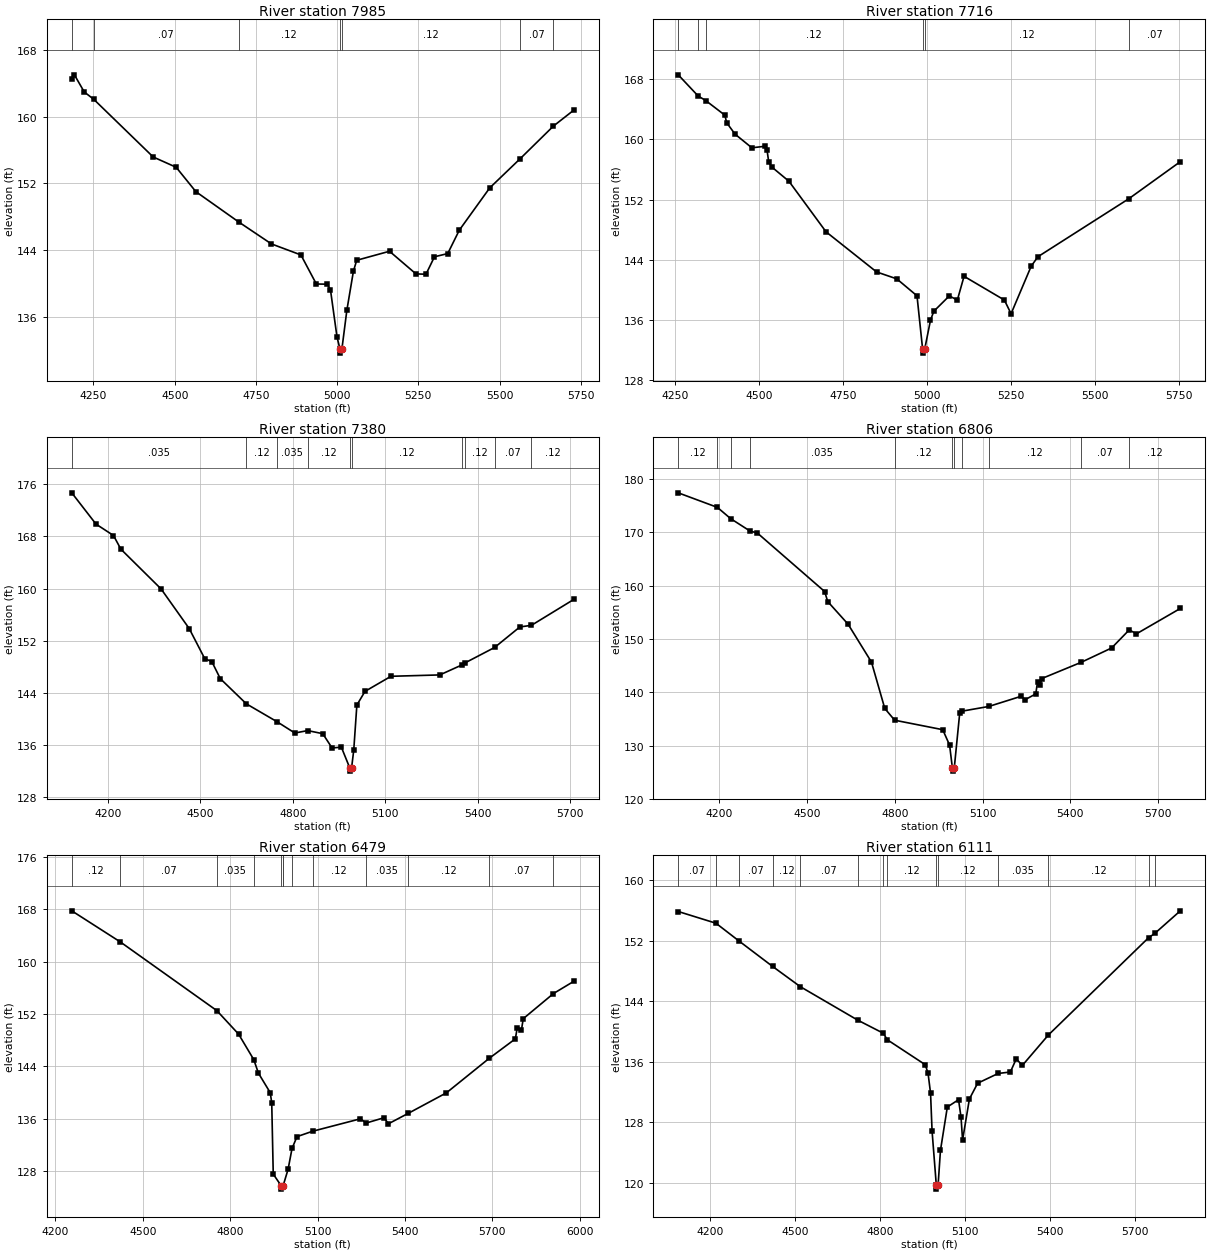
Type RM Length L Ch R = 1 ,7985    ,269,269,269
BEGIN DESCRIPTION:
Mapping XS 66cec7e2
END DESCRIPTION:
XS GIS Cut Line= 4
      2540383.03     13507250.43      2539732.08     13507156.27
      2539359.54     13507209.49      2538864.18      13507336.4
#Sta/Elev= 30
  4183.2  164.53  4191.3  164.99  4221.6  162.94  4250.9  162.06  4433.8  155.16
  4504.5  153.93  4565.2  151.01  4696.8  147.39  4797.6  144.76  4888.5  143.44
    4936  139.96  4969.3  139.94  4979.4  139.29  4999.6  133.62  5008.7  132.19
  5009.2  131.69  5014.7  132.19  5029.9  136.81  5050.1  141.49  5060.2   142.8
  5161.2  143.88  5242.6  141.17  5273.5  141.13  5299.6  143.22  5340.4   143.6
    5376   146.4  5469.7  151.46  5563.3  154.95  5665.5  158.85  5728.6  160.77
#Mann= 7 ,-1 , 0
  4183.2     .12       0  4250.9     .07       0  4696.8     .12       0
  5008.7     .05       0  5014.7     .12       0  5563.3     .07       0
  5665.5     .12       0
Bank Sta=5008.7,5014.7
XS Rating Curve= 0 ,0
Exp/Cntr=0.3,0.1

Type RM Length L Ch R = 1 ,7716    ,336,336,336
BEGIN DESCRIPTION:
Mapping XS 9af00751
END DESCRIPTION:
XS GIS Cut Line= 4
      2540313.42     13506972.05      2539580.61     13506910.64
      2539113.91     13506906.55      2538836.54     13507000.36
#Sta/Elev= 30
  4259.2  168.57  4318.7  165.75  4340.9  165.16  4398.1  163.21  4403.3  162.22
  4428.2   160.7  4478.4  158.88  4518.4  159.09  4523.4  158.64  4528.6     157
  4538.6   156.3  4588.8  154.44  4699.2  147.73  4849.7   142.4  4909.9  141.48
  4970.1  139.23  4986.9  132.12  4987.4  131.62  4992.9  132.12  5010.2  135.98
  5020.2  137.18  5066.4  139.22  5090.2  138.66  5110.2  141.82  5230.2  138.67
  5250.2  136.85  5310.2  143.17  5330.2  144.42  5600.5  152.11  5754.1  157.04
#Mann= 6 ,-1 , 0
  4259.2     .12       0  4318.7     .07       0  4340.9     .12       0
  4986.9     .05       0  4992.9     .12       0  5600.5     .07       0
Bank Sta=4986.9,4992.9
XS Rating Curve= 0 ,0
Exp/Cntr=0.3,0.1

Type RM Length L Ch R = 1 ,7380    ,574,574,574
BEGIN DESCRIPTION:
Mapping XS 1da22f61
END DESCRIPTION:
XS GIS Cut Line= 4
      2540292.97     13506562.66      2539556.04     13506656.82
      2539224.44     13506693.67      2538712.75     13506902.44
#Sta/Elev= 30
  4082.4  174.68    4161  169.89  4217.8  168.14  4241.7  166.05  4372.3  159.95
  4463.4  153.89  4513.8  149.28  4536.9  148.82  4564.3  146.21  4648.9  142.35
  4748.4  139.61  4806.2  137.88  4847.8  138.25  4896.8  137.78    4927  135.59
  4957.2  135.71  4984.4  132.54  4984.9  132.04  4990.4  132.54  4997.4  135.26
  5007.5  142.16  5033.9  144.26  5118.2  146.57  5276.7  146.78  5348.4  148.31
  5356.8  148.58  5454.6  150.99  5536.4  154.13    5574  154.38  5711.6  158.35
#Mann= 10 ,-1 , 0
  4082.4    .035       0  4648.9     .12       0  4748.4    .035       0
  4847.8     .12       0  4984.4     .05       0  4990.4     .12       0
  5348.4     .07       0  5356.8     .12       0  5454.6     .07       0
    5574     .12       0
Bank Sta=4984.4,4990.4
XS Rating Curve= 0 ,0
Exp/Cntr=0.3,0.1

Type RM Length L Ch R = 1 ,6806    ,327,327,327
BEGIN DESCRIPTION:
Mapping XS d03cb9fd
END DESCRIPTION:
XS GIS Cut Line= 4
      2540305.25     13506214.69      2539486.45     13506255.63
      2539249.01     13506357.97      2538720.87     13506718.25
#Sta/Elev= 30
  4058.9  177.44  4192.8  174.71  4238.1   172.6  4304.3  170.27  4329.5   169.9
  4559.8  158.91  4570.3  157.03  4639.9  152.78    4720  145.66  4765.5  136.96
  4799.3  134.75  4963.8  132.97  4987.3  130.07    4997  125.69  4997.5  125.19
  5003.1  125.69  5021.9   136.1  5030.9  136.46  5121.3  137.33  5231.3  139.23
  5246.2  138.62  5282.1  139.69  5288.1  141.93    5297  141.34  5303.1  142.58
  5437.5  145.62  5541.6  148.31  5601.9  151.71  5626.3  150.96  5776.6  155.73
#Mann= 11 ,-1 , 0
  4058.9     .12       0  4192.8    .035       0  4238.1     .07       0
  4304.3    .035       0  4799.3     .12       0    4997     .05       0
  5003.1     .12       0  5030.9    .035       0  5121.3     .12       0
  5437.5     .07       0  5601.9     .12       0
Bank Sta=4997,5003.1
XS Rating Curve= 0 ,0
Exp/Cntr=0.3,0.1

Type RM Length L Ch R = 1 ,6479    ,368,368,368
BEGIN DESCRIPTION:
Mapping XS a4dddc2e
END DESCRIPTION:
XS GIS Cut Line= 4
      2540174.22     13506022.28       2539584.7     13506050.94
      2539138.47       13506141.        2538594.     13506546.29
#Sta/Elev= 30
  4256.1  167.78  4422.9  163.02  4754.4  152.51    4829  148.92  4881.1  145.02
  4897.1  142.95  4937.7  139.96  4942.8  138.41    4948  127.51  4975.5  125.71
    4976  125.21  4981.7  125.71    4982  125.74    4999  128.25  5012.5  131.43
  5029.6  133.24  5082.9  134.06  5247.5  135.97  5267.1  135.32    5329  136.14
  5343.3   135.2  5412.4  136.82  5542.7  139.94  5689.7  145.22  5779.5   148.2
  5785.7  149.86  5800.3  149.54  5806.5  151.28  5910.4  155.13  5980.3     157
#Mann= 13 ,-1 , 0
  4256.1     .12       0  4422.9     .07       0  4754.4    .035       0
  4881.1     .07       0  4975.5     .05       0  4981.7     .07       0
    4982     .12       0  5012.5     .07       0  5082.9     .12       0
  5267.1    .035       0  5412.4     .12       0  5689.7     .07       0
  5910.4     .12       0
Bank Sta=4975.5,4981.7
XS Rating Curve= 0 ,0
Exp/Cntr=0.3,0.1

Type RM Length L Ch R = 1 ,6111    ,393,393,393
BEGIN DESCRIPTION:
Mapping XS 9d24595a
END DESCRIPTION:
XS GIS Cut Line= 4
      2540088.26     13505752.09      2539326.79     13505780.74
      2539060.69     13505887.18      2538471.18     13506308.85
#Sta/Elev= 30
  4087.2  155.88  4220.5  154.33  4301.5  151.99  4420.3  148.62  4518.8  145.93
  4720.8  141.52  4811.5  139.78  4825.5  138.92  4959.6  135.62  4969.6  134.49
  4978.4  131.85  4983.8  126.82  4998.8  119.66  4999.3  119.16    5005  119.66
  5013.4  124.28  5037.7  130.02  5077.3  130.99  5086.1  128.66  5091.5  125.65
  5115.7  131.09  5144.8  133.17  5217.3  134.46  5260.3  134.65  5281.2  136.39
  5302.6  135.52  5394.7  139.55  5748.7  152.42  5770.4  152.98  5860.6  155.97
#Mann= 14 ,-1 , 0
  4087.2     .07       0  4220.5     .12       0  4301.5     .07       0
  4420.3     .12       0  4518.8     .07       0  4720.8     .12       0
  4811.5     .07       0  4825.5     .12       0  4998.8     .05       0
    5005     .12       0  5217.3    .035       0  5394.7     .12       0
  5748.7     .05       0  5770.4     .12       0
Bank Sta=4998.8,5005
XS Rating Curve= 0 ,0
Exp/Cntr=0.3,0.1

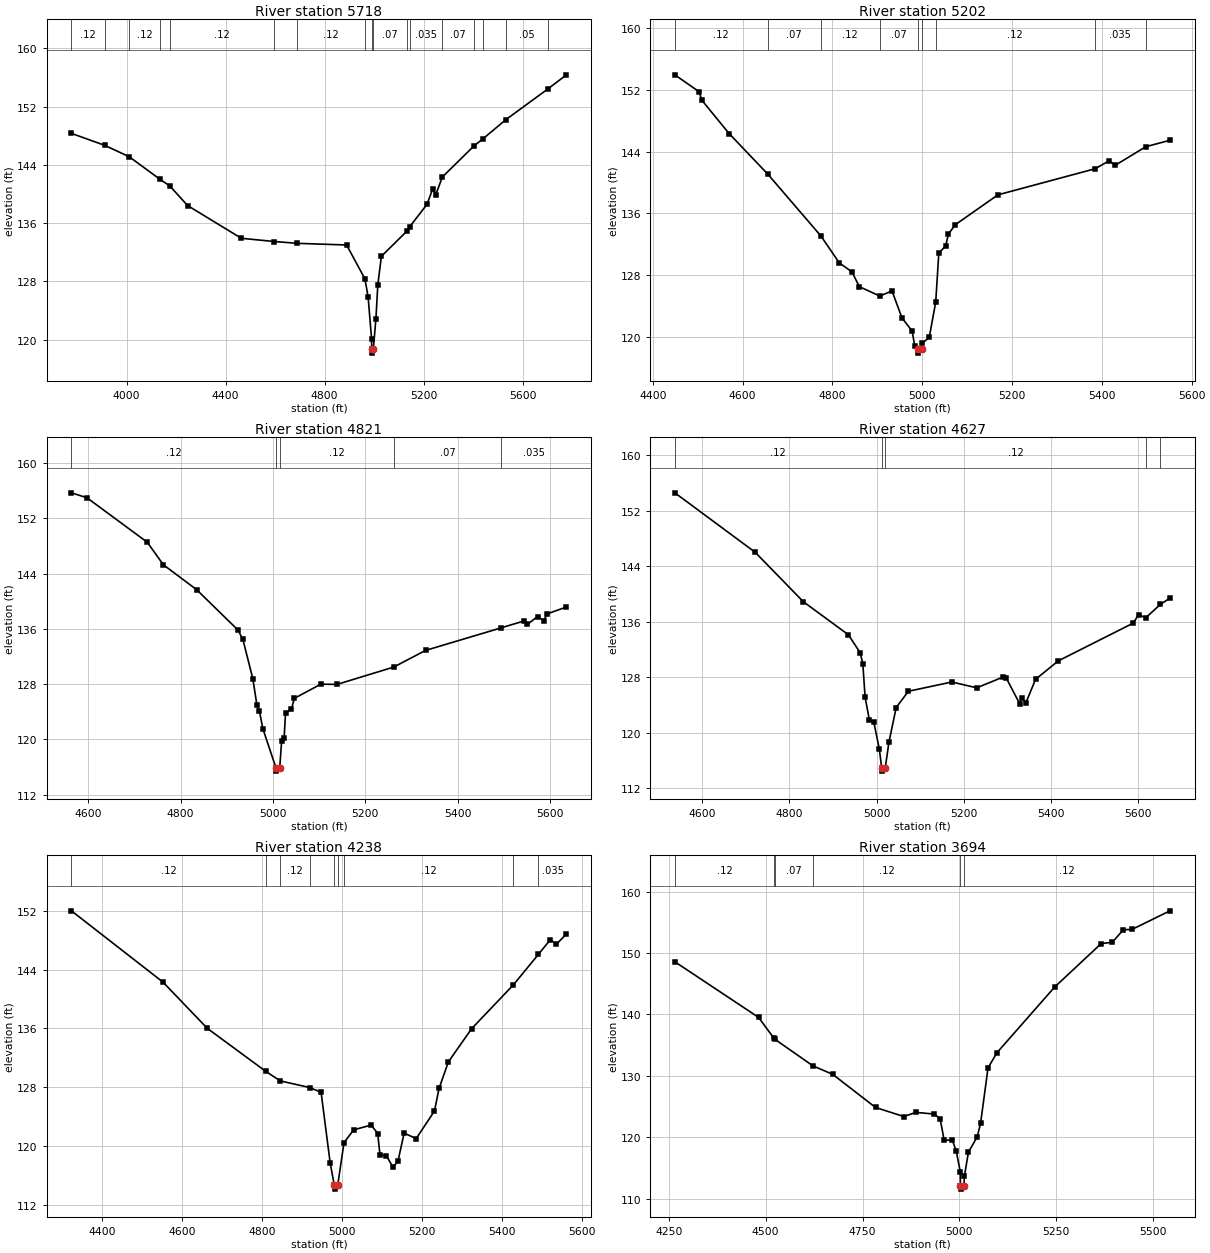
Type RM Length L Ch R = 1 ,5718    ,516,516,516
BEGIN DESCRIPTION:
Mapping XS b142550f
END DESCRIPTION:
XS GIS Cut Line= 4
      2540092.33     13505567.86      2539171.22     13505490.08
      2538892.84     13505588.33      2538280.26     13506070.23
#Sta/Elev= 30
  3777.3  148.34  3912.2  146.69  4010.7  145.13    4135  142.03  4174.7  141.12
  4246.3  138.43  4463.5  133.93  4596.1  133.49  4688.7  133.24  4888.6  133.01
  4962.5  128.36  4975.3  125.89  4989.3  120.16  4989.9  118.66  4990.4  118.16
  4996.2  118.66  5006.9  122.87  5014.5  127.52  5028.9  131.45  5131.6   134.9
  5142.7  135.49  5213.3   138.6  5235.9  140.69  5248.6  139.92  5275.2  142.35
  5403.1  146.62  5439.5   147.6  5531.1  150.21  5703.2  154.49  5776.3  156.38
#Mann= 17 ,-1 , 0
  3777.3     .12       0  3912.2    .035       0  4010.7     .12       0
    4135     .07       0  4174.7     .12       0  4596.1     .07       0
  4688.7     .12       0  4962.5     .07       0  4989.9     .05       0
  4996.2     .07       0  5131.6     .12       0  5142.7    .035       0
  5275.2     .07       0  5403.1     .05       0  5439.5     .07       0
  5531.1     .05       0  5703.2    .035       0
Bank Sta=4989.9,4996.2
XS Rating Curve= 0 ,0
Exp/Cntr=0.3,0.1

Type RM Length L Ch R = 1 ,5202    ,381,381,381
BEGIN DESCRIPTION:
Mapping XS 69647958
END DESCRIPTION:
XS GIS Cut Line= 3
      2539175.36     13504884.17      2538696.34     13505125.73
      2538401.57     13505608.82
#Sta/Elev= 30
  4449.2  153.97  4503.3  151.77  4508.9   150.7  4570.2  146.34  4655.7  141.12
  4774.2  133.09  4815.5  129.58  4843.4  128.43  4860.1   126.5  4905.6  125.29
  4932.7  125.96    4955  122.44  4977.3  120.78  4983.6  118.78  4990.1  118.39
  4990.6  117.89  4998.4  118.39  5000.1  119.17  5015.6  119.93  5030.1  124.52
  5036.9  130.86  5052.3  131.79  5058.2  133.33  5073.7  134.54  5168.5  138.41
  5384.7  141.79  5416.3  142.82    5430  142.25  5497.9  144.65  5551.6  145.49
#Mann= 9 ,-1 , 0
  4449.2     .12       0  4655.7     .07       0  4774.2     .12       0
  4905.6     .07       0  4990.1     .05       0  4998.4     .07       0
  5030.1     .12       0  5384.7    .035       0  5497.9     .07       0
Bank Sta=4990.1,4998.4
XS Rating Curve= 0 ,0
Exp/Cntr=0.3,0.1

Type RM Length L Ch R = 1 ,4821    ,194,194,194
BEGIN DESCRIPTION:
Mapping XS c31a6884
END DESCRIPTION:
XS GIS Cut Line= 3
      2538978.78      13504626.3      2538548.96     13504802.32
      2538164.15     13505273.09
#Sta/Elev= 30
  4563.3  155.69  4596.9  154.98  4727.7  148.53  4762.5  145.27  4834.5  141.67
    4924  135.83  4934.8  134.46  4956.4  128.75  4965.3   124.9  4970.7  124.05
    4978  121.54  5006.3  115.89  5006.8  115.39  5014.6  115.89  5018.7   119.7
  5024.1  120.18  5027.2  123.83  5039.8  124.33  5046.3  125.93  5103.7  127.98
  5138.9  127.95  5261.7  130.46  5330.5  132.87  5494.4  136.14  5544.5  137.15
  5550.9  136.63  5573.2  137.77  5586.6  137.19    5594  138.16  5635.8  139.16
#Mann= 5 ,-1 , 0
  4563.3     .12       0  5006.3     .05       0  5014.6     .12       0
  5261.7     .07       0  5494.4    .035       0
Bank Sta=5006.3,5014.6
XS Rating Curve= 0 ,0
Exp/Cntr=0.3,0.1

Type RM Length L Ch R = 1 ,4627    ,389,389,389
BEGIN DESCRIPTION:
Mapping XS 1618f053
END DESCRIPTION:
XS GIS Cut Line= 3
      2538901.05     13504523.93       2538458.9     13504659.03
      2537861.18     13504966.08
#Sta/Elev= 30
  4537.9  154.59    4722  146.02  4832.1  138.91  4935.7  134.13  4962.5  131.54
  4968.5     130  4973.7  125.18  4983.4  121.91  4993.9  121.52  5006.3  117.67
  5011.7     115  5012.2   114.5    5020     115  5028.5  118.72    5045  123.66
  5072.8     126  5172.5  127.34  5229.5   126.5  5289.1  128.03  5296.9  127.94
  5327.8  124.23  5333.4  125.05  5341.9  124.31  5364.4  127.73  5416.6  130.39
  5588.4  135.83  5600.5  137.06  5616.7  136.58  5650.1  138.51  5672.2  139.42
#Mann= 5 ,-1 , 0
  4537.9     .12       0  5011.7     .05       0    5020     .12       0
  5616.7    .035       0  5650.1     .12       0
Bank Sta=5011.7,5020
XS Rating Curve= 0 ,0
Exp/Cntr=0.3,0.1

Type RM Length L Ch R = 1 ,4238    ,544,544,544
BEGIN DESCRIPTION:
Mapping XS b31779ea
END DESCRIPTION:
XS GIS Cut Line= 4
      2538802.78     13504315.15      2538299.24     13504368.37
      2537959.45      13504548.5      2537660.57     13504724.55
#Sta/Elev= 30
  4322.9  151.99  4551.9  142.29  4662.6  136.01  4808.5  130.17  4845.1  128.86
  4918.5  127.96  4947.2  127.31  4969.9   117.7  4980.3  114.64  4980.8  114.14
  4988.7  114.64  5004.4  120.45  5028.5   122.2  5072.5  122.85  5088.8   121.7
  5094.5  118.75  5110.3  118.71  5127.1  117.09  5139.6  117.99  5154.8  121.76
  5184.9  121.01  5230.6  124.76  5242.2  127.84  5265.4  131.44  5323.4  135.95
    5428  141.92  5490.6  146.07  5520.7  148.09  5535.1  147.42  5560.7  148.84
#Mann= 9 ,-1 , 0
  4322.9     .12       0  4808.5     .07       0  4845.1     .12       0
  4918.5     .07       0  4980.3     .05       0  4988.7     .07       0
  5004.4     .12       0    5428     .07       0  5490.6    .035       0
Bank Sta=4980.3,4988.7
XS Rating Curve= 0 ,0
Exp/Cntr=0.3,0.1

Type RM Length L Ch R = 1 ,3694    ,507,507,507
BEGIN DESCRIPTION:
Mapping XS 508969b8
END DESCRIPTION:
XS GIS Cut Line= 4
      2538679.95     13504208.71      2538172.33     13504155.49
      2537812.07     13504049.05      2537455.87     13504212.82
#Sta/Elev= 30
  4265.6  148.57  4481.7  139.52  4521.5  136.11  4523.6  135.97  4622.1  131.63
  4672.8  130.27  4783.6  124.87  4856.6  123.39  4887.9  124.07  4935.7  123.79
  4950.5  122.99  4960.9  119.52  4981.8  119.59  4992.2  117.72  5002.3  114.44
    5003  112.08  5003.5  111.58  5011.9  112.08    5013  113.66  5023.5   117.6
    5046  120.06  5054.8  122.28  5074.1   131.3  5096.5  133.73  5245.8  144.44
  5366.2  151.53  5394.7  151.74  5423.6  153.78  5446.1  153.84  5543.7  156.86
#Mann= 6 ,-1 , 0
  4265.6     .12       0  4521.5    .035       0  4523.6     .07       0
  4622.1     .12       0    5003     .05       0  5011.9     .12       0
Bank Sta=5003,5011.9
XS Rating Curve= 0 ,0
Exp/Cntr=0.3,0.1

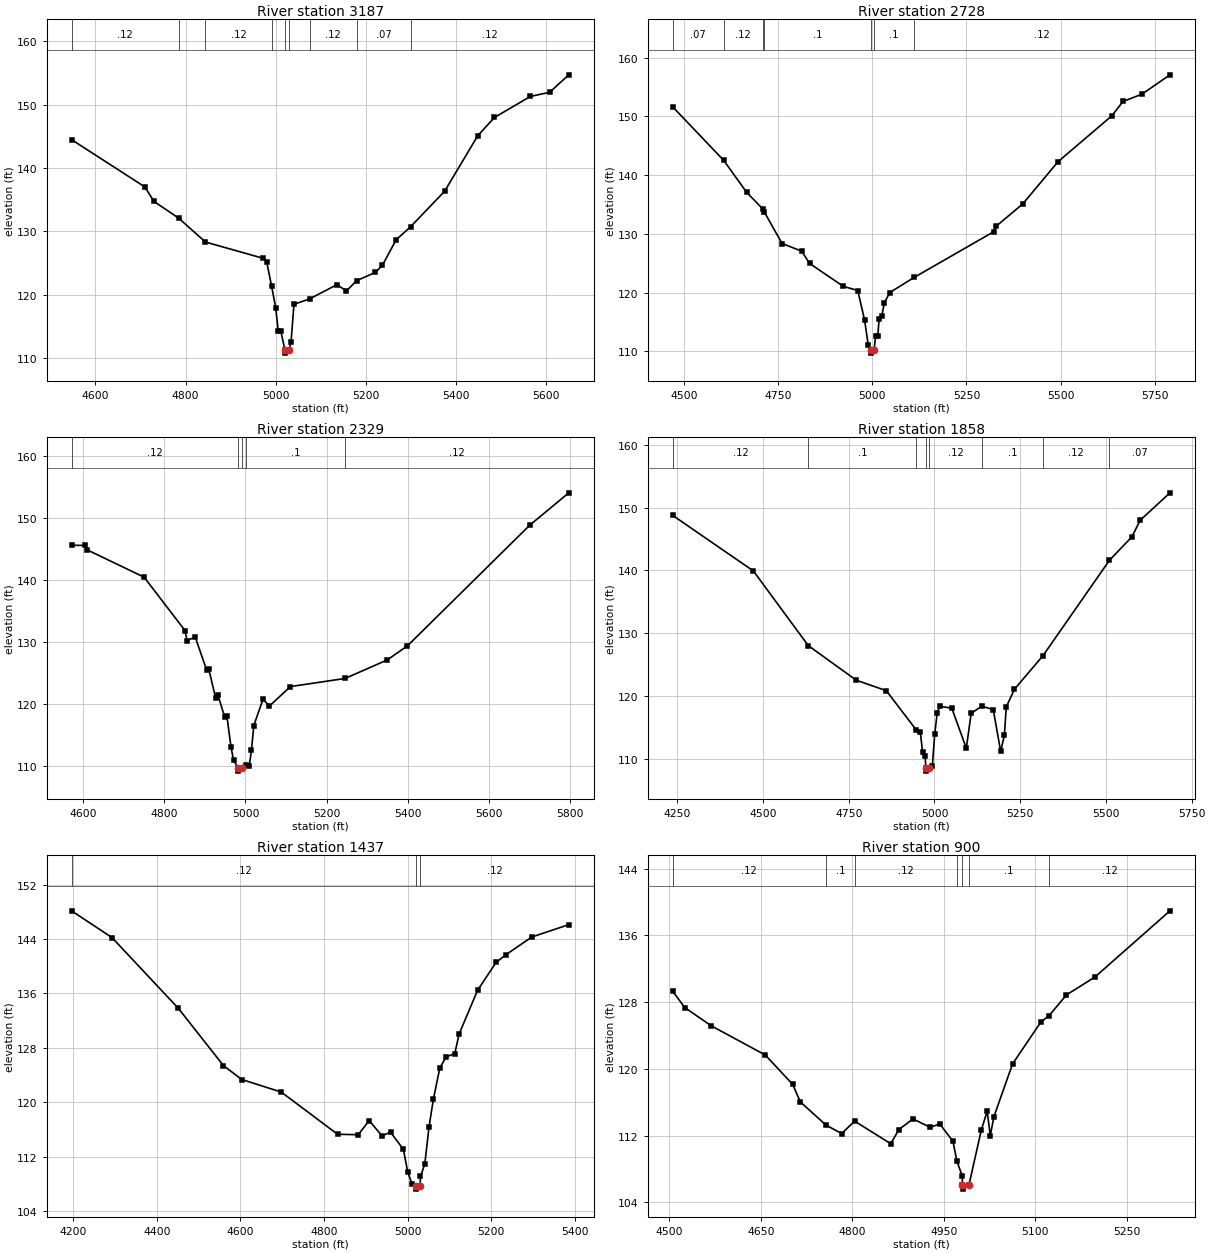
Type RM Length L Ch R = 1 ,3187    ,459,459,459
BEGIN DESCRIPTION:
Mapping XS 888f0d7b
END DESCRIPTION:
XS GIS Cut Line= 3
       2538577.6     13503627.39      2538119.11     13503651.95
      2537566.41     13503983.57
#Sta/Elev= 30
  4546.8  144.49  4709.6  137.02  4729.7  134.73  4784.5   132.1  4844.1  128.32
  4972.3  125.75    4980   125.2  4990.9  121.34  5000.1  117.89  5005.5  114.27
  5011.3  114.27  5020.4  111.28  5020.9  110.78  5029.4  111.28  5034.1  112.59
  5040.5  118.49    5075  119.34  5135.7  121.58  5157.1  120.61  5179.8  122.23
  5221.2  123.52  5236.8  124.65  5267.3  128.68  5299.2  130.72  5374.8  136.33
  5448.6  145.12  5485.6  147.99  5565.3  151.31    5608  151.96  5650.5  154.72
#Mann= 9 ,-1 , 0
  4546.8     .12       0  4784.5      .1       0  4844.1     .12       0
  4990.9     .07       0  5020.4     .05       0  5029.4     .07       0
    5075     .12       0  5179.8     .07       0  5299.2     .12       0
Bank Sta=5020.4,5029.4
XS Rating Curve= 0 ,0
Exp/Cntr=0.3,0.1

Type RM Length L Ch R = 1 ,2728    ,399,399,399
BEGIN DESCRIPTION:
Mapping XS c1b377ef
END DESCRIPTION:
XS GIS Cut Line= 4
      2538483.49     13503119.74      2537963.54     13503275.32
      2537693.35     13503533.23      2537460.01     13503864.81
#Sta/Elev= 30
  4469.2  151.61  4604.6  142.51  4665.9  137.05  4708.1  134.26  4712.6  133.72
  4759.9  128.34  4812.1  127.04    4833  124.95  4922.6  121.05    4961  120.34
  4979.1  115.35  4988.8  111.13  4995.4  110.18  4995.9  109.68  5004.5  110.18
  5008.5  112.61  5014.4  112.61  5017.8  115.47  5024.7  115.98  5031.9  118.24
  5046.1  119.99    5111  122.57  5321.9  130.33  5328.8  131.28  5399.8  135.09
  5493.5  142.28  5636.4  150.08    5666  152.52  5716.5  153.77  5790.9  157.06
#Mann= 7 ,-1 , 0
  4469.2     .07       0  4604.6     .12       0  4708.1     .07       0
  4712.6      .1       0  4995.4     .05       0  5004.5      .1       0
    5111     .12       0
Bank Sta=4995.4,5004.5
XS Rating Curve= 0 ,0
Exp/Cntr=0.3,0.1

Type RM Length L Ch R = 1 ,2329    ,471,471,471
BEGIN DESCRIPTION:
Mapping XS b14f11a3
END DESCRIPTION:
XS GIS Cut Line= 4
      2538160.04     13502882.31      2537865.29     13502943.72
      2537681.07     13503299.88      2537423.14     13503754.32
#Sta/Elev= 30
  4571.7  145.62  4605.9  145.58    4611  144.85  4750.5  140.46  4851.1  131.85
  4856.2  130.23  4876.3   130.8  4904.2   125.5  4909.8   125.6  4926.4  120.99
    4932  121.51  4948.5  117.94  4954.1  118.12  4964.3  113.12  4970.6  110.93
  4982.3  109.65  4982.8  109.15  4991.4  109.65  5002.5  110.17  5009.3   109.9
  5014.9  112.59  5020.6  116.51  5043.1  120.74  5059.2  119.67  5110.7   122.8
  5245.3  124.11  5348.6  127.08  5398.9  129.37  5700.4  148.87  5796.3  154.08
#Mann= 5 ,-1 , 0
  4571.7     .12       0  4982.3     .05       0  4991.4     .12       0
  5002.5      .1       0  5245.3     .12       0
Bank Sta=4982.3,4991.4
XS Rating Curve= 0 ,0
Exp/Cntr=0.3,0.1

Type RM Length L Ch R = 1 ,1858    ,421,421,421
BEGIN DESCRIPTION:
Mapping XS 88482850
END DESCRIPTION:
XS GIS Cut Line= 4
        2538070.     13502792.24      2537513.22      13502820.9
      2537247.12     13503078.81      2537046.93     13503560.91
#Sta/Elev= 30
  4236.6  148.78  4471.9  139.92  4631.9  128.02  4771.9   122.5  4859.5  120.83
  4947.1  114.55  4958.5  114.28  4965.5  110.99  4972.7  110.41    4975   108.5
  4975.5     108  4984.2   108.5  4993.8  108.83  5000.7   113.9  5007.9  117.25
  5014.9  118.33  5050.4  118.05  5092.8  111.66    5107  117.21  5137.7  118.35
  5171.4  117.82    5193  111.14  5203.9  113.72  5209.3  118.23  5233.2  121.06
  5316.7  126.43  5509.9   141.6  5575.9  145.38  5599.8     148  5686.7  152.38
#Mann= 8 ,-1 , 0
  4236.6     .12       0  4631.9      .1       0  4947.1     .12       0
    4975     .05       0  4984.2     .12       0  5137.7      .1       0
  5316.7     .12       0  5509.9     .07       0
Bank Sta=4975,4984.2
XS Rating Curve= 0 ,0
Exp/Cntr=0.3,0.1

Type RM Length L Ch R = 1 ,1437    ,537,537,537
BEGIN DESCRIPTION:
Mapping XS 260d7cf3
END DESCRIPTION:
XS GIS Cut Line= 3
      2537967.64     13502693.99      2537365.84     13502603.93
      2536798.41      13502726.4
#Sta/Elev= 30
  4196.2  148.14  4292.8  144.22  4451.7  133.81  4559.4  125.41  4603.3  123.36
  4697.7  121.52  4832.3  115.32  4881.6  115.25  4907.9  117.33  4938.6  115.08
    4959  115.63  4989.7   113.1  4999.9  109.84  5010.2  108.01    5019  107.76
  5019.5  107.26  5029.6  107.76  5030.6  109.12  5040.9  110.95  5051.1  116.44
  5061.3  120.43  5076.7  125.03    5092   126.7  5112.5  127.15  5122.8  130.01
    5167  136.46  5211.2  140.55  5235.2  141.71  5296.6  144.29  5385.2  146.11
#Mann= 3 ,-1 , 0
  4196.2     .12       0    5019     .05       0  5029.6     .12       0
Bank Sta=5019,5029.6
XS Rating Curve= 0 ,0
Exp/Cntr=0.3,0.1

Type RM Length L Ch R = 1 ,900     ,555,555,555
BEGIN DESCRIPTION:
Mapping XS e9c9a8c7
END DESCRIPTION:
XS GIS Cut Line= 3
      2537766.64     13502400.21      2537349.97     13502160.62
      2537024.61     13502240.23
#Sta/Elev= 30
  4505.5  129.31  4525.3  127.36  4568.5  125.18  4657.4  121.67  4702.1  118.17
    4715  116.04    4757  113.27  4782.6  112.26  4803.9  113.75  4863.1  111.04
  4876.5  112.74  4899.6  114.01  4927.8  113.01  4943.6  113.41  4965.2  111.33
  4971.5     109  4980.3  107.19  4980.8   106.1  4981.3   105.6  4991.4   106.1
  5011.8  112.72  5021.3  114.93  5026.4  112.02  5032.4  114.29  5062.9   120.6
  5109.7  125.66  5122.4  126.35  5151.3  128.87  5198.1  131.02  5321.1  138.95
#Mann= 7 ,-1 , 0
  4505.5     .12       0    4757      .1       0  4803.9     .12       0
  4971.5      .1       0  4980.8     .05       0  4991.4      .1       0
  5122.4     .12       0
Bank Sta=4980.8,4991.4
XS Rating Curve= 0 ,0
Exp/Cntr=0.3,0.1