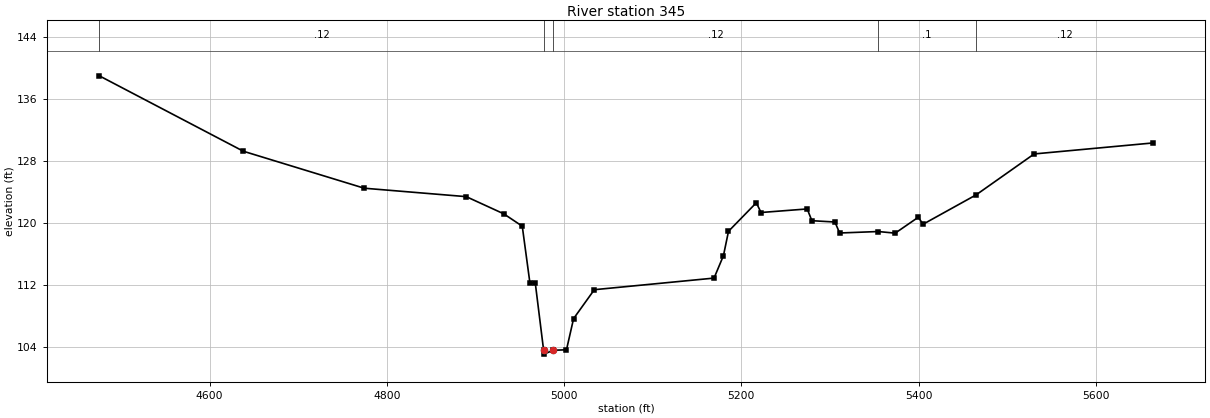
HEC-RAS study TRIB 5A TO COLETO CREEK.prj: TRIB 5A TO COLETO CREEK Base Level Engineering

--- TRIB 5A TO COLETO CREEK.g01 (geometry) --- (continued)

Type RM Length L Ch R = 1 ,345     ,0,0,0
BEGIN DESCRIPTION:
TRIB 5A TO COLETO CREEK 1.0
END DESCRIPTION:
XS GIS Cut Line= 3
      2538152.07     13502174.52      2537725.15     13501869.99
      2537096.46     13502084.25
#Sta/Elev= 30
  4475.6  139.02  4638.1  129.27  4774.5  124.49  4889.6   123.4  4931.9  121.18
  4952.8  119.58  4961.4  112.27  4967.5  112.22  4976.9  103.54  4977.4  103.04
  4987.6  103.54  5002.7   103.6  5010.7  107.63  5034.1  111.37  5169.2  112.87
  5179.8  115.77  5185.5  118.92  5216.9  122.61  5222.2  121.35  5274.3  121.81
  5279.6  120.29  5305.6  120.12  5310.9   118.7  5354.4  118.89  5373.6  118.68
  5399.7  120.74    5405  119.83  5464.9  123.63  5530.4  128.92  5664.2  130.34
#Mann= 5 ,-1 , 0
  4475.6     .12       0  4976.9     .05       0  4987.6     .12       0
  5354.4      .1       0  5464.9     .12       0
Bank Sta=4976.9,4987.6
XS Rating Curve= 0 ,0
Exp/Cntr=0.3,0.1

Chan Stop Cuts=-1
Use User Specified Reach Order=0
Composite Channel Slope=5