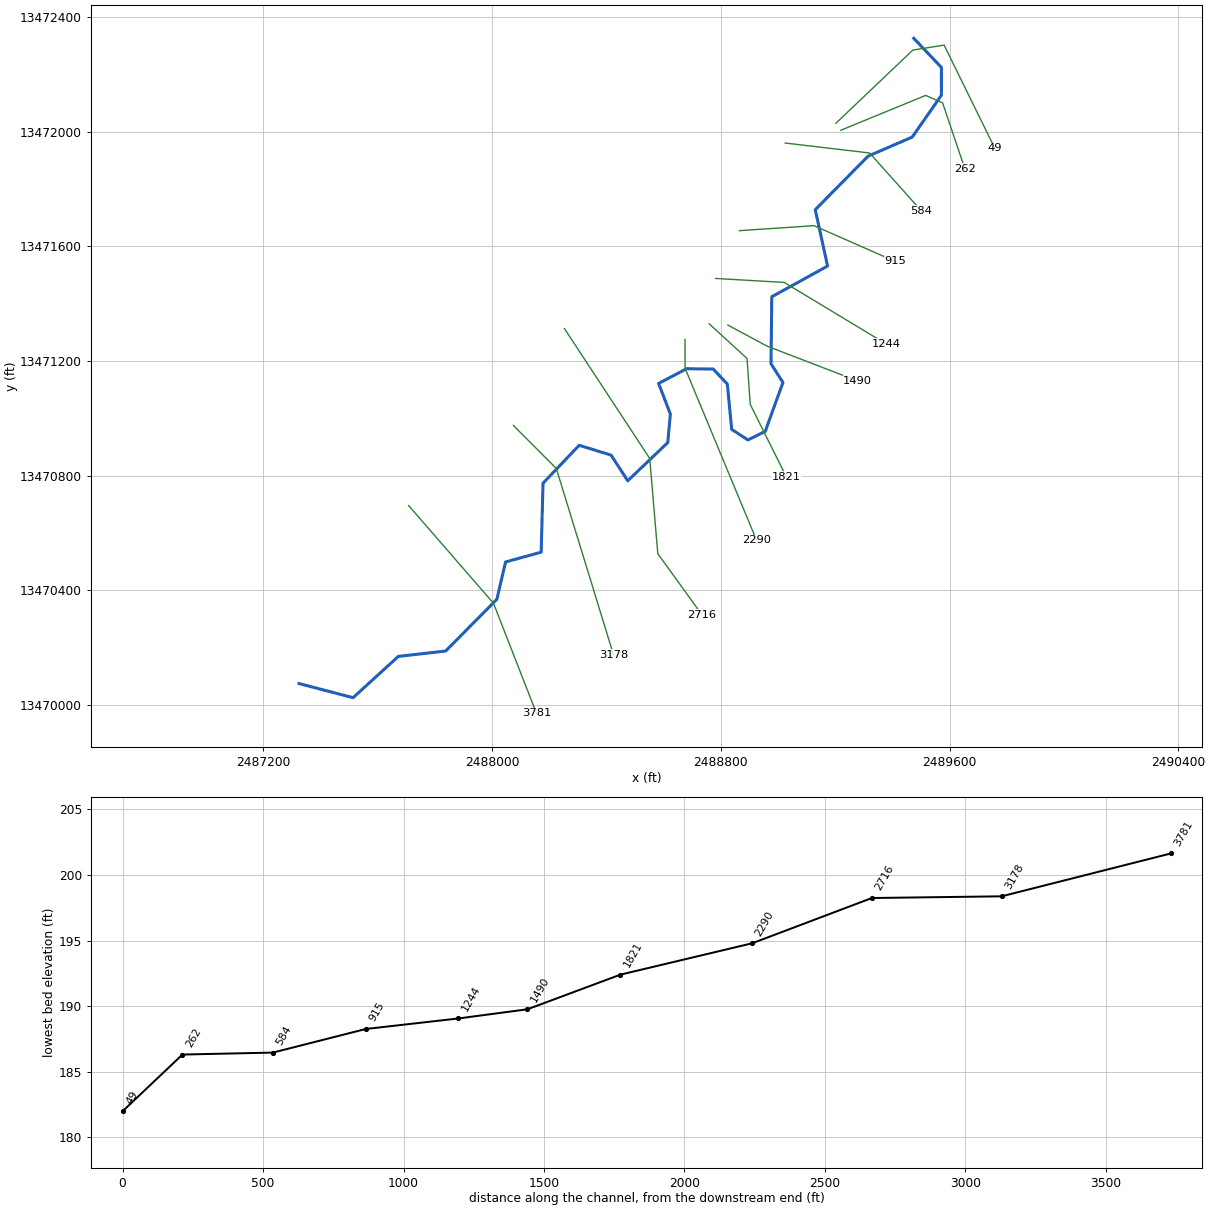
--- TRIB 5A TO PERDIDO CREEK.prj (project) ---

Proj Title=TRIB 5A TO PERDIDO CREEK Base Level Engineering
Current Plan=p01
Default Exp/Contr=0.3,0.1
English Units
Geom File=g01
Flow File=f01
Plan File=p01
Y Axis Title=Elevation
X Axis Title(PF)=Main Channel Distance
X Axis Title(XS)=Station
BEGIN DESCRIPTION:
TRIB 5A TO PERDIDO CREEK
END DESCRIPTION:
DSS Export Rating Curves= 0
DSS Export Rating Curve Sorted= 0
DSS Export Volume Flow Curves= 0
DXF OffsetX= 0
DXF OffsetY= 0
DXF ScaleX= 1
DXF ScaleY= 10

--- TRIB 5A TO PERDIDO CREEK.p01 (plan) ---

Plan Title=Multiple Run
Short Identifier=Multiple
Geom File=g01
Flow File=f01
Subcritical Flow
K Sum by GR= 0
Std Step Tol= 0.01
Critical Tol= 0.01
Num of Std Step Trials= 20
Max Error Tol= 0.3
Flow Tol Ratio= 0.001
Split Flow NTrial= 30
Split Flow Tol= 0.02
Split Flow Ratio= 0.02
Log Output Level= 0
Friction Slope Method= 1
Unsteady Friction Slope Method= 2
Unsteady Bridges Friction Slope Method= 1
Parabolic Critical Depth
Global Vel Dist=  1 , 1 , 1
Global Log Level= 0
CheckData=True
Encroach Param= -1, 0, 0, 0
BEGIN DESCRIPTION:
Multiple Run
END DESCRIPTION:

--- TRIB 5A TO PERDIDO CREEK.f01 (steady flow) ---

Flow Title=Multiple
Number of Profiles=7
Profile Names=10-year,25-year,50-year,1pct_min,100-year,1pct_plu,500-year
River Rch & RM= TRIB 5A TO PERDI,Reach-1,3781
    1078    1787    2443    1614    3221    6427    5544
Boundary for River Rch & Prof#=TRIB 5A TO PERDI,Reach-1,1
Up Type=0
Dn Type=3
Dn Slope=0.005
Boundary for River Rch & Prof#=TRIB 5A TO PERDI,Reach-1,2
Up Type=0
Dn Type=3
Dn Slope=0.005
Boundary for River Rch & Prof#=TRIB 5A TO PERDI,Reach-1,3
Up Type=0
Dn Type=3
Dn Slope=0.005
Boundary for River Rch & Prof#=TRIB 5A TO PERDI,Reach-1,4
Up Type=0
Dn Type=3
Dn Slope=0.005
Boundary for River Rch & Prof#=TRIB 5A TO PERDI,Reach-1,5
Up Type=0
Dn Type=3
Dn Slope=0.005
Boundary for River Rch & Prof#=TRIB 5A TO PERDI,Reach-1,6
Up Type=0
Dn Type=3
Dn Slope=0.005
Boundary for River Rch & Prof#=TRIB 5A TO PERDI,Reach-1,7
Up Type=0
Dn Type=3
Dn Slope=0.005

--- TRIB 5A TO PERDIDO CREEK.g01 (geometry) ---

Geom Title=Existing Conditions
Program Version=4.10

River Reach=TRIB 5A TO PERDI,Reach-1
Reach XY= 30
        2487325.       13470075.      2487514.38     13470025.59
      2487672.55     13470169.53      2487838.32     13470188.37
      2488017.14     13470368.83      2488047.69       13470499.
      2488172.06     13470532.97      2488178.54     13470773.54
      2488304.98     13470905.72       2488416.5     13470871.48
       2488474.8     13470782.01      2488614.57     13470915.21
      2488623.87     13471014.47      2488582.72      13471121.5
      2488680.94     13471172.87      2488773.75     13471171.64
      2488823.02     13471119.35      2488838.23     13470961.19
      2488895.12     13470924.45      2488955.53     13470954.24
      2489017.44       13471125.      2488975.66     13471190.16
      2488978.44     13471423.78      2489173.47     13471530.83
       2489130.4     13471727.43      2489315.32     13471914.23
      2489469.39     13471980.59      2489571.53      13472126.5
       2489571.6     13472223.52        2489475.       13472325.

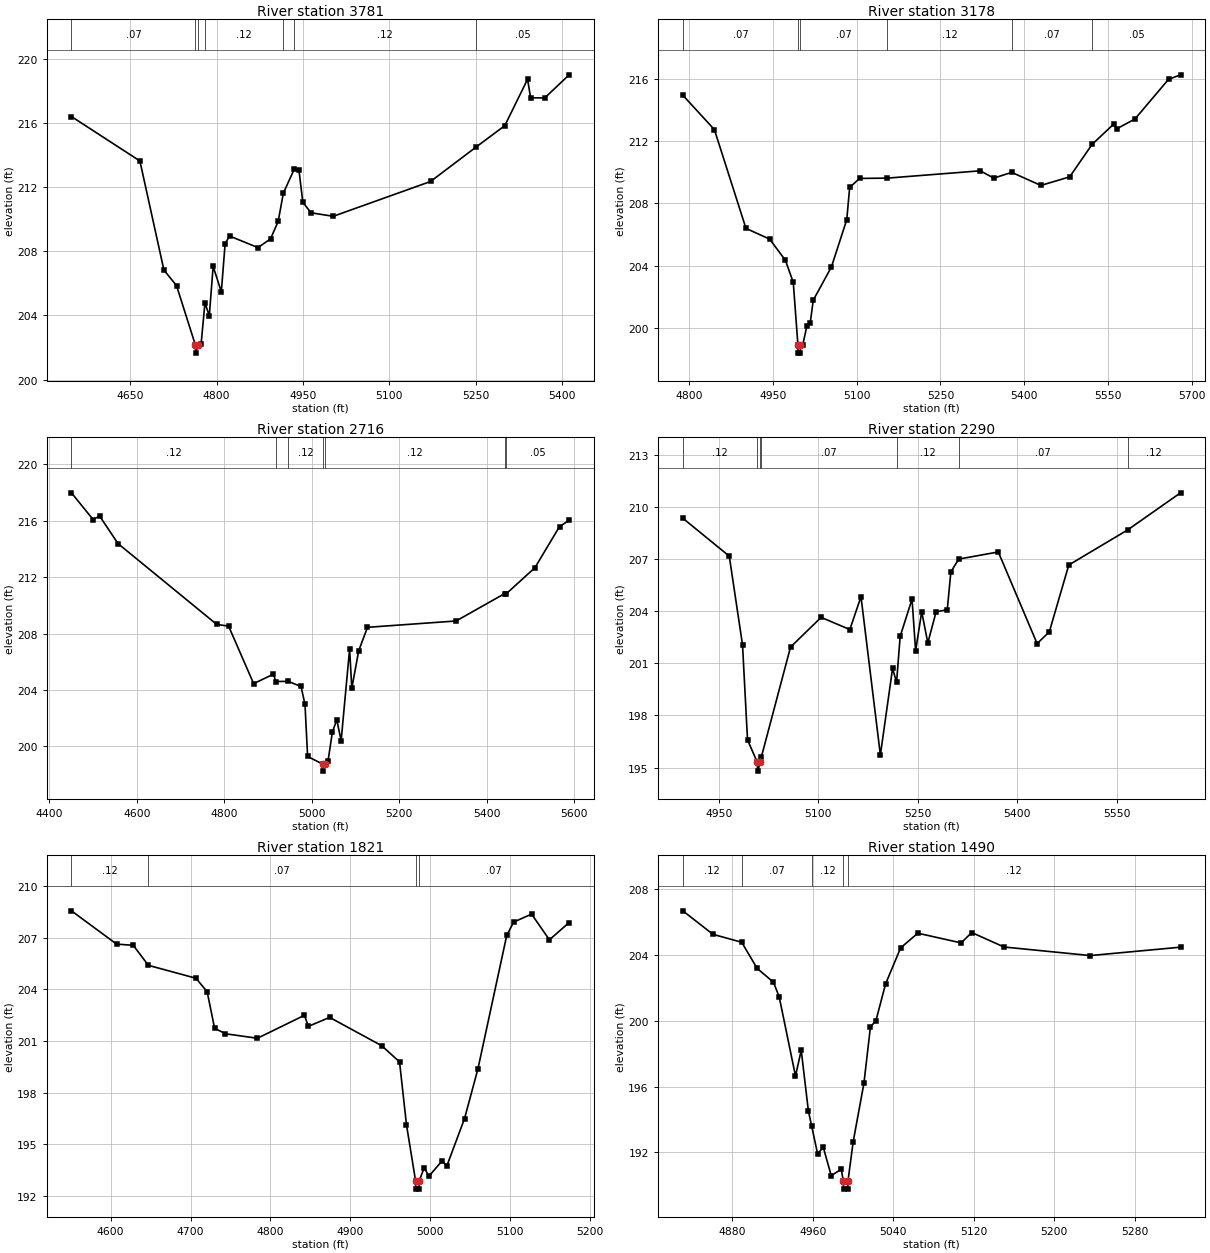
Type RM Length L Ch R = 1 ,3781    ,603,603,603
BEGIN DESCRIPTION:
TRIB 5A TO PERDIDO CREEK 8.0
END DESCRIPTION:
XS GIS Cut Line= 3
      2487708.55     13470695.72      2488005.37     13470354.85
       2488155.6     13469970.89
#Sta/Elev= 30
    4548   216.4  4666.9  213.63  4708.6  206.83  4730.5  205.86  4763.3  202.15
  4763.7  201.65  4767.8  202.15  4773.2  202.22  4779.9  204.79  4787.4  203.97
  4794.1  207.06  4808.3  205.47  4814.9  208.48  4822.6  208.95  4871.9  208.23
  4893.7  208.77    4907  209.86    4916  211.62  4935.3  213.15  4943.1  213.06
  4949.8  211.06    4964   210.4  5002.6  210.18  5171.6  212.35  5250.8   214.5
  5300.5  215.83  5340.1  218.72  5345.4  217.57  5369.9  217.56  5412.3     219
#Mann= 7 ,-1 , 0
    4548     .07       0  4763.3     .05       0  4767.8     .07       0
  4779.9     .12       0    4916     .07       0  4935.3     .12       0
  5250.8     .05       0
Bank Sta=4763.3,4767.8
XS Rating Curve= 0 ,0
Exp/Cntr=0.3,0.1

Type RM Length L Ch R = 1 ,3178    ,462,462,462
BEGIN DESCRIPTION:
TRIB 5A TO PERDIDO CREEK 7.0
END DESCRIPTION:
XS GIS Cut Line= 3
      2488074.97     13470975.03        2488225.       13470825.
      2488424.99     13470175.05
#Sta/Elev= 30
  4788.1  214.96  4844.7  212.75  4901.3   206.4  4943.7  205.71    4972  204.35
  4986.1  202.93  4994.5  198.88  4994.8  198.38  4998.7  198.38    4999  198.88
  5002.9  198.88  5010.7  200.15  5016.6  200.34  5021.9  201.78  5054.5  203.92
    5082  206.96  5087.2  209.03  5104.9  209.61  5154.7  209.63  5321.3   210.1
  5345.5  209.63  5377.7     210  5429.9  209.16  5481.6  209.71  5521.8   211.8
  5560.7  213.11  5565.9   212.8  5598.6  213.43  5658.8  215.98  5680.3  216.27
#Mann= 6 ,-1 , 0
  4788.1     .07       0  4994.5     .05       0    4999     .07       0
  5154.7     .12       0  5377.7     .07       0  5521.8     .05       0
Bank Sta=4994.5,4999
XS Rating Curve= 0 ,0
Exp/Cntr=0.3,0.1

Type RM Length L Ch R = 1 ,2716    ,426,426,426
BEGIN DESCRIPTION:
Mapping XS 26a956dd
END DESCRIPTION:
XS GIS Cut Line= 4
      2488253.59     13471312.56      2488551.66     13470859.83
      2488579.78     13470528.05      2488734.43     13470314.35
#Sta/Elev= 30
  4450.2  217.97  4499.7  216.08  4514.8  216.32  4556.9  214.37  4782.5  208.65
  4809.9  208.52  4867.1  204.45  4912.4  205.12  4917.8   204.6  4946.3  204.61
  4975.5  204.25  4984.6  202.98  4990.6  199.29  5024.9  198.75  5025.2  198.25
  5029.5  198.75  5037.2  198.94  5047.3  201.02  5057.3  201.89  5067.3  200.41
  5086.7   206.9  5091.7  204.12  5107.5  206.78  5127.6  208.44  5330.4  208.89
  5441.5  210.83  5445.2  210.82  5510.6  212.66    5567  215.58    5589  216.02
#Mann= 7 ,-1 , 0
  4450.2     .12       0  4917.8     .07       0  4946.3     .12       0
  5024.9     .05       0  5029.5     .12       0  5441.5     .07       0
  5445.2     .05       0
Bank Sta=5024.9,5029.5
XS Rating Curve= 0 ,0
Exp/Cntr=0.3,0.1

Type RM Length L Ch R = 1 ,2290    ,469,469,469
BEGIN DESCRIPTION:
TRIB 5A TO PERDIDO CREEK 5.0
END DESCRIPTION:
XS GIS Cut Line= 3
        2488675.     13471275.02        2488675.       13471175.
      2488924.99     13470575.02
#Sta/Elev= 30
    4896  209.34    4966  207.16    4986  202.05  4993.5   196.6  5008.3   195.3
  5008.6   194.8  5012.9   195.3  5014.2  195.59  5058.3  201.93  5104.4  203.64
  5147.7  202.94  5164.5  204.83  5193.7  195.73  5212.1  200.71  5218.1   199.9
  5223.5  202.54  5241.4  204.69  5246.8  201.72    5256  203.96  5265.2  202.17
  5277.7  203.96  5294.5  204.08  5299.9  206.25  5311.7  206.99  5371.4   207.4
  5429.9  202.13  5448.3  202.81  5477.6  206.65  5566.4  208.67    5646   210.8
#Mann= 7 ,-1 , 0
    4896     .12       0  5008.3     .05       0  5012.9     .12       0
  5014.2     .07       0  5218.1     .12       0  5311.7     .07       0
  5566.4     .12       0
Bank Sta=5008.3,5012.9
XS Rating Curve= 0 ,0
Exp/Cntr=0.3,0.1

Type RM Length L Ch R = 1 ,1821    ,331,331,331
BEGIN DESCRIPTION:
Mapping XS cc2dad02
END DESCRIPTION:
XS GIS Cut Line= 4
      2488759.72      13471329.4      2488891.88     13471208.49
      2488903.13     13471048.22      2489029.65     13470795.18
#Sta/Elev= 30
    4551  208.55  4607.5  206.62  4628.4  206.55  4647.2  205.39  4706.8  204.64
  4720.8  203.86  4730.1  201.74  4743.7  201.42  4783.7  201.16  4842.5  202.49
  4847.5  201.85    4874  202.37  4939.1  200.73  4961.5  199.79  4970.2  196.14
  4981.5  192.91  4981.8  192.41  4985.8  192.41  4986.2  192.91  4992.5  193.66
  4998.1  193.15  5014.9  194.06  5020.5  193.73  5042.8   196.5  5059.6  199.39
  5095.6  207.12  5104.3   207.9  5126.7  208.36    5149  206.87  5173.7  207.87
#Mann= 4 ,-1 , 0
    4551     .12       0  4647.2     .07       0  4981.5     .05       0
  4986.2     .07       0
Bank Sta=4981.5,4986.2
XS Rating Curve= 0 ,0
Exp/Cntr=0.3,0.1

Type RM Length L Ch R = 1 ,1490    ,246,246,246
BEGIN DESCRIPTION:
TRIB 5A TO PERDIDO CREEK 3.0
END DESCRIPTION:
XS GIS Cut Line= 3
      2488825.04     13471324.98      2488961.78     13471251.63
      2489278.78     13471130.02
#Sta/Elev= 30
  4830.9  206.69  4860.9  205.26  4889.4  204.78  4904.8  203.19    4921  202.35
  4926.7  201.46  4942.9  196.65  4948.6  198.21  4955.7  194.53  4958.9  193.62
  4964.9  191.91  4970.5  192.32  4978.4  190.59  4988.4  190.98  4990.4  190.27
  4990.8  189.77  4994.8  189.77  4995.1  190.27  5000.2  192.64  5010.9   196.2
  5017.4  199.64  5022.8     200  5032.4  202.24  5047.4  204.44  5064.5  205.33
  5107.5  204.74  5118.1  205.37  5150.2  204.49  5235.9  203.97  5325.6  204.48
#Mann= 5 ,-1 , 0
  4830.9     .12       0  4889.4     .07       0  4958.9     .12       0
  4990.4     .05       0  4995.1     .12       0
Bank Sta=4990.4,4995.1
XS Rating Curve= 0 ,0
Exp/Cntr=0.3,0.1

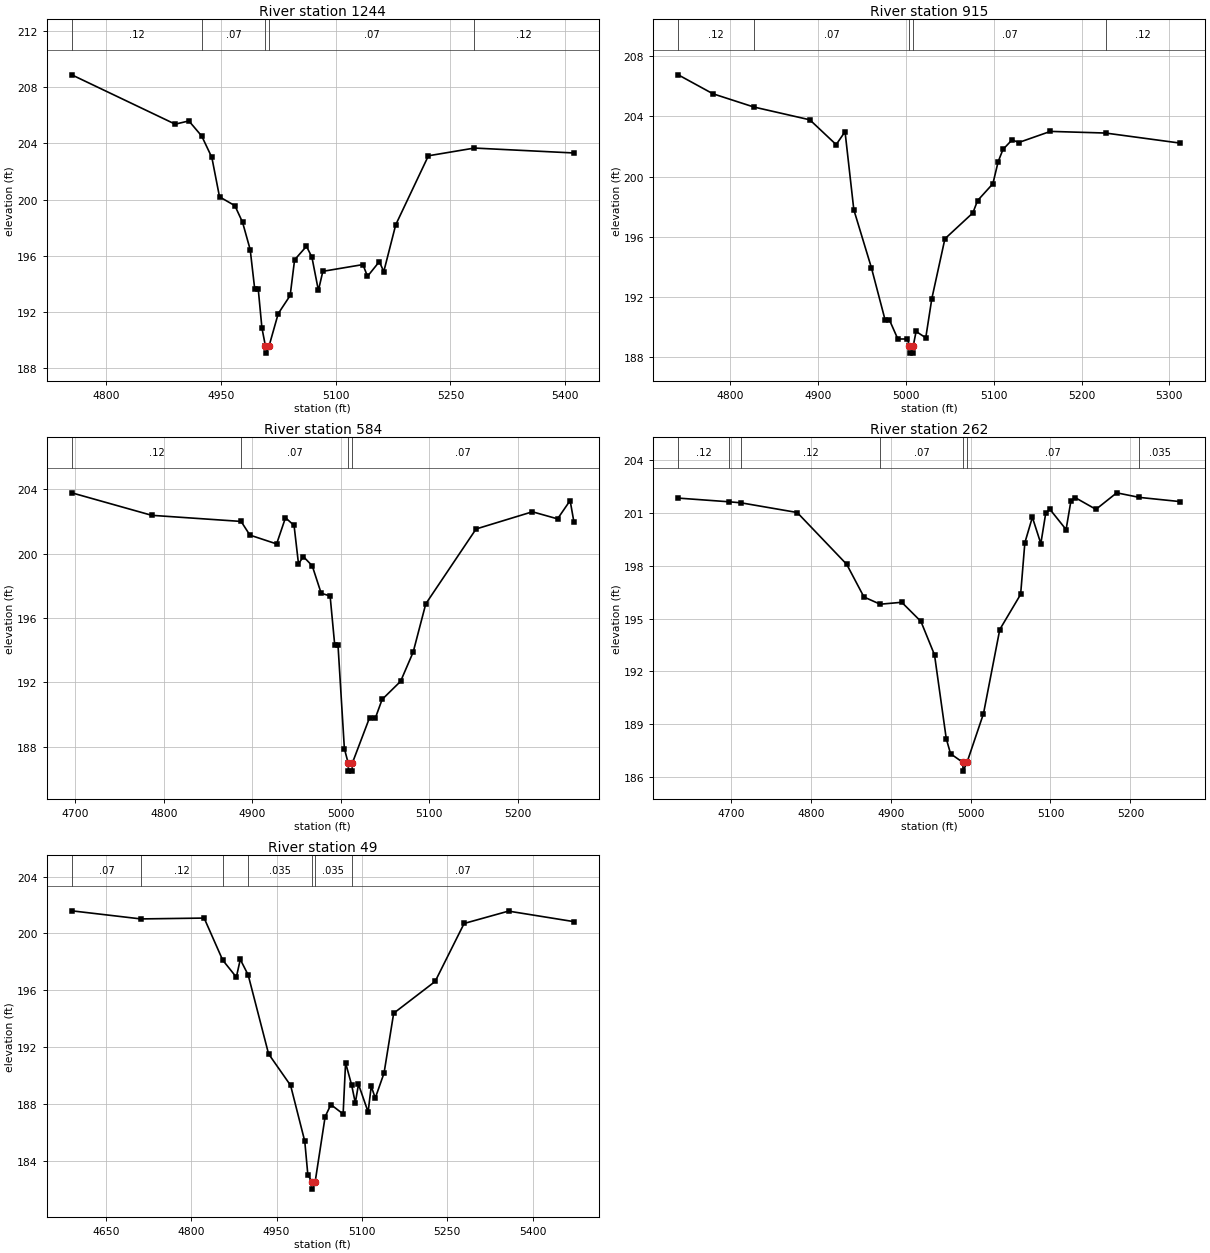
Type RM Length L Ch R = 1 ,1244    ,329,329,329
BEGIN DESCRIPTION:
Mapping XS 2b55a1ef
END DESCRIPTION:
XS GIS Cut Line= 3
      2488782.28     13471487.65      2489021.84     13471473.76
       2489378.2     13471259.25
#Sta/Elev= 30
  4755.3  208.87  4890.4  205.36  4908.3  205.59  4925.1  204.51  4938.3  202.99
  4948.3  200.19  4968.4  199.56  4978.4  198.38  4988.4  196.43  4994.3  193.63
  4998.9  193.63  5003.7  190.87  5008.3  189.57  5008.6  189.07    5013  189.57
    5025  191.88  5040.6  193.17  5046.4  195.71  5061.9  196.67    5069   195.9
  5077.5  193.53  5083.3  194.89  5135.7  195.37  5141.6  194.53  5157.1  195.58
  5162.9  194.87  5178.5   198.2  5221.2  203.11  5281.3  203.66  5411.2  203.31
#Mann= 5 ,-1 , 0
  4755.3     .12       0  4925.1     .07       0  5008.3     .05       0
    5013     .07       0  5281.3     .12       0
Bank Sta=5008.3,5013
XS Rating Curve= 0 ,0
Exp/Cntr=0.3,0.1

Type RM Length L Ch R = 1 ,915     ,331,331,331
BEGIN DESCRIPTION:
Mapping XS 6516ee98
END DESCRIPTION:
XS GIS Cut Line= 3
      2488865.56     13471654.31      2489126.01     13471671.68
      2489410.38     13471546.83
#Sta/Elev= 30
  4740.8  206.77  4780.3  205.51  4826.9  204.63  4890.6  203.78  4920.6  202.13
  4930.7  202.99  4940.7   197.8  4960.7  193.95  4976.2   190.5  4981.2  190.48
  4990.8  189.21  5001.8  189.21  5003.7  188.77  5004.1  188.27  5008.1  188.27
  5008.4  188.77  5011.6  189.71  5022.6  189.29  5029.5  191.89  5044.4  195.87
  5076.2  197.59  5081.6  198.41    5099  199.53    5105  200.99  5110.5  201.81
  5120.9  202.45  5128.4  202.27  5164.5  203.01  5227.3   202.9  5312.4  202.23
#Mann= 5 ,-1 , 0
  4740.8     .12       0  4826.9     .07       0  5003.7     .05       0
  5008.4     .07       0  5227.3     .12       0
Bank Sta=5003.7,5008.4
XS Rating Curve= 0 ,0
Exp/Cntr=0.3,0.1

Type RM Length L Ch R = 1 ,584     ,322,322,322
BEGIN DESCRIPTION:
Mapping XS a4d84369
END DESCRIPTION:
XS GIS Cut Line= 3
      2489025.32     13471959.87      2489320.45     13471925.15
      2489500.51     13471724.31
#Sta/Elev= 30
  4696.2  203.79  4786.5  202.39  4887.4  202.01  4897.3  201.16  4927.5  200.61
  4937.5  202.24  4947.2  201.76  4952.2  199.37  4957.7  199.82  4967.7  199.25
  4977.8  197.54  4987.9  197.37  4993.1  194.32  4996.8  194.32    5004  187.87
  5008.3  186.97  5008.6  186.47  5012.7  186.47    5013  186.97  5032.4  189.79
  5039.1  189.79  5046.6  190.93  5067.5  192.06  5081.7  193.88  5095.9  196.88
  5152.7  201.54  5216.3  202.61  5244.7  202.17  5258.9  203.31  5263.1     202
#Mann= 4 ,-1 , 0
  4696.2     .12       0  4887.4     .07       0  5008.3     .05       0
    5013     .07       0
Bank Sta=5008.3,5013
XS Rating Curve= 0 ,0
Exp/Cntr=0.3,0.1

Type RM Length L Ch R = 1 ,262     ,213,213,213
BEGIN DESCRIPTION:
Mapping XS 315aaf89
END DESCRIPTION:
XS GIS Cut Line= 4
      2489219.86     13472004.51       2489516.7     13472126.03
      2489575.73     13472099.99      2489653.69     13471869.58
#Sta/Elev= 30
    4634  201.86  4697.5  201.65  4712.8  201.59  4782.9  201.04  4844.9  198.09
  4866.5  196.23  4886.8  195.82  4913.8  195.93  4937.8  194.84  4954.8  192.94
  4969.5  188.17  4974.9  187.31  4990.2  186.82  4990.6  186.32  4995.5  186.82
  5016.1  189.59  5036.5  194.38  5062.6  196.38  5067.9  199.32  5077.3  200.77
  5087.9  199.27  5094.1  201.02  5099.3  201.22  5119.5  200.07  5125.5  201.68
  5130.8  201.89  5156.9  201.22  5182.9  202.16  5211.2   201.9  5262.5  201.66
#Mann= 7 ,-1 , 0
    4634     .12       0  4697.5     .07       0  4712.8     .12       0
  4886.8     .07       0  4990.2     .05       0  4995.5     .07       0
  5211.2    .035       0
Bank Sta=4990.2,4995.5
XS Rating Curve= 0 ,0
Exp/Cntr=0.3,0.1

Type RM Length L Ch R = 1 ,49      ,0,0,0
BEGIN DESCRIPTION:
TRIB 5A TO PERDIDO CREEK 1.0
END DESCRIPTION:
XS GIS Cut Line= 4
      2489202.47      13472028.8      2489471.57     13472284.01
      2489580.94     13472301.37        2489758.     13471942.04
#Sta/Elev= 30
  4590.1  201.59  4711.5  201.02  4822.7  201.08  4855.3  198.12  4879.3  196.92
  4886.2  198.17  4900.1  197.07  4935.9  191.52  4974.6   189.3  4999.5  185.37
  5004.9  183.01  5012.4   182.5  5012.8     182  5017.7   182.5  5035.3   187.1
  5045.4  187.95  5066.9  187.29  5071.2  190.89  5081.8  189.34  5088.3  188.07
  5093.9  189.38  5110.8  187.43  5116.3  189.24  5123.4  188.41  5138.8  190.17
  5155.7  194.38  5228.6  196.62  5279.5   200.7  5357.5  201.57  5472.3  200.83
#Mann= 7 ,-1 , 0
  4590.1     .07       0  4711.5     .12       0  4855.3     .07       0
  4900.1    .035       0  5012.4    .035       0  5017.7    .035       0
  5081.8     .07       0
Bank Sta=5012.4,5017.7
XS Rating Curve= 0 ,0
Exp/Cntr=0.3,0.1

Chan Stop Cuts=-1
Use User Specified Reach Order=0
Composite Channel Slope=5