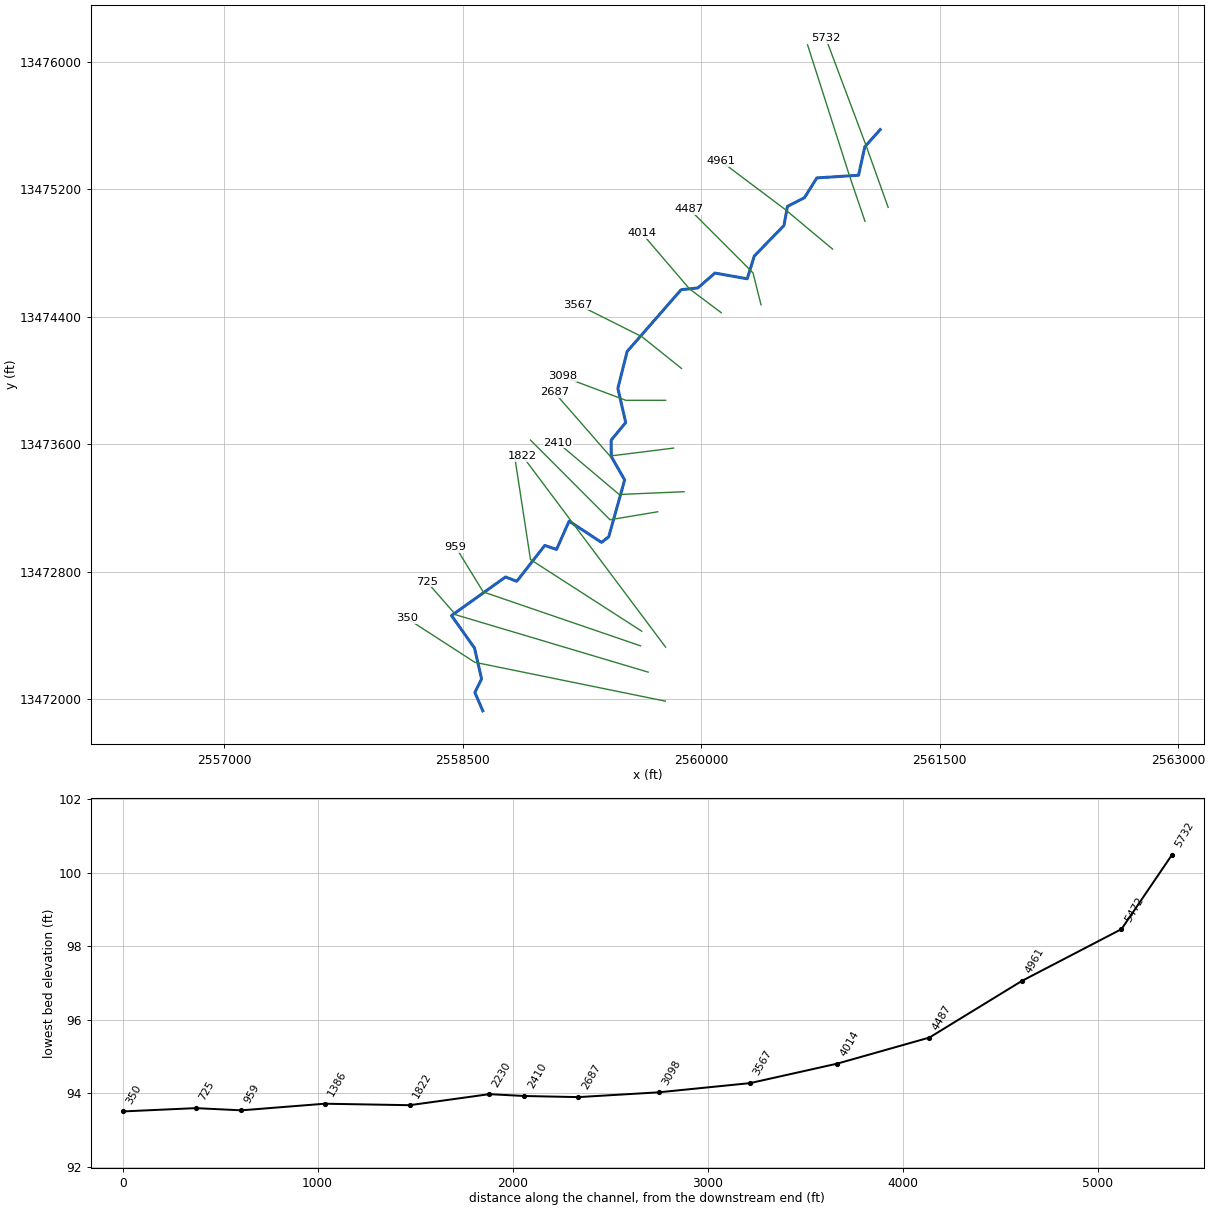
--- TRIB 6 TO COLETO CREEK RESERVOIR.prj (project) ---

Proj Title=TRIB 6 TO COLETO CREEK RESERVOIR Base Level Engineering
Current Plan=p01
Default Exp/Contr=0.3,0.1
English Units
Geom File=g01
Flow File=f01
Plan File=p01
Y Axis Title=Elevation
X Axis Title(PF)=Main Channel Distance
X Axis Title(XS)=Station
BEGIN DESCRIPTION:
TRIB 6 TO COLETO CREEK RESERVOIR
END DESCRIPTION:
DSS Export Rating Curves= 0
DSS Export Rating Curve Sorted= 0
DSS Export Volume Flow Curves= 0
DXF OffsetX= 0
DXF OffsetY= 0
DXF ScaleX= 1
DXF ScaleY= 10

--- TRIB 6 TO COLETO CREEK RESERVOIR.p01 (plan) ---

Plan Title=Multiple Run
Short Identifier=Multiple
Geom File=g01
Flow File=f01
Subcritical Flow
K Sum by GR= 0
Std Step Tol= 0.01
Critical Tol= 0.01
Num of Std Step Trials= 20
Max Error Tol= 0.3
Flow Tol Ratio= 0.001
Split Flow NTrial= 30
Split Flow Tol= 0.02
Split Flow Ratio= 0.02
Log Output Level= 0
Friction Slope Method= 1
Unsteady Friction Slope Method= 2
Unsteady Bridges Friction Slope Method= 1
Parabolic Critical Depth
Global Vel Dist=  1 , 1 , 1
Global Log Level= 0
CheckData=True
Encroach Param= -1, 0, 0, 0
BEGIN DESCRIPTION:
Multiple Run
END DESCRIPTION:

--- TRIB 6 TO COLETO CREEK RESERVOIR.f01 (steady flow) ---

Flow Title=Multiple
Number of Profiles=7
Profile Names=10-year,25-year,50-year,1pct_min,100-year,1pct_plu,500-year
River Rch & RM= TRIB 6 TO COLETO,Reach-1,5732
     777    1227    1623    1037    2070    4130    3327
River Rch & RM= TRIB 6 TO COLETO,Reach-1,4487
     843    1332    1763    1127    2248    4485    3613
Boundary for River Rch & Prof#=TRIB 6 TO COLETO,Reach-1,1
Up Type=0
Dn Type=3
Dn Slope=0.005
Boundary for River Rch & Prof#=TRIB 6 TO COLETO,Reach-1,2
Up Type=0
Dn Type=3
Dn Slope=0.005
Boundary for River Rch & Prof#=TRIB 6 TO COLETO,Reach-1,3
Up Type=0
Dn Type=3
Dn Slope=0.005
Boundary for River Rch & Prof#=TRIB 6 TO COLETO,Reach-1,4
Up Type=0
Dn Type=3
Dn Slope=0.005
Boundary for River Rch & Prof#=TRIB 6 TO COLETO,Reach-1,5
Up Type=0
Dn Type=3
Dn Slope=0.005
Boundary for River Rch & Prof#=TRIB 6 TO COLETO,Reach-1,6
Up Type=0
Dn Type=3
Dn Slope=0.005
Boundary for River Rch & Prof#=TRIB 6 TO COLETO,Reach-1,7
Up Type=0
Dn Type=3
Dn Slope=0.005

--- TRIB 6 TO COLETO CREEK RESERVOIR.g01 (geometry) ---

Geom Title=Existing Conditions
Program Version=4.10

River Reach=TRIB 6 TO COLETO,Reach-1
Reach XY= 30
        2561125.       13475575.      2561028.08     13475466.72
      2560988.74      13475288.2      2560726.25     13475271.55
      2560648.83     13475147.87      2560541.31     13475092.13
      2560519.47     13474972.58      2560332.86     13474781.17
      2560288.63     13474637.95      2560085.48     13474674.06
      2559977.42     13474580.54      2559872.57     13474569.48
      2559532.82     13474181.19       2559474.6       13473950.
      2559523.95     13473735.44      2559432.55       13473625.
      2559433.23     13473521.77      2559517.47     13473375.01
      2559417.15     13473018.18      2559371.97     13472982.75
        2559168.     13473116.17      2559088.75     13472938.48
      2559015.01     13472963.75      2558838.68      13472738.5
      2558768.35     13472765.68      2558428.09     13472523.36
      2558572.93     13472319.14      2558617.41     13472124.99
      2558575.04     13472040.41        2558625.       13471925.

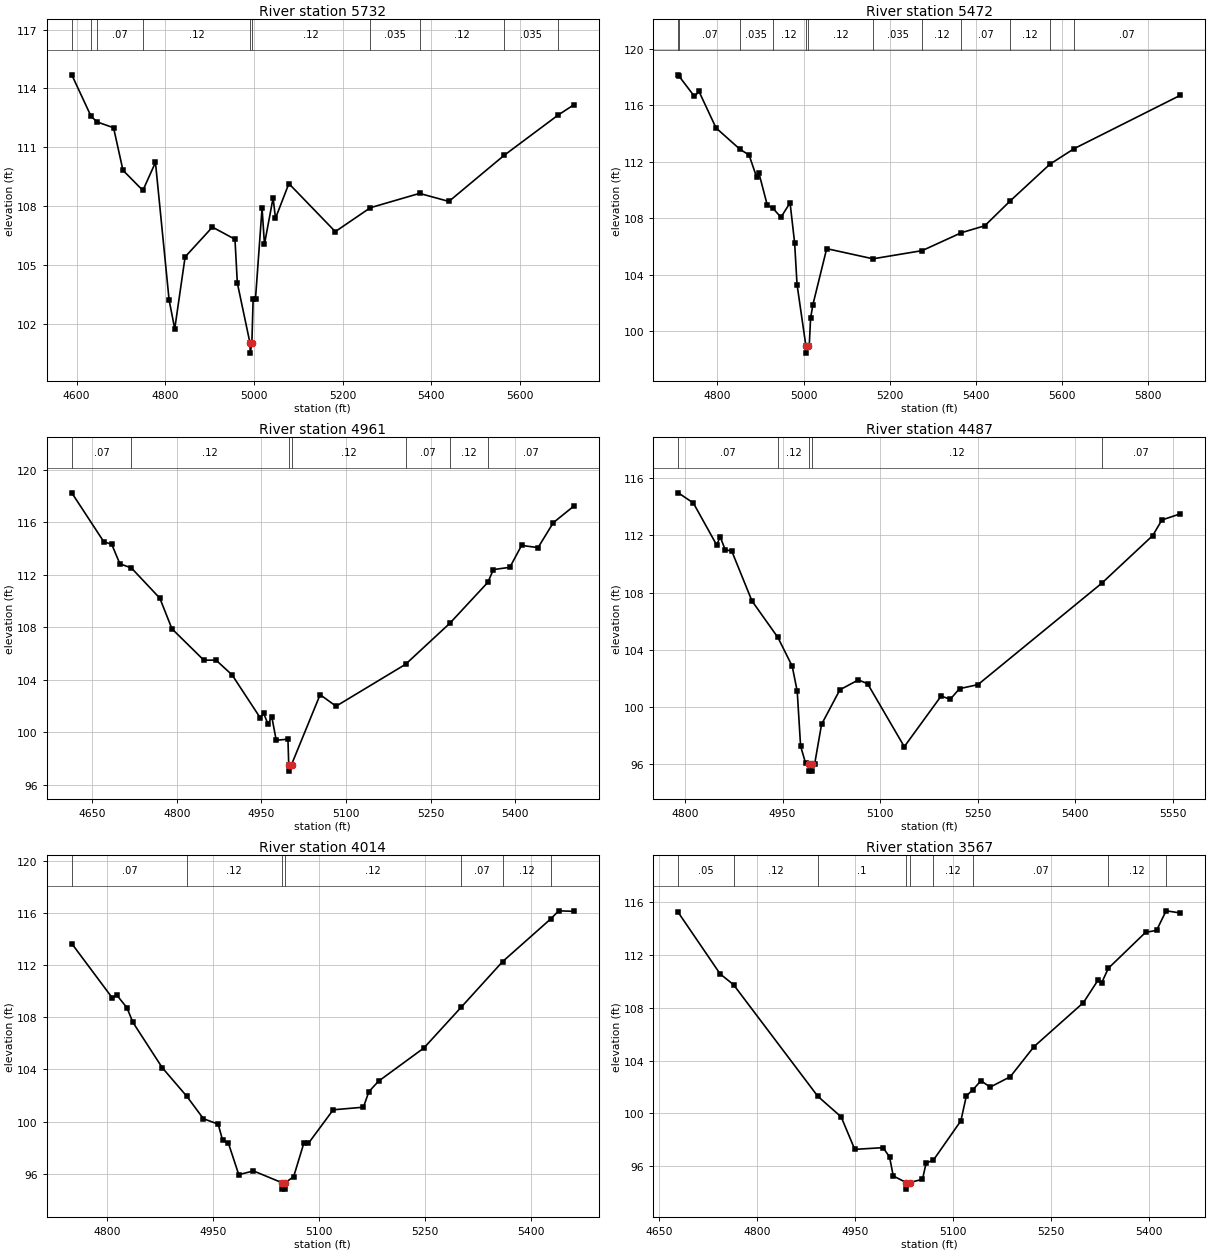
Type RM Length L Ch R = 1 ,5732    ,260,260,260
BEGIN DESCRIPTION:
TRIB 6 TO COLETO CREEK RESERVOIR 11.0
END DESCRIPTION:
XS GIS Cut Line= 3
      2561174.98     13475086.23      2561036.68     13475473.05
       2560782.6     13476148.76
#Sta/Elev= 30
  4589.2  114.69  4632.6  112.58  4645.9  112.29  4683.5  111.99  4704.7  109.82
  4749.6  108.79    4778  110.22  4808.8   103.2  4821.5  101.73  4844.9   105.4
  4906.5  106.92  4957.4   106.3  4962.7  104.07  4991.4  100.99  4991.7  100.49
  4995.5  100.99  4998.4  103.27  5003.7  103.27  5018.5  107.89  5023.9  106.05
  5043.4  108.41  5048.8  107.37    5079  109.14  5183.7  106.69  5262.9  107.91
  5373.8  108.64    5440  108.23  5564.5  110.58  5686.6  112.64  5721.9  113.16
#Mann= 10 ,-1 , 0
  4589.2     .07       0  4632.6    .035       0  4645.9     .07       0
  4749.6     .12       0  4991.4     .05       0  4995.5     .12       0
  5262.9    .035       0  5373.8     .12       0  5564.5    .035       0
  5686.6     .07       0
Bank Sta=4991.4,4995.5
XS Rating Curve= 0 ,0
Exp/Cntr=0.3,0.1

Type RM Length L Ch R = 1 ,5472    ,511,511,511
BEGIN DESCRIPTION:
Mapping XS 404263b7
END DESCRIPTION:
XS GIS Cut Line= 3
      2561029.16     13474999.38      2560931.93     13475284.13
      2560668.04     13476107.06
#Sta/Elev= 30
  4709.3  118.17  4710.6   118.1  4746.9  116.64  4757.5  116.99    4797  114.41
  4852.4   112.9  4873.7  112.49    4891  110.94  4896.3  111.24    4916  108.93
  4928.1  108.75  4947.7  108.08  4968.8  109.11  4979.4  106.26    4985  103.32
  5005.6   98.96  5005.9   98.46  5010.5   98.96  5013.3   98.96  5016.4  100.93
  5021.7  101.88  5053.8  105.86  5161.2  105.14  5275.4  105.72  5366.5  106.99
  5420.7  107.48    5480  109.25  5571.8  111.84  5627.9  112.94  5874.4  116.72
#Mann= 12 ,-1 , 0
  4709.3    .035       0  4710.6     .07       0  4852.4    .035       0
  4928.1     .12       0  5005.6     .05       0  5010.5     .12       0
  5161.2    .035       0  5275.4     .12       0  5366.5     .07       0
    5480     .12       0  5571.8    .035       0  5627.9     .07       0
Bank Sta=5005.6,5010.5
XS Rating Curve= 0 ,0
Exp/Cntr=0.3,0.1

Type RM Length L Ch R = 1 ,4961    ,474,474,474
BEGIN DESCRIPTION:
TRIB 6 TO COLETO CREEK RESERVOIR 10.0
END DESCRIPTION:
XS GIS Cut Line= 3
      2560825.02     13474824.98        2560525.       13475075.
      2560125.03     13475374.98
#Sta/Elev= 30
  4613.5  118.23  4670.1  114.52  4684.5   114.3  4698.8  112.83  4719.3  112.51
  4769.7  110.21  4791.2  107.88  4847.8  105.49  4869.3   105.5  4897.9  104.37
  4947.4  101.13  4953.9  101.44  4961.7  100.62  4968.2   101.2  4976.1    99.4
  4996.9   99.48  4998.3   97.55  4998.6   97.05  5003.3   97.55    5054  102.87
  5082.2  101.99  5205.5  105.18    5284   108.3  5351.5  111.42  5361.3  112.39
  5390.5  112.56  5411.3  114.23  5440.5  114.06  5467.6  115.96    5504  117.22
#Mann= 7 ,-1 , 0
  4613.5     .07       0  4719.3     .12       0  4998.3     .05       0
  5003.3     .12       0  5205.5     .07       0    5284     .12       0
  5351.5     .07       0
Bank Sta=4998.3,5003.3
XS Rating Curve= 0 ,0
Exp/Cntr=0.3,0.1

Type RM Length L Ch R = 1 ,4487    ,473,473,473
BEGIN DESCRIPTION:
TRIB 6 TO COLETO CREEK RESERVOIR 9.0
END DESCRIPTION:
XS GIS Cut Line= 3
      2560374.99     13474475.04        2560325.       13474675.
        2559925.       13475075.
#Sta/Elev= 30
  4789.7  114.98  4812.9  114.27  4848.9  111.32  4854.1  111.91  4861.8  111.01
  4872.1  110.89    4903  107.42  4942.9  104.86  4964.9  102.85  4972.6   101.1
  4977.8   97.26  4985.5   96.06  4990.7   96.01    4991   95.51  4995.4   95.51
  4995.8   96.01  4999.4   96.01    5010   98.78  5038.2   101.2  5066.5  101.89
  5080.7  101.63  5137.2   97.22  5193.8  100.76  5207.9  100.54  5222.1  101.28
  5250.4  101.56  5440.6  108.65  5519.1  111.99  5533.2  113.08  5561.5  113.51
#Mann= 5 ,-1 , 0
  4789.7     .07       0  4942.9     .12       0  4990.7     .05       0
  4995.8     .12       0  5440.6     .07       0
Bank Sta=4990.7,4995.8
XS Rating Curve= 0 ,0
Exp/Cntr=0.3,0.1

Type RM Length L Ch R = 1 ,4014    ,447,447,447
BEGIN DESCRIPTION:
TRIB 6 TO COLETO CREEK RESERVOIR 8.0
END DESCRIPTION:
XS GIS Cut Line= 3
      2560125.02     13474424.99        2559925.       13474575.
        2559625.       13474925.
#Sta/Elev= 30
    4750  113.68  4807.3  109.51  4813.6  109.73  4828.1  108.75  4836.5  107.63
  4878.1  104.14    4913  101.93  4936.5  100.21  4957.3    99.8  4963.6   98.56
  4971.9   98.32  4986.5   95.91  5007.2    96.2  5047.4    95.3  5047.8    94.8
  5052.2    94.8  5052.6    95.3  5064.2   95.76  5078.5   98.31  5085.1   98.32
  5120.2   100.9    5163   101.1  5170.7  102.29  5184.4   103.1  5248.6  105.65
  5301.5  108.79  5360.2   112.3  5428.3  115.58  5439.6   116.2    5461  116.16
#Mann= 7 ,-1 , 0
    4750     .07       0    4913     .12       0  5047.4     .05       0
  5052.6     .12       0  5301.5     .07       0  5360.2     .12       0
  5428.3    .035       0
Bank Sta=5047.4,5052.6
XS Rating Curve= 0 ,0
Exp/Cntr=0.3,0.1

Type RM Length L Ch R = 1 ,3567    ,469,469,469
BEGIN DESCRIPTION:
TRIB 6 TO COLETO CREEK RESERVOIR 7.0
END DESCRIPTION:
XS GIS Cut Line= 3
      2559875.03     13474074.98        2559625.       13474275.
        2559225.       13474475.
#Sta/Elev= 30
  4679.8  115.22  4743.9  110.56  4764.3  109.75  4893.1   101.3  4928.8   99.74
  4949.6   97.28  4992.8   97.41  5002.8   96.71  5008.4   95.27  5028.1   94.77
  5028.5   94.27  5033.3   94.77  5053.1   95.01  5058.7   96.25  5069.7   96.46
  5111.8   99.44  5120.2  101.33  5130.3   101.8  5142.5  102.48  5156.5  101.99
  5187.3  102.78  5223.6  105.06  5299.1  108.39  5321.4  110.09    5327  109.89
  5337.2  110.99  5394.1  113.71  5410.9  113.86  5425.5  115.34  5447.2  115.18
#Mann= 9 ,-1 , 0
  4679.8     .05       0  4764.3     .12       0  4893.1      .1       0
  5028.1     .05       0  5033.3      .1       0  5069.7     .12       0
  5130.3     .07       0  5337.2     .12       0  5425.5    .035       0
Bank Sta=5028.1,5033.3
XS Rating Curve= 0 ,0
Exp/Cntr=0.3,0.1

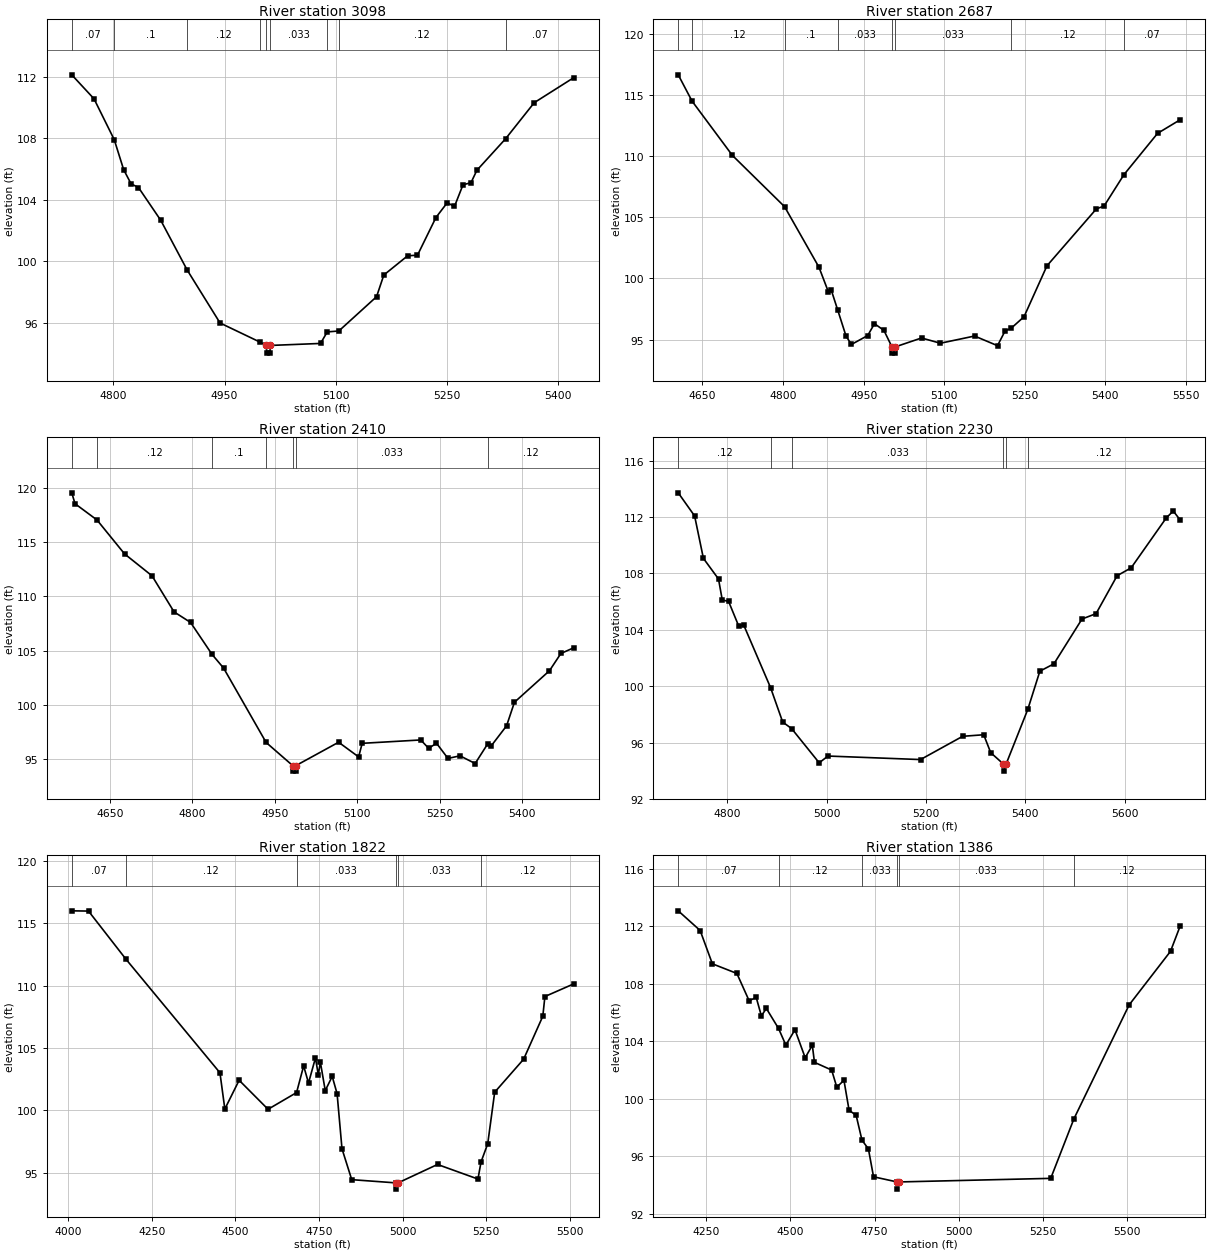
Type RM Length L Ch R = 1 ,3098    ,411,411,411
BEGIN DESCRIPTION:
TRIB 6 TO COLETO CREEK RESERVOIR 6.0
END DESCRIPTION:
XS GIS Cut Line= 3
      2559775.05       13473875.        2559525.       13473875.
      2559125.05     13474024.98
#Sta/Elev= 30
  4743.9  112.12  4773.9  110.56  4801.2   107.9  4813.9  105.95  4823.9  105.03
  4833.9  104.79  4863.9  102.66  4899.5   99.43  4943.9   95.98  4998.1   94.73
  5006.4   94.52  5006.8   94.02  5011.3   94.02  5011.7   94.52  5079.4   94.65
  5088.5    95.4  5104.1   95.46    5155   97.69  5164.8    99.1  5196.9  100.35
  5210.2  100.39  5235.1  102.84  5250.3   103.8  5260.1  103.56  5271.6  104.97
  5282.3   105.1  5290.3  105.91    5329  107.96  5367.7  110.31  5421.1  111.94
#Mann= 9 ,-1 , 0
  4743.9     .07       0  4801.2      .1       0  4899.5     .12       0
  4998.1    .033       0  5006.4    .033       0  5011.7    .033       0
  5088.5     .12       0  5104.1     .12       0    5329     .07       0
Bank Sta=5006.4,5011.7
XS Rating Curve= 0 ,0
Exp/Cntr=0.3,0.1

Type RM Length L Ch R = 1 ,2687    ,277,277,277
BEGIN DESCRIPTION:
TRIB 6 TO COLETO CREEK RESERVOIR 5.0
END DESCRIPTION:
XS GIS Cut Line= 3
      2559824.95     13473574.99        2559425.       13473525.
      2559074.98     13473925.02
#Sta/Elev= 30
  4604.9  116.67  4630.6  114.52  4705.6  110.08  4802.8  105.88  4866.9  100.92
  4884.5   98.89  4889.6   99.07  4901.6   97.44  4917.3   95.28  4927.3    94.6
  4957.6   95.33  4970.2    96.3  4987.8   95.75  5002.8   94.39  5003.2   93.89
  5007.7   93.89  5008.1   94.39  5057.8   95.13  5092.9    94.7  5156.5   95.29
  5199.2    94.5  5213.5   95.72  5224.2   95.91  5248.6   96.87  5291.3  101.04
  5383.3   105.7  5397.6  105.93  5434.6   108.5  5497.2  111.88  5539.5     113
#Mann= 8 ,-1 , 0
  4604.9     .07       0  4630.6     .12       0  4802.8      .1       0
  4901.6    .033       0  5002.8    .033       0  5008.1    .033       0
  5224.2     .12       0  5434.6     .07       0
Bank Sta=5002.8,5008.1
XS Rating Curve= 0 ,0
Exp/Cntr=0.3,0.1

Type RM Length L Ch R = 1 ,2410    ,180,180,180
BEGIN DESCRIPTION:
Mapping XS b76250a8
END DESCRIPTION:
XS GIS Cut Line= 3
      2559890.91     13473300.97      2559482.89     13473283.61
      2559096.64      13473609.1
#Sta/Elev= 30
  4580.9  119.54  4586.8  118.54  4626.8  117.04  4676.9  113.92  4726.9   111.9
    4767  108.58    4797  107.61  4836.2  104.66  4857.1  103.41  4934.5   96.56
  4983.1   94.42  4983.5   93.92    4988   93.92  4988.4   94.42  5066.4   96.58
  5102.8   95.23  5109.3   96.48  5215.9   96.79  5230.2   96.02  5244.5   96.49
  5265.4   95.09  5287.3   95.33  5314.8   94.62  5337.9   96.45  5343.4    96.2
    5372   98.09  5386.3  100.26    5450  103.16  5470.8  104.75  5494.4  105.28
#Mann= 7 ,-1 , 0
  4580.9     .07       0  4626.8     .12       0  4836.2      .1       0
  4934.5    .033       0  4983.1    .033       0  4988.4    .033       0
  5337.9     .12       0
Bank Sta=4983.1,4988.4
XS Rating Curve= 0 ,0
Exp/Cntr=0.3,0.1

Type RM Length L Ch R = 1 ,2230    ,408,408,408
BEGIN DESCRIPTION:
TRIB 6 TO COLETO CREEK RESERVOIR 4.0
END DESCRIPTION:
XS GIS Cut Line= 3
      2559725.02       13473175.        2559425.       13473125.
      2558924.97     13473625.03
#Sta/Elev= 30
    4701  113.71    4734  112.07  4751.7  109.06  4782.1   107.6  4789.7  106.11
  4802.4  106.01  4822.7  104.27  4832.8  104.34    4887   99.89  4911.4   97.45
  4929.3   96.99  4984.9   94.56  5002.6   95.04    5189   94.79  5273.9   96.44
  5316.3   96.55  5330.4   95.28  5356.1   94.47  5356.5   93.97  5361.4   94.47
  5405.1   98.35  5429.4  101.06  5457.7  101.58  5514.3  104.76  5542.6  105.14
    5585  107.83  5613.3  108.39    5684  111.93  5698.1  112.42  5712.3  111.77
#Mann= 6 ,-1 , 0
    4701     .12       0    4887      .1       0  4929.3    .033       0
  5356.1    .033       0  5361.4    .033       0  5405.1     .12       0
Bank Sta=5356.1,5361.4
XS Rating Curve= 0 ,0
Exp/Cntr=0.3,0.1

Type RM Length L Ch R = 1 ,1822    ,436,436,436
BEGIN DESCRIPTION:
TRIB 6 TO COLETO CREEK RESERVOIR 3.0
END DESCRIPTION:
XS GIS Cut Line= 3
      2559774.99     13472325.02        2559175.       13473125.
      2558874.99     13473525.02
#Sta/Elev= 30
  4011.4  116.01  4061.4  115.99  4173.2  112.13  4454.1  103.01  4468.7   100.1
  4511.4  102.41  4597.8  100.08    4683  101.42  4704.1  103.56  4718.7  102.19
  4739.5  104.21  4747.8  102.85  4754.1  103.86  4768.7  101.58  4789.5  102.72
  4804.1  101.33  4818.7   96.91  4847.8   94.43  4980.6   94.17    4981   93.67
    4986   94.17  5104.1   95.65  5224.9   94.48  5234.2   95.86  5254.1   97.31
  5274.9  101.45  5361.4   104.1  5418.7  107.55  5424.9  109.13  5511.4  110.15
#Mann= 6 ,-1 , 0
  4011.4     .07       0  4173.2     .12       0    4683    .033       0
  4980.6    .033       0    4986    .033       0  5234.2     .12       0
Bank Sta=4980.6,4986
XS Rating Curve= 0 ,0
Exp/Cntr=0.3,0.1

Type RM Length L Ch R = 1 ,1386    ,427,427,427
BEGIN DESCRIPTION:
TRIB 6 TO COLETO CREEK RESERVOIR 2.0
END DESCRIPTION:
XS GIS Cut Line= 3
      2559624.97     13472425.02        2558925.       13472875.
        2558825.     13473525.03
#Sta/Elev= 30
  4167.6  113.09  4232.6  111.72  4268.9   109.4  4341.6  108.73  4377.9  106.83
    4399  107.06  4414.2  105.78  4429.1  106.29  4465.2   104.9  4486.9  103.74
    4514  104.81  4544.3  102.86  4565.5  103.73  4571.8  102.54  4622.9     102
  4638.1  100.81  4659.3  101.29  4674.5   99.21  4695.6   98.84  4712.8   97.12
  4731.9   96.51  4747.1   94.57    4817   94.21  4817.5   93.71  4822.5   94.21
  5272.9   94.46  5341.6    98.6  5505.6  106.54  5628.3  110.27  5657.4  112.06
#Mann= 6 ,-1 , 0
  4167.6     .07       0  4465.2     .12       0  4712.8    .033       0
    4817    .033       0  4822.5    .033       0  5341.6     .12       0
Bank Sta=4817,4822.5
XS Rating Curve= 0 ,0
Exp/Cntr=0.3,0.1

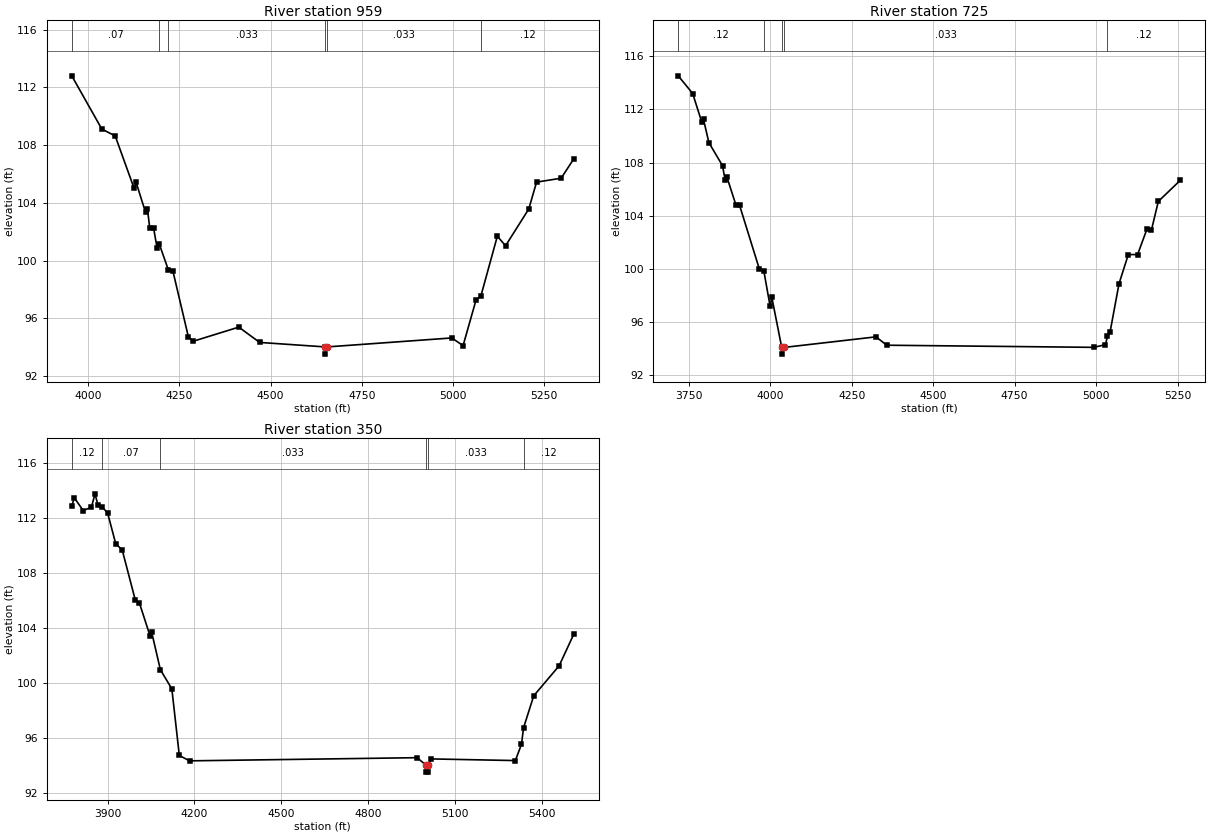
Type RM Length L Ch R = 1 ,959     ,234,234,234
BEGIN DESCRIPTION:
Mapping XS ce7f47d2
END DESCRIPTION:
XS GIS Cut Line= 3
      2559617.43     13472333.09      2558627.86     13472671.63
      2558454.26     13472953.71
#Sta/Elev= 30
  3954.8   112.8  4037.3  109.11  4073.9  108.64  4125.9     105  4131.2  105.43
  4157.2  103.34  4162.5  103.55  4168.7  102.25  4179.3  102.26  4188.5  100.91
  4194.3  101.19  4219.6   99.37  4232.2   99.28  4274.4   94.75  4287.7   94.42
  4412.9    95.4  4470.2   94.34    4650   94.03  4650.4   93.53  4655.5   94.03
    4997   94.65  5028.1   94.12  5063.4   97.26  5077.1   97.57  5122.1   101.7
  5144.5  101.03  5208.3  103.58  5229.6  105.44  5297.1  105.71  5331.9  107.06
#Mann= 6 ,-1 , 0
  3954.8     .07       0  4194.3     .12       0  4219.6    .033       0
    4650    .033       0  4655.5    .033       0  5077.1     .12       0
Bank Sta=4650,4655.5
XS Rating Curve= 0 ,0
Exp/Cntr=0.3,0.1

Type RM Length L Ch R = 1 ,725     ,375,375,375
BEGIN DESCRIPTION:
Mapping XS e7702523
END DESCRIPTION:
XS GIS Cut Line= 3
      2559665.19     13472168.15      2558454.24      13472528.4
      2558271.97     13472736.72
#Sta/Elev= 30
  3717.9  114.53  3762.2   113.2  3790.2  111.04  3795.4  111.25    3812   109.5
  3853.7  107.77  3861.8  106.69    3867  106.93    3895   104.8  3905.9   104.8
  3966.6     100  3980.3   99.88  3999.8   97.18    4005   97.86  4035.4   94.09
  4035.9   93.59  4040.9   94.09  4324.5   94.89  4357.7   94.26  4992.2    94.1
  5028.3    94.3  5034.7   94.92  5042.5   95.24  5070.1   98.89  5098.5  101.08
    5127  101.08  5155.5  102.98  5169.7  102.94  5190.6  105.08  5258.1  106.67
#Mann= 5 ,-1 , 0
  3717.9     .12       0  3980.3    .033       0  4035.4    .033       0
  4040.9    .033       0  5034.7     .12       0
Bank Sta=4035.4,4040.9
XS Rating Curve= 0 ,0
Exp/Cntr=0.3,0.1

Type RM Length L Ch R = 1 ,350     ,0,0,0
BEGIN DESCRIPTION:
TRIB 6 TO COLETO CREEK RESERVOIR 1.0
END DESCRIPTION:
XS GIS Cut Line= 3
      2559773.67     13471985.87      2558574.75     13472229.88
      2558146.07     13472506.71
#Sta/Elev= 30
  3776.5  112.86  3785.4  113.44    3816  112.51  3844.4  112.76  3856.8  113.73
    3867   112.9  3880.7  112.78  3900.1  112.35  3928.2  110.11  3950.7  109.65
  3996.2  105.98  4009.9  105.81  4046.8   103.4  4051.9  103.72  4082.4  100.95
  4122.1   99.55  4147.9   94.71  4183.3   94.32  4969.1   94.55  5000.2      94
  5000.6    93.5  5005.2    93.5  5005.7      94  5018.1   94.46  5308.4   94.34
  5329.5   95.53  5336.6   96.72  5371.8   99.05  5459.5  101.23  5510.3  103.54
#Mann= 6 ,-1 , 0
  3776.5     .12       0  3880.7     .07       0  4082.4    .033       0
  5000.2    .033       0  5005.7    .033       0  5336.6     .12       0
Bank Sta=5000.2,5005.7
XS Rating Curve= 0 ,0
Exp/Cntr=0.3,0.1

Chan Stop Cuts=-1
Use User Specified Reach Order=0
Composite Channel Slope=5