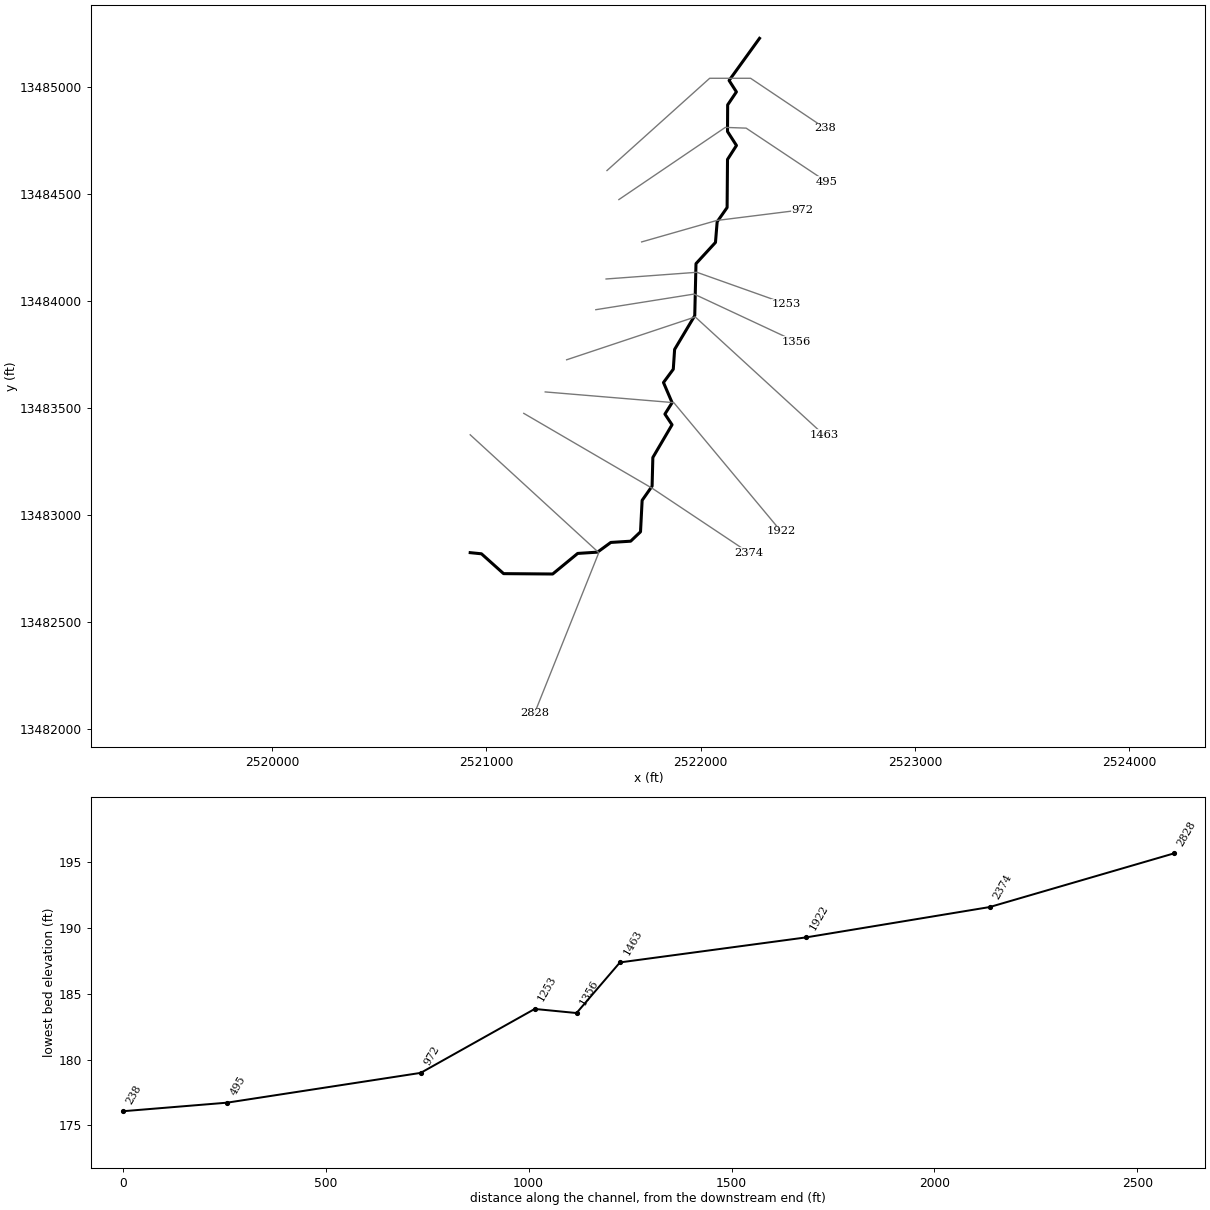
--- TRIB 6 TO HOG THIEF CREEK.prj (project) ---

Proj Title=TRIB 6 TO HOG THIEF CREEK Base Level Engineering
Current Plan=p01
Default Exp/Contr=0.3,0.1
English Units
Geom File=g01
Flow File=f01
Plan File=p01
Y Axis Title=Elevation
X Axis Title(PF)=Main Channel Distance
X Axis Title(XS)=Station
BEGIN DESCRIPTION:
TRIB 6 TO HOG THIEF CREEK
END DESCRIPTION:
DSS Export Rating Curves= 0
DSS Export Rating Curve Sorted= 0
DSS Export Volume Flow Curves= 0
DXF OffsetX= 0
DXF OffsetY= 0
DXF ScaleX= 1
DXF ScaleY= 10

--- TRIB 6 TO HOG THIEF CREEK.p01 (plan) ---

Plan Title=Multiple Run
Short Identifier=Multiple
Geom File=g01
Flow File=f01
Subcritical Flow
K Sum by GR= 0
Std Step Tol= 0.01
Critical Tol= 0.01
Num of Std Step Trials= 20
Max Error Tol= 0.3
Flow Tol Ratio= 0.001
Split Flow NTrial= 30
Split Flow Tol= 0.02
Split Flow Ratio= 0.02
Log Output Level= 0
Friction Slope Method= 1
Unsteady Friction Slope Method= 2
Unsteady Bridges Friction Slope Method= 1
Parabolic Critical Depth
Global Vel Dist=  1 , 1 , 1
Global Log Level= 0
CheckData=True
Encroach Param= -1, 0, 0, 0
BEGIN DESCRIPTION:
Multiple Run
END DESCRIPTION:

--- TRIB 6 TO HOG THIEF CREEK.f01 (steady flow) ---

Flow Title=Multiple
Number of Profiles=7
Profile Names=10-year,25-year,50-year,1pct_min,100-year,1pct_plu,500-year
River Rch & RM= TRIB 6 TO HOG TH,Reach-1,2828
     126     179     220     132     264     527     374
River Rch & RM= TRIB 6 TO HOG TH,Reach-1,1922
     263     395     507     316     630    1256     958
Boundary for River Rch & Prof#=TRIB 6 TO HOG TH,Reach-1,1
Up Type=0
Dn Type=3
Dn Slope=0.005
Boundary for River Rch & Prof#=TRIB 6 TO HOG TH,Reach-1,2
Up Type=0
Dn Type=3
Dn Slope=0.005
Boundary for River Rch & Prof#=TRIB 6 TO HOG TH,Reach-1,3
Up Type=0
Dn Type=3
Dn Slope=0.005
Boundary for River Rch & Prof#=TRIB 6 TO HOG TH,Reach-1,4
Up Type=0
Dn Type=3
Dn Slope=0.005
Boundary for River Rch & Prof#=TRIB 6 TO HOG TH,Reach-1,5
Up Type=0
Dn Type=3
Dn Slope=0.005
Boundary for River Rch & Prof#=TRIB 6 TO HOG TH,Reach-1,6
Up Type=0
Dn Type=3
Dn Slope=0.005
Boundary for River Rch & Prof#=TRIB 6 TO HOG TH,Reach-1,7
Up Type=0
Dn Type=3
Dn Slope=0.005

--- TRIB 6 TO HOG THIEF CREEK.g01 (geometry) ---

Geom Title=Existing Conditions
Program Version=4.10

River Reach=TRIB 6 TO HOG TH,Reach-1
Reach XY= 30
        2520925.       13482825.      2520977.51     13482819.67
      2521080.85     13482727.06      2521309.84     13482725.39
       2521426.5     13482821.38      2521519.02     13482827.36
      2521580.98     13482872.64      2521673.75     13482878.51
      2521719.65     13482922.27      2521727.27     13483069.06
      2521773.77     13483135.51      2521777.25     13483269.07
      2521866.77     13483421.77      2521833.55     13483471.67
      2521867.19     13483524.91      2521826.86     13483618.87
      2521872.62     13483680.97      2521878.83     13483773.42
      2521972.76     13483930.93      2521978.55     13484173.53
      2522069.46     13484272.58      2522077.36     13484369.02
      2522123.78      13484435.5      2522125.66     13484659.84
      2522167.44       13484725.      2522125.64     13484790.17
      2522126.36     13484914.56      2522167.19      13484975.1
      2522133.01     13485028.33        2522275.       13485225.

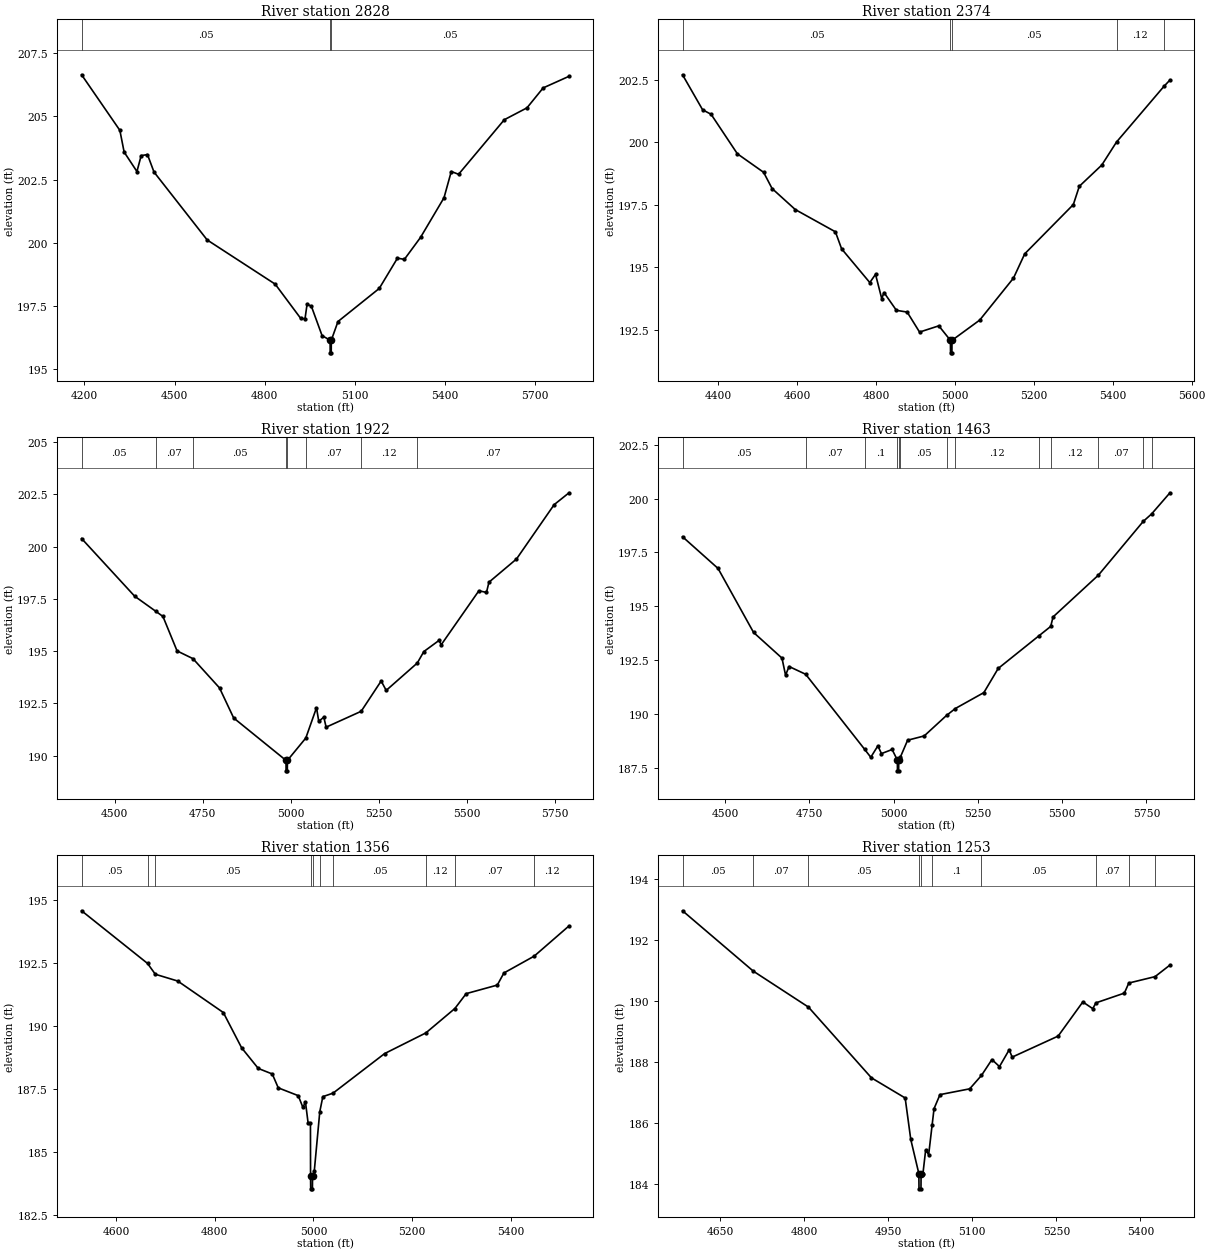
Type RM Length L Ch R = 1 ,2828    ,454,454,454
BEGIN DESCRIPTION:
TRIB 6 TO HOG THIEF CREEK 6.0
END DESCRIPTION:
XS GIS Cut Line= 3
        2520925.       13483375.        2521525.       13482825.
      2521225.01     13482075.02
#Sta/Elev= 30
  4190.8  206.65  4318.1  204.45  4332.3  203.59  4374.9  202.82    4389  203.45
    4410  203.49  4431.6   202.8  4608.6  200.11  4834.9  198.36    4920     197
  4934.1  196.99  4940.9  197.56  4955.1  197.49  4990.9  196.32  5017.6  196.14
  5017.8  195.64  5021.3  195.64  5021.6  196.14  5043.8  196.88  5181.1  198.19
  5241.7  199.39  5264.6  199.34  5318.4  200.21  5396.5  201.78  5420.7  202.82
    5445  202.71  5597.1  204.87  5672.5  205.34  5726.4  206.13  5812.5  206.59
#Mann= 3 ,-1 , 0
  4190.8     .05       0  5017.6     .05       0  5021.6     .05       0
Bank Sta=5017.6,5021.6
XS Rating Curve= 0 ,0
Exp/Cntr=0.3,0.1

Type RM Length L Ch R = 1 ,2374    ,452,452,452
BEGIN DESCRIPTION:
TRIB 6 TO HOG THIEF CREEK 5.0
END DESCRIPTION:
XS GIS Cut Line= 3
      2521174.96     13483475.03        2521775.       13483125.
        2522225.       13482825.
#Sta/Elev= 30
  4309.5  202.69  4360.4  201.29  4381.9  201.11  4448.5  199.53    4515  198.79
  4536.5  198.14  4595.3   197.3    4697  196.41  4712.7  195.73  4784.2  194.38
  4798.7  194.71  4814.4  193.74  4820.2  193.98  4851.6  193.27  4878.9   193.2
  4910.3   192.4  4959.1  192.65  4988.5  192.07  4988.8  191.57  4992.3  191.57
  4992.5  192.07  5062.8  192.88  5148.4  194.56  5176.9  195.53  5300.1   197.5
  5315.2  198.23  5372.2  199.08  5409.5     200  5529.9  202.23    5545  202.48
#Mann= 5 ,-1 , 0
  4309.5     .05       0  4988.5     .05       0  4992.5     .05       0
  5409.5     .12       0  5529.9     .07       0
Bank Sta=4988.5,4992.5
XS Rating Curve= 0 ,0
Exp/Cntr=0.3,0.1

Type RM Length L Ch R = 1 ,1922    ,459,459,459
BEGIN DESCRIPTION:
TRIB 6 TO HOG THIEF CREEK 4.0
END DESCRIPTION:
XS GIS Cut Line= 3
      2521275.03       13483575.        2521875.       13483525.
      2522375.01     13482924.98
#Sta/Elev= 30
  4405.9  200.39  4556.4  197.63  4616.1  196.91  4636.7  196.66  4676.8  195.01
  4721.9  194.64  4797.2  193.24  4837.4   191.8  4985.9  189.77  4986.1  189.27
  4989.6  189.27  4989.9  189.77  5042.1  190.84  5072.4  192.29  5078.9  191.64
  5093.2  191.84  5099.7  191.36  5199.2  192.12  5255.9  193.57  5270.2  193.12
  5358.4  194.43    5377  194.98  5419.9  195.51  5426.5  195.31  5533.2  197.89
  5554.7  197.81  5561.8   198.3  5639.9  199.41  5746.7  202.01    5789  202.58
#Mann= 8 ,-1 , 0
  4405.9     .05       0  4616.1     .07       0  4721.9     .05       0
  4985.9     .05       0  4989.9     .05       0  5042.1     .07       0
  5199.2     .12       0  5358.4     .07       0
Bank Sta=4985.9,4989.9
XS Rating Curve= 0 ,0
Exp/Cntr=0.3,0.1

Type RM Length L Ch R = 1 ,1463    ,107,107,107
BEGIN DESCRIPTION:
TRIB 6 TO HOG THIEF CREEK 3.0
END DESCRIPTION:
XS GIS Cut Line= 3
      2521375.02     13483725.01        2521975.       13483925.
      2522575.02     13483374.98
#Sta/Elev= 30
  4373.3  198.23  4478.7  196.76  4584.1  193.79  4668.4   192.6    4679  191.81
  4689.5  192.21  4738.7  191.85  4913.6  188.37  4931.9     188    4953  188.53
  4963.6  188.17  4995.2  188.36  5010.8  187.87  5011.1  187.37  5014.6  187.37
  5014.8  187.87  5019.8  188.01  5041.2  188.79  5090.5  188.99  5156.7  189.94
  5182.7  190.26  5267.5     191    5310  192.12  5430.5  193.63  5465.8  194.07
  5472.8  194.51  5607.4  196.45  5740.3  198.94  5765.3  199.29  5819.7  200.27
#Mann= 13 ,-1 , 0
  4373.3     .05       0  4738.7     .07       0  4913.6      .1       0
  5010.8     .05       0  5014.8      .1       0  5019.8     .05       0
  5156.7     .07       0  5182.7     .12       0  5430.5     .07       0
  5465.8     .12       0  5607.4     .07       0  5740.3     .12       0
  5765.3     .07       0
Bank Sta=5010.8,5014.8
XS Rating Curve= 0 ,0
Exp/Cntr=0.3,0.1

Type RM Length L Ch R = 1 ,1356    ,103,103,103
BEGIN DESCRIPTION:
Mapping XS b1337fd1
END DESCRIPTION:
XS GIS Cut Line= 3
       2521511.2     13483958.76      2521969.51     13484031.67
      2522444.65     13483809.71
#Sta/Elev= 30
  4529.8  194.57  4663.5  192.48  4679.3  192.05  4724.8  191.78  4817.2  190.53
  4854.3  189.13  4888.1  188.31  4916.5  188.09  4928.6  187.54  4969.1  187.23
  4978.7  186.76  4983.7  186.99  4989.1  186.15  4993.9  186.15  4994.1  184.03
  4994.4  183.53  4997.9  183.53  4998.1  184.03  5001.6  184.22  5012.8  186.59
    5019  187.19  5039.8  187.33  5144.3   188.9  5227.9  189.72  5286.8  190.69
  5309.7  191.28  5372.8  191.62  5386.2   192.1  5447.7  192.77  5518.3  193.97
#Mann= 10 ,-1 , 0
  4529.8     .05       0  4663.5     .07       0  4679.3     .05       0
  4994.1     .05       0  4998.1     .05       0  5012.8      .1       0
  5039.8     .05       0  5227.9     .12       0  5286.8     .07       0
  5447.7     .12       0
Bank Sta=4994.1,4998.1
XS Rating Curve= 0 ,0
Exp/Cntr=0.3,0.1

Type RM Length L Ch R = 1 ,1253    ,281,281,281
BEGIN DESCRIPTION:
Mapping XS 12c3beed
END DESCRIPTION:
XS GIS Cut Line= 3
      2521559.06     13484102.04       2521982.7     13484133.29
      2522401.45     13483984.48
#Sta/Elev= 30
  4583.4  192.96  4709.6  190.98    4808   189.8  4920.3  187.48  4980.4  186.82
  4990.4  185.46  5004.8  184.34  5005.1  183.84  5008.6  183.84  5008.8  184.34
  5012.1  184.34    5017  185.12  5022.3  184.96  5028.4  185.92  5031.9  186.47
  5042.5  186.93  5095.5  187.12  5116.5  187.56  5135.1  188.08  5148.6  187.85
  5165.9   188.4  5171.2  188.16  5253.2  188.85  5297.2  189.97  5314.9  189.75
  5320.6  189.94  5371.3  190.26  5379.2  190.59    5426   190.8  5452.6  191.18
#Mann= 10 ,-1 , 0
  4583.4     .05       0  4709.6     .07       0    4808     .05       0
  5004.8     .05       0  5008.8     .05       0  5028.4      .1       0
  5116.5     .05       0  5320.6     .07       0  5379.2     .12       0
    5426     .07       0
Bank Sta=5004.8,5008.8
XS Rating Curve= 0 ,0
Exp/Cntr=0.3,0.1

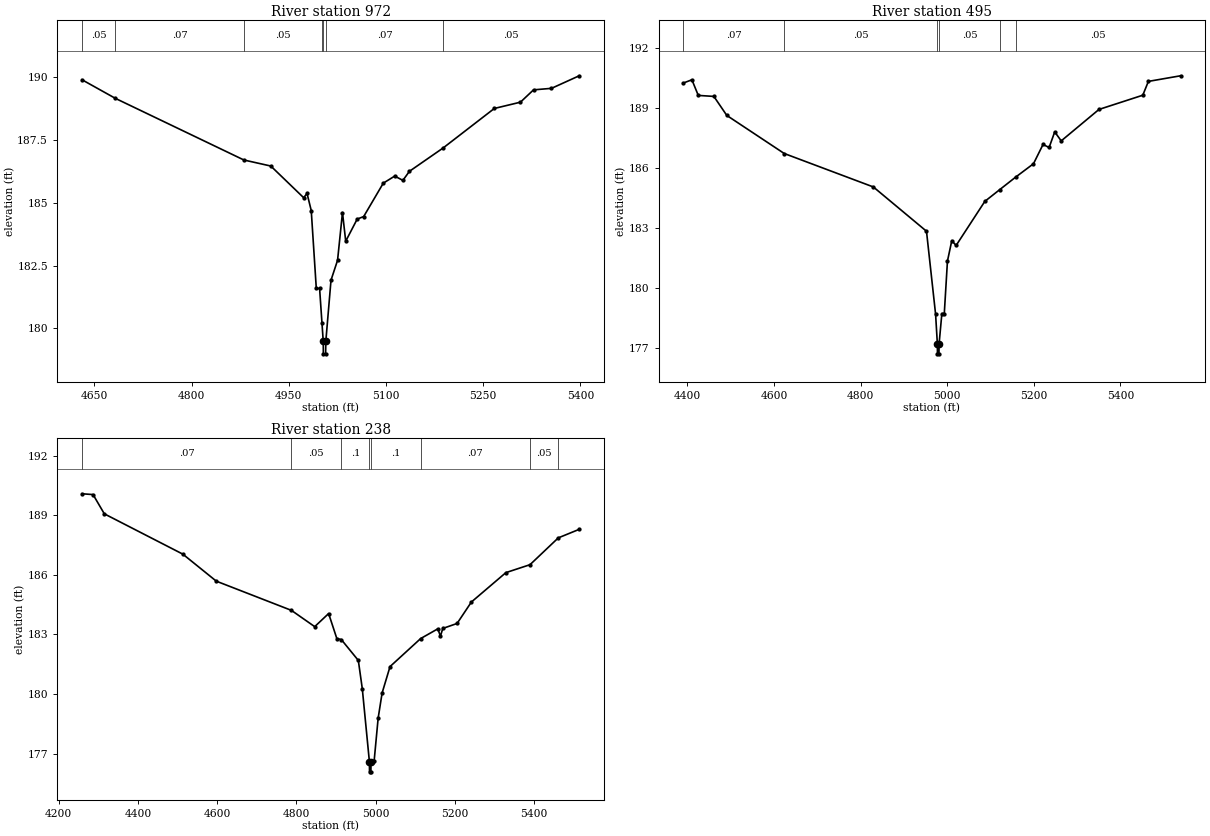
Type RM Length L Ch R = 1 ,972     ,477,477,477
BEGIN DESCRIPTION:
TRIB 6 TO HOG THIEF CREEK 2.0
END DESCRIPTION:
XS GIS Cut Line= 3
      2521725.01       13484275.        2522075.       13484375.
      2522474.99       13484425.
#Sta/Elev= 30
    4631  189.89  4682.5  189.15  4880.7   186.7  4922.2  186.46  4972.9   185.2
  4978.1  185.37  4984.6  184.69  4992.4  181.59  4997.5  181.59  5001.2   180.2
  5003.1  179.49  5003.3  178.99  5006.8  178.99  5007.1  179.49  5015.1  181.92
  5025.2  182.71  5032.8  184.61  5037.8  183.47  5055.5  184.35  5065.5  184.45
  5095.8  185.78  5113.4  186.06    5126  185.89  5136.1  186.25  5188.2  187.18
  5267.1  188.75  5307.4     189  5327.6  189.49  5355.3  189.55  5398.1  190.05
#Mann= 7 ,-1 , 0
    4631     .05       0  4682.5     .07       0  4880.7     .05       0
  5001.2     .07       0  5003.1     .05       0  5007.1     .07       0
  5188.2     .05       0
Bank Sta=5003.1,5007.1
XS Rating Curve= 0 ,0
Exp/Cntr=0.3,0.1

Type RM Length L Ch R = 1 ,495     ,257,257,257
BEGIN DESCRIPTION:
Mapping XS ad6e7fdb
END DESCRIPTION:
XS GIS Cut Line= 4
      2521618.78     13484472.62      2522115.34     13484809.45
      2522212.56     13484805.98      2522587.56     13484555.98
#Sta/Elev= 30
  4390.7  190.25  4410.3  190.41    4425  189.63    4461  189.58  4490.9  188.63
  4623.5  186.73  4829.3  185.06    4952  182.85    4973  178.71  4977.1  177.23
  4977.3  176.73  4980.8  176.73  4981.1  177.23  4987.5  178.74  4993.1  178.74
  5000.4  181.36  5010.4  182.38  5020.4  182.14  5086.7  184.34  5121.3  184.93
  5157.8  185.55  5199.1  186.22  5221.1  187.18  5235.2  187.03  5248.1  187.81
  5263.1  187.36  5350.3  188.93  5451.5  189.64  5464.4  190.33  5538.7  190.61
#Mann= 6 ,-1 , 0
  4390.7     .07       0  4623.5     .05       0  4977.1     .05       0
  4981.1     .05       0  5121.3     .12       0  5157.8     .05       0
Bank Sta=4977.1,4981.1
XS Rating Curve= 0 ,0
Exp/Cntr=0.3,0.1

Type RM Length L Ch R = 1 ,238     ,0,0,0
BEGIN DESCRIPTION:
TRIB 6 TO HOG THIEF CREEK 1.0
END DESCRIPTION:
XS GIS Cut Line= 4
      2521563.24     13484608.05      2522042.42     13485038.62
       2522233.4     13485038.62      2522581.15     13484805.22
#Sta/Elev= 30
  4259.3  190.08    4287  190.04  4315.4  189.07  4513.5  187.04  4597.9  185.68
  4787.3  184.21  4846.1  183.39  4881.2  184.05  4901.9  182.79  4913.2  182.74
  4956.1  181.69  4966.1  180.27  4984.1  176.58  4984.3  176.08  4987.8  176.08
  4988.1  176.58  4996.1  176.65  5006.1  178.78  5016.1  180.05  5036.1  181.38
  5113.3  182.79  5156.6  183.28  5163.2  182.91  5169.2   183.3  5205.2  183.55
  5241.3  184.63  5328.3  186.11  5389.2  186.51  5460.5  187.86  5513.3  188.29
#Mann= 8 ,-1 , 0
  4259.3     .07       0  4787.3     .05       0  4913.2      .1       0
  4984.1     .05       0  4988.1      .1       0  5113.3     .07       0
  5389.2     .05       0  5460.5     .07       0
Bank Sta=4984.1,4988.1
XS Rating Curve= 0 ,0
Exp/Cntr=0.3,0.1

Chan Stop Cuts=-1
Use User Specified Reach Order=0
Composite Channel Slope=5