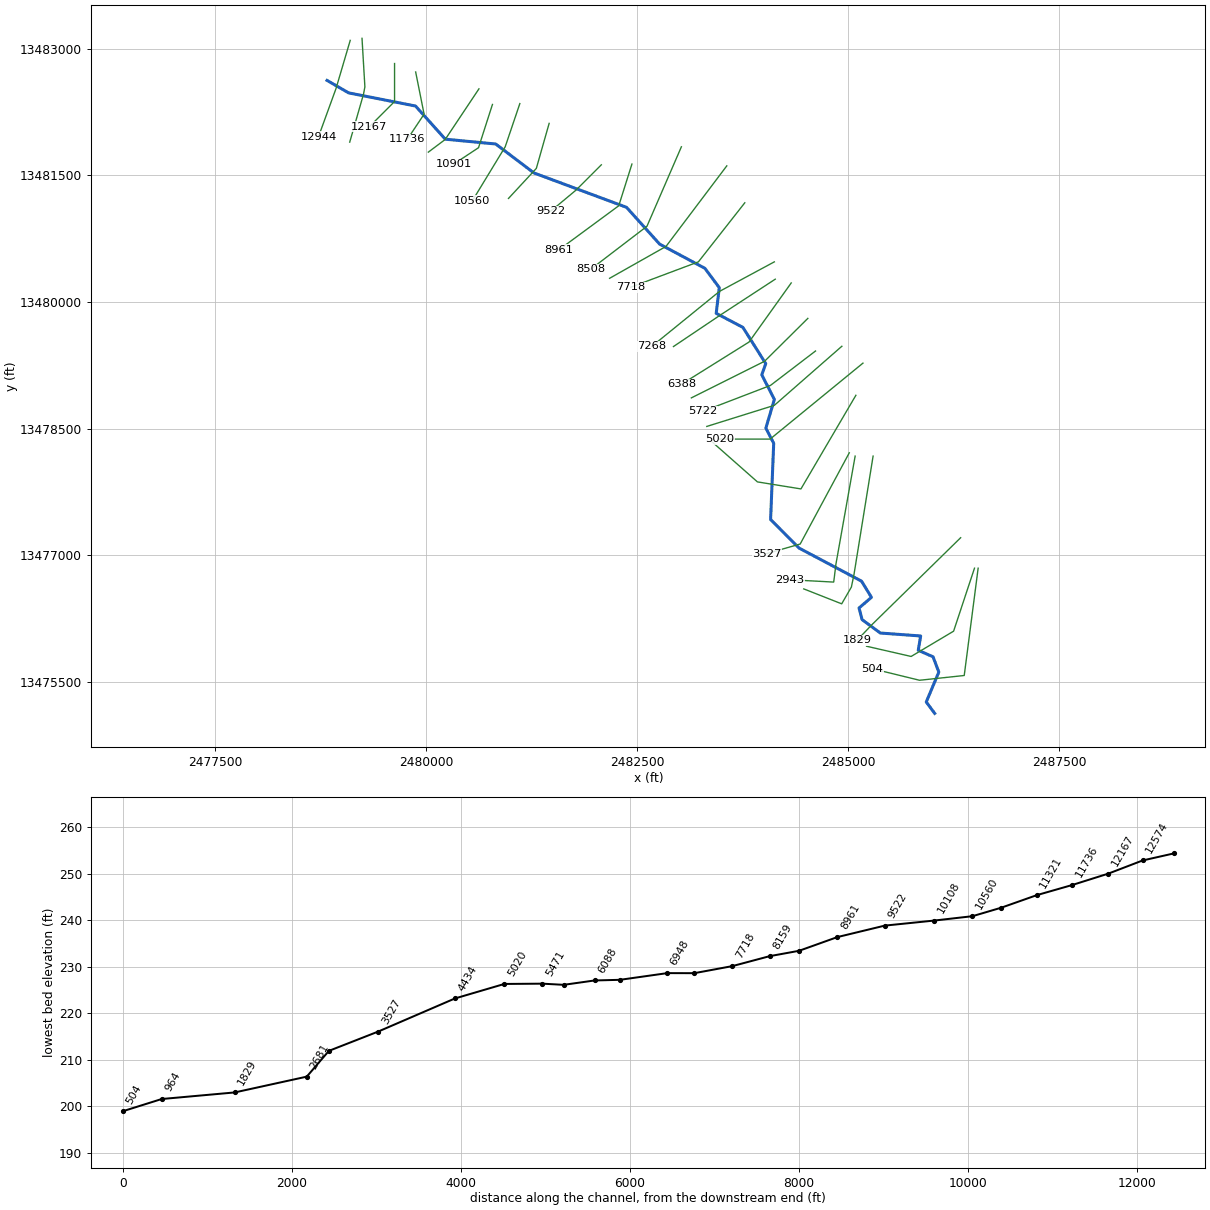
--- TRIB 6 TO PERDIDO CREEK.prj (project) ---

Proj Title=TRIB 6 TO PERDIDO CREEK Detailed Study
Current Plan=p01
Default Exp/Contr=0.3,0.1
English Units
Geom File=g01
Flow File=f01
Plan File=p01
BEGIN DESCRIPTION:
TRIB 6 TO PERDIDO CREEK
END DESCRIPTION:

--- TRIB 6 TO PERDIDO CREEK.p01 (plan) ---

Plan Title=Multiple Run
Short Identifier=Multiple
Geom File=g01
Flow File=f01
Subcritical Flow
K Sum by GR= 0
Std Step Tol= 0.01
Critical Tol= 0.01
Num of Std Step Trials= 20
Max Error Tol= 0.3
Flow Tol Ratio= 0.001
Split Flow NTrial= 30
Split Flow Tol= 0.02
Split Flow Ratio= 0.02
Log Output Level= 0
Friction Slope Method= 1
Unsteady Friction Slope Method= 2
Unsteady Bridges Friction Slope Method= 1
Parabolic Critical Depth
Global Vel Dist=  1 , 1 , 1
Global Log Level= 0
CheckData=True
Encroach Param= -1, 0, 0, 0
BEGIN DESCRIPTION:
Multiple Run
END DESCRIPTION:

--- TRIB 6 TO PERDIDO CREEK.f01 (steady flow) ---

Flow Title=Multiple
Number of Profiles=4
Profile Names=10-year,50-year,100-year,500-year
River Rch & RM= TRIB 6 TO PERDID,Reach-1,12944
     300     500     600     700
Boundary for River Rch & Prof#=TRIB 6 TO PERDID,Reach-1,1
Up Type=0
Dn Type=3
Dn Slope=0.005
Boundary for River Rch & Prof#=TRIB 6 TO PERDID,Reach-1,2
Up Type=0
Dn Type=3
Dn Slope=0.005
Boundary for River Rch & Prof#=TRIB 6 TO PERDID,Reach-1,3
Up Type=0
Dn Type=3
Dn Slope=0.005
Boundary for River Rch & Prof#=TRIB 6 TO PERDID,Reach-1,4
Up Type=0
Dn Type=3
Dn Slope=0.005

--- TRIB 6 TO PERDIDO CREEK.g01 (geometry) ---

Geom Title=Existing Conditions

River Reach=TRIB 6 TO PERDID,Reach-1
Reach XY= 30
      2478825.00     13482625.00      2479080.97     13482477.17
      2479873.50     13482321.39      2480226.25     13481928.46
      2480823.50     13481871.53      2481276.47     13481528.54
      2482373.42     13481121.18      2482765.32     13480685.78
      2483302.01     13480398.52      2483472.94     13480169.15
      2483436.10     13479864.89      2483752.28     13479698.89
      2484023.38     13479268.96      2483976.20     13479137.02
      2484125.36     13478845.15      2484024.60     13478504.87
      2484117.47     13478325.01      2484080.70     13477422.46
      2484418.67     13477083.04      2485158.36     13476691.71
      2485275.62     13476499.91      2485128.37     13476373.71
      2485164.94     13476235.63      2485380.85     13476077.06
      2485858.86     13476042.09      2485830.28     13475872.29
      2486005.57     13475795.64      2486073.90     13475614.45
      2485925.00     13475259.59      2486025.00     13475125.00

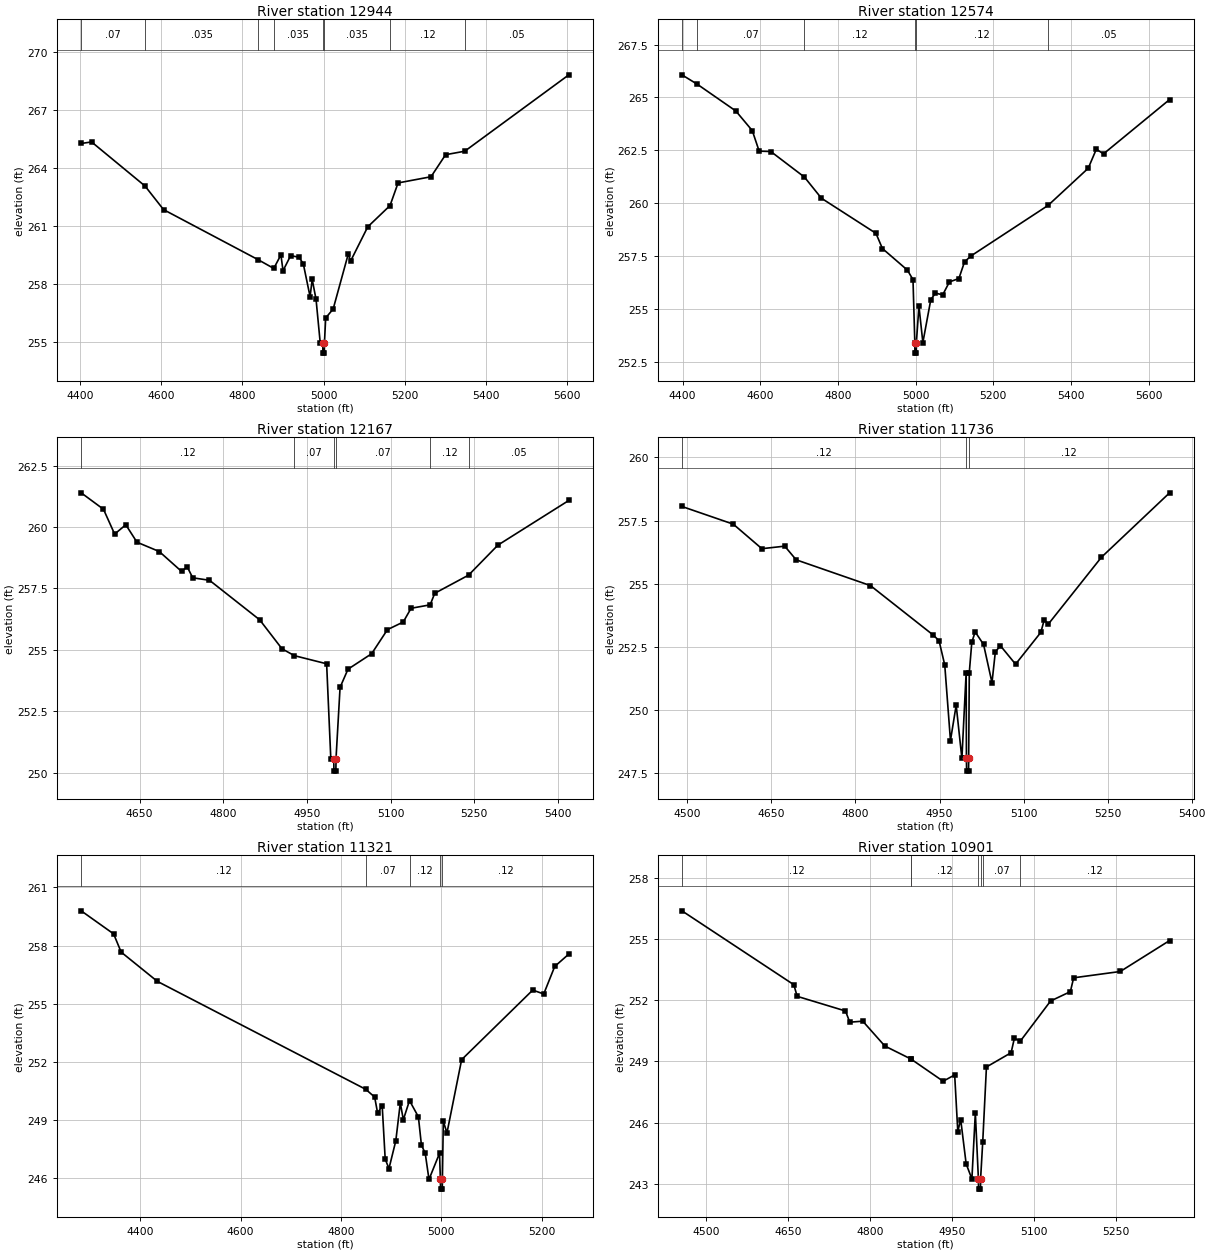
Type RM Length L Ch R = 1,12944,370,370,370
BEGIN DESCRIPTION:
TRIB 6 TO PERDIDO CREEK 24.0
END DESCRIPTION:
XS GIS Cut Line= 3
      2479099.76     13483099.52      2478930.88     13482527.12
      2478724.51     13481959.78
#Sta/Elev= 30
  4403.2  265.26  4428.8  265.34  4560.4  263.06  4606.0  261.84  4838.9  259.25
  4877.3  258.80  4894.9  259.50  4900.1  258.68  4918.8  259.46  4939.6  259.38
  4950.1  259.03  4966.7  257.34  4971.9  258.23  4981.4  257.20  4991.8  254.92
  4998.0  254.92  4998.3  254.42  5001.8  254.42  5002.0  254.92  5005.1  256.24
  5023.5  256.70  5060.9  259.56  5066.2  259.17  5108.7  260.95  5163.5  262.05
  5183.3  263.22  5264.4  263.54  5300.3  264.68  5347.4  264.86  5603.7  268.81
#Mann=8,-1,0
  4403.2    0.07       0  4560.4   0.035       0  4838.9    0.07       0
  4877.3   0.035       0  4998.0   0.035       0  5002.0   0.035       0
  5163.5    0.12       0  5347.4    0.05       0
Bank Sta=4998,5002
Exp/Cntr=0.3,0.1

Type RM Length L Ch R = 1,12574,407,407,407
BEGIN DESCRIPTION:
Mapping XS 32352395
END DESCRIPTION:
XS GIS Cut Line= 4
      2479239.49     13483123.49      2479273.43     13482548.51
      2479257.46     13482462.67      2479093.76     13481893.74
#Sta/Elev= 30
  4398.5  266.07  4438.4  265.62  4537.2  264.36  4579.6  263.43  4597.3  262.46
  4627.4  262.44  4713.9  261.23  4757.6  260.23  4897.9  258.57  4914.6  257.85
  4978.8  256.83  4993.3  256.38  4998.0  253.40  4998.3  252.90  5001.8  252.90
  5002.0  253.40  5008.6  255.12  5018.7  253.40  5039.1  255.43  5051.1  255.74
  5069.8  255.66  5087.1  256.27  5111.4  256.43  5126.0  257.22  5142.6  257.50
  5341.0  259.89  5444.4  261.65  5465.2  262.55  5483.7  262.33  5653.8  264.90
#Mann=6,-1,0
  4398.5    0.12       0  4438.4    0.07       0  4713.9    0.12       0
  4998.0    0.05       0  5002.0    0.12       0  5341.0    0.05       0
Bank Sta=4998,5002
Exp/Cntr=0.3,0.1

Type RM Length L Ch R = 1,12167,431,431,431
BEGIN DESCRIPTION:
TRIB 6 TO PERDIDO CREEK 23.0
END DESCRIPTION:
XS GIS Cut Line= 3
      2479625.00     13482824.98      2479625.00     13482375.00
      2479325.03     13482075.03
#Sta/Elev= 30
  4545.2  261.39  4585.2  260.72  4605.2  259.71  4625.2  260.09  4645.2  259.38
  4685.2  259.00  4725.2  258.19  4735.2  258.38  4745.2  257.93  4775.2  257.83
  4865.2  256.22  4905.2  255.04  4927.5  254.76  4985.2  254.43  4992.7  250.56
  4998.0  250.56  4998.3  250.06  5001.8  250.06  5002.0  250.56  5009.3  253.47
  5023.5  254.21  5065.9  254.84  5094.2  255.82  5122.5  256.13  5136.6  256.69
  5170.8  256.83  5179.0  257.30  5239.7  258.04  5292.2  259.26  5419.4  261.08
#Mann=6,-1,0
  4545.2    0.12       0  4927.5    0.07       0  4998.0    0.05       0
  5002.0    0.07       0  5170.8    0.12       0  5239.7    0.05       0
Bank Sta=4998,5002
Exp/Cntr=0.3,0.1

Type RM Length L Ch R = 1,11736,415,415,415
BEGIN DESCRIPTION:
TRIB 6 TO PERDIDO CREEK 22.0
END DESCRIPTION:
XS GIS Cut Line= 3
      2479875.01     13482724.96      2479975.00     13482225.00
      2479775.01     13481925.02
#Sta/Elev= 30
  4490.2  258.06  4581.9  257.36  4632.9  256.39  4673.7  256.49  4694.1  255.95
  4826.7  254.93  4938.9  252.97  4949.1  252.75  4959.3  251.79  4969.5  248.80
  4979.7  250.20  4989.9  248.09  4997.5  251.49  4998.0  248.09  4998.3  247.59
  5001.8  247.59  5002.0  248.09  5003.1  251.49  5007.6  252.69  5013.6  253.10
  5028.6  252.60  5043.6  251.09  5049.6  252.31  5058.7  252.55  5085.7  251.82
  5130.8  253.08  5136.8  253.57  5144.3  253.41  5238.9  256.05  5360.6  258.60
#Mann=3,-1,0
  4490.2    0.12       0  4998.0    0.05       0  5002.0    0.12       0
Bank Sta=4998,5002
Exp/Cntr=0.3,0.1

Type RM Length L Ch R = 1,11321,420,420,420
BEGIN DESCRIPTION:
TRIB 6 TO PERDIDO CREEK 21.0
END DESCRIPTION:
XS GIS Cut Line= 3
      2480625.00     13482525.00      2480225.00     13481925.00
      2480025.01     13481775.01
#Sta/Elev= 30
  4282.7  259.79  4347.3  258.60  4362.3  257.66  4434.4  256.15  4849.4  250.58
  4867.1  250.18  4873.1  249.34  4882.1  249.74  4888.1  246.98  4895.6  246.49
  4909.2  247.92  4918.2  249.88  4924.2  249.01  4936.5  250.00  4954.2  249.16
  4960.2  247.71  4967.8  247.28  4975.3  245.93  4996.3  247.28  4998.0  245.93
  4998.3  245.43  5001.8  245.43  5002.0  245.93  5003.8  248.93  5011.1  248.33
  5040.3  252.11  5181.9  255.70  5203.8  255.50  5225.7  256.92  5253.8  257.56
#Mann=5,-1,0
  4282.7    0.12       0  4849.4    0.07       0  4936.5    0.12       0
  4998.0    0.05       0  5002.0    0.12       0
Bank Sta=4998,5002
Exp/Cntr=0.3,0.1

Type RM Length L Ch R = 1,10901,341,341,341
BEGIN DESCRIPTION:
Mapping XS f6644389
END DESCRIPTION:
XS GIS Cut Line= 3
      2480784.85     13482339.84      2480619.91     13481827.66
      2480324.78     13481632.34
#Sta/Elev= 30
  4455.7  256.40  4660.4  252.77  4666.5  252.20  4754.9  251.48  4762.7  250.93
  4786.5  250.98  4826.8  249.76  4874.7  249.12  4875.2  249.11  4933.5  248.03
  4954.6  248.34  4960.3  245.56  4965.6  246.15  4975.6  243.97  4986.1  243.23
  4992.4  246.48  4998.0  243.23  4998.3  242.73  5001.8  242.73  5002.0  243.23
  5005.9  245.04  5012.7  248.73  5057.8  249.43  5063.8  250.14  5074.7  250.00
  5130.0  251.97  5166.2  252.43  5172.2  253.11  5257.5  253.42  5347.7  254.94
#Mann=7,-1,0
  4455.7    0.12       0  4874.7    0.07       0  4875.2    0.12       0
  4998.0    0.05       0  5002.0    0.12       0  5005.9    0.07       0
  5074.7    0.12       0
Bank Sta=4998,5002
Exp/Cntr=0.3,0.1

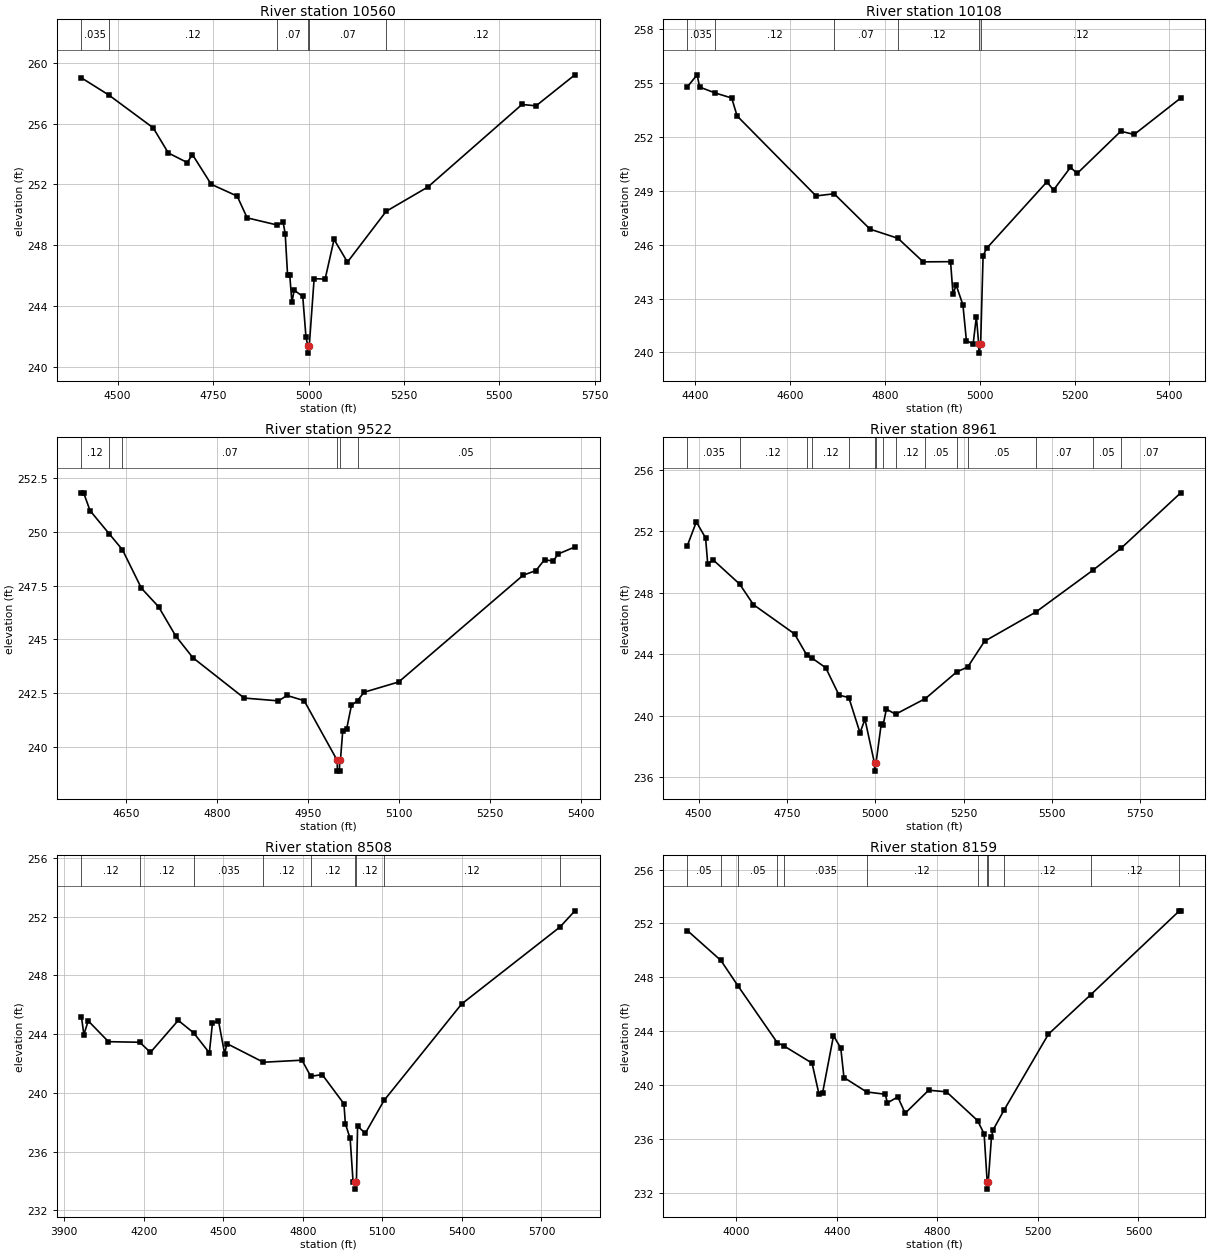
Type RM Length L Ch R = 1,10560,452,452,452
BEGIN DESCRIPTION:
Mapping XS f43fbdcd
END DESCRIPTION:
XS GIS Cut Line= 3
      2481109.54     13482350.45      2480935.93     13481838.30
      2480545.30     13481195.92
#Sta/Elev= 30
  4405.2  259.01  4476.9  257.88  4593.2  255.72  4632.7  254.07  4682.2  253.44
  4696.0  253.96  4745.0  252.01  4813.1  251.23  4839.2  249.80  4917.8  249.33
  4933.5  249.51  4938.9  248.76  4945.1  246.05  4950.8  246.05  4956.5  244.24
  4962.4  245.04  4984.9  244.63  4993.3  241.96  4998.0  241.40  4998.3  240.90
  5002.0  241.40  5014.7  245.80  5043.5  245.77  5066.9  248.38  5102.0  246.89
  5203.4  250.23  5312.7  251.83  5559.2  257.26  5596.0  257.17  5697.8  259.21
#Mann=6,-1,0
  4405.2   0.035       0  4476.9    0.12       0  4917.8    0.07       0
  4998.0    0.05       0  5002.0    0.07       0  5203.4    0.12       0
Bank Sta=4998,5002
Exp/Cntr=0.3,0.1

Type RM Length L Ch R = 1,10108,586,586,586
BEGIN DESCRIPTION:
Mapping XS a4a5f412
END DESCRIPTION:
XS GIS Cut Line= 3
      2481456.75     13482116.04      2481304.85     13481582.22
      2480974.97     13481226.29
#Sta/Elev= 30
  4383.6  254.78  4404.3  255.45  4409.5  254.77  4442.3  254.44  4477.2  254.16
  4488.6  253.16  4655.0  248.71  4693.2  248.83  4768.9  246.86  4827.8  246.35
  4880.9  245.04  4938.6  245.05  4943.7  243.26  4950.5  243.74  4964.7  242.64
  4972.0  240.66  4986.2  240.46  4993.0  241.99  4998.0  240.46  4998.3  239.96
  5002.0  240.46  5007.2  245.38  5014.6  245.79  5141.6  249.49  5155.7  249.04
  5191.4  250.30  5205.6  249.96  5297.5  252.31  5325.8  252.13  5423.9  254.16
#Mann=6,-1,0
  4383.6   0.035       0  4442.3    0.12       0  4693.2    0.07       0
  4827.8    0.12       0  4998.0    0.05       0  5002.0    0.12       0
Bank Sta=4998,5002
Exp/Cntr=0.3,0.1

Type RM Length L Ch R = 1,9522,561,561,561
BEGIN DESCRIPTION:
TRIB 6 TO PERDIDO CREEK 17.0
END DESCRIPTION:
XS GIS Cut Line= 3
      2482075.02     13481625.02      2481775.00     13481325.00
      2481475.01     13481075.01
#Sta/Elev= 30
  4575.7  251.82  4579.3  251.82  4589.9  250.99  4621.3  249.92  4643.4  249.17
  4674.7  247.38  4703.0  246.52  4731.3  245.16  4759.6  244.15  4844.4  242.27
  4901.0  242.14  4915.1  242.39  4943.4  242.15  4998.0  239.37  4998.3  238.87
  5001.8  238.87  5002.0  239.37  5003.3  239.37  5007.2  240.76  5013.7  240.85
  5021.5  241.93  5031.6  242.15  5042.3  242.54  5099.6  243.02  5305.2  247.99
  5326.1  248.20  5340.4  248.71  5354.7  248.64  5362.5  248.97  5390.5  249.30
#Mann=6,-1,0
  4575.7    0.12       0  4621.3   0.035       0  4643.4    0.07       0
  4998.0    0.05       0  5002.0    0.07       0  5031.6    0.05       0
Bank Sta=4998,5002
Exp/Cntr=0.3,0.1

Type RM Length L Ch R = 1,8961,453,453,453
BEGIN DESCRIPTION:
Mapping XS 17b369ec
END DESCRIPTION:
XS GIS Cut Line= 3
      2482437.68     13481634.33      2482281.42     13481139.51
      2481574.85     13480619.34
#Sta/Elev= 30
  4468.2  251.05  4493.7  252.60  4519.9  251.56  4526.0  249.86  4540.9  250.14
  4616.2  248.56  4655.4  247.22  4771.6  245.32  4806.4  243.94  4820.9  243.75
  4859.9  243.12  4897.5  241.34  4925.3  241.18  4956.9  238.89  4970.9  239.77
  4998.0  236.90  4998.3  236.40  5002.0  236.90  5016.9  239.46  5022.6  239.43
  5031.5  240.43  5057.6  240.10  5142.2  241.12  5230.6  242.85  5261.8  243.17
  5309.2  244.84  5454.4  246.74  5615.4  249.45  5695.2  250.88  5864.5  254.49
#Mann=15,-1,0
  4468.2   0.035       0  4616.2    0.12       0  4806.4    0.07       0
  4820.9    0.12       0  4925.3    0.12       0  4998.0    0.05       0
  5002.0    0.12       0  5022.6    0.07       0  5057.6    0.12       0
  5142.2    0.05       0  5230.6    0.07       0  5261.8    0.05       0
  5454.4    0.07       0  5615.4    0.05       0  5695.2    0.07       0
Bank Sta=4998,5002
Exp/Cntr=0.3,0.1

Type RM Length L Ch R = 1,8508,349,349,349
BEGIN DESCRIPTION:
Mapping XS 35ed39ef
END DESCRIPTION:
XS GIS Cut Line= 3
      2483023.61     13481838.31      2482615.62     13480896.46
      2481952.43     13480389.31
#Sta/Elev= 30
  3964.9  245.17  3974.0  243.97  3990.3  244.91  4066.6  243.49  4184.8  243.45
  4225.1  242.76  4329.9  244.94  4388.2  244.09  4447.3  242.73  4458.9  244.73
  4481.7  244.92  4505.1  242.66  4513.4  243.36  4651.2  242.09  4796.8  242.23
  4829.8  241.13  4873.0  241.25  4955.0  239.26  4960.4  237.90  4978.4  236.90
  4989.4  233.95  4998.0  233.95  4998.3  233.45  5002.0  233.95  5006.5  237.74
  5035.5  237.25  5106.3  239.49  5399.1  246.06  5770.1  251.30  5826.2  252.40
#Mann=9,-1,0
  3964.9    0.12       0  4184.8    0.12       0  4388.2   0.035       0
  4651.2    0.12       0  4829.8    0.12       0  4998.0    0.05       0
  5002.0    0.12       0  5106.3    0.12       0  5770.1    0.07       0
Bank Sta=4998,5002
Exp/Cntr=0.3,0.1

Type RM Length L Ch R = 1,8159,441,441,441
BEGIN DESCRIPTION:
Mapping XS b2719491
END DESCRIPTION:
XS GIS Cut Line= 3
      2483561.78     13481612.58      2482841.31     13480657.74
      2482172.95     13480280.16
#Sta/Elev= 30
  3804.5  251.48  3938.1  249.26  4006.2  247.37  4162.4  243.16  4191.2  242.89
  4300.9  241.64  4328.0  239.38  4342.6  239.40  4386.3  243.67  4415.3  242.76
  4427.9  240.57  4518.2  239.50  4592.4  239.33  4600.7  238.69  4642.3  239.13
  4671.5  237.92  4765.1  239.63  4835.9  239.51  4959.5  237.38  4985.8  236.39
  4998.0  232.79  4998.3  232.29  5002.0  232.79  5015.0  236.15  5020.8  236.66
  5065.9  238.18  5241.7  243.79  5410.9  246.73  5762.3  252.93  5768.3  252.94
#Mann=12,-1,0
  3804.5    0.05       0  3938.1    0.07       0  4006.2    0.05       0
  4162.4    0.07       0  4191.2   0.035       0  4518.2    0.12       0
  4959.5    0.12       0  4998.0    0.05       0  5002.0    0.12       0
  5065.9    0.12       0  5410.9    0.12       0  5762.3    0.07       0
Bank Sta=4998,5002
Exp/Cntr=0.3,0.1

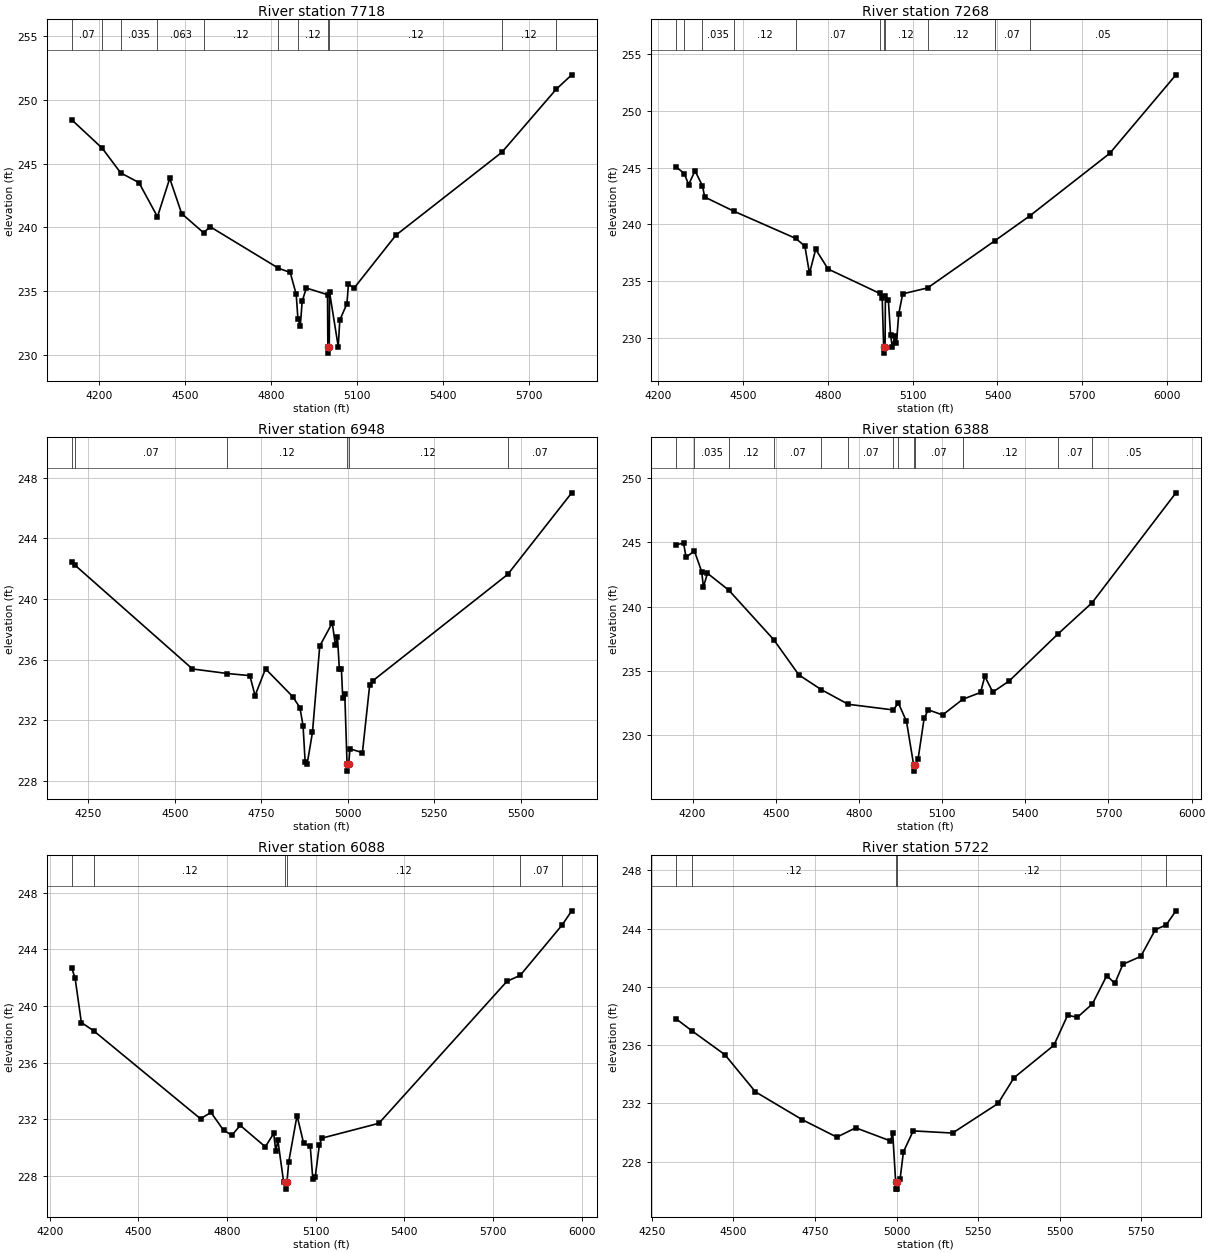
Type RM Length L Ch R = 1,7718,450,450,450
BEGIN DESCRIPTION:
TRIB 6 TO PERDIDO CREEK 13.0
END DESCRIPTION:
XS GIS Cut Line= 3
      2483774.99     13481174.99      2483225.00     13480475.00
      2482425.01     13480175.00
#Sta/Elev= 30
  4103.6  248.44  4210.7  246.20  4275.0  244.27  4338.6  243.51  4403.3  240.83
  4446.1  243.84  4487.7  241.08  4564.1  239.58  4587.1  240.05  4825.4  236.80
  4866.3  236.47  4887.2  234.76  4893.3  232.82  4901.6  232.28  4908.0  234.20
  4922.4  235.25  4996.5  234.73  4997.6  230.65  4998.0  230.15  5002.5  230.65
  5003.6  234.92  5033.9  230.65  5039.2  232.73  5064.1  234.02  5069.5  235.56
  5089.0  235.24  5235.0  239.39  5604.5  245.88  5794.1  250.82  5848.2  251.95
#Mann=11,-1,0
  4103.6    0.07       0  4210.7    0.12       0  4275.0   0.035       0
  4403.3   0.063       0  4564.1    0.12       0  4825.4    0.12       0
  4893.3    0.12       0  4997.6    0.05       0  5002.5    0.12       0
  5604.5    0.12       0  5794.1    0.07       0
Bank Sta=4997.6,5002.5
Exp/Cntr=0.3,0.1

Type RM Length L Ch R = 1,7268,320,320,320
BEGIN DESCRIPTION:
TRIB 6 TO PERDIDO CREEK 12.0
END DESCRIPTION:
XS GIS Cut Line= 3
      2484124.96     13480474.98      2483475.00     13480125.00
      2482674.98     13479474.98
#Sta/Elev= 30
  4262.3  245.08  4292.3  244.47  4307.7  243.50  4330.4  244.71  4356.8  243.38
  4364.5  242.40  4466.8  241.16  4686.7  238.75  4719.0  238.06  4735.2  235.66
  4757.1  237.79  4800.9  236.05  4983.7  233.90  4992.4  233.51  4997.6  229.13
  4997.9  228.63  5002.5  229.13  5003.7  233.65  5014.1  233.34  5022.1  230.21
  5028.5  229.13  5036.4  230.14  5042.9  229.54  5050.8  232.09  5064.9  233.86
  5152.8  234.38  5390.1  238.53  5513.9  240.73  5797.1  246.25  6031.3  253.18
#Mann=11,-1,0
  4262.3   0.035       0  4292.3   0.063       0  4356.8   0.035       0
  4466.8    0.12       0  4686.7    0.07       0  4983.7    0.12       0
  4997.6    0.05       0  5002.5    0.12       0  5152.8    0.12       0
  5390.1    0.07       0  5513.9    0.05       0
Bank Sta=4997.6,5002.5
Exp/Cntr=0.3,0.1

Type RM Length L Ch R = 1,6948,560,560,560
BEGIN DESCRIPTION:
Mapping XS 4cbf0c69
END DESCRIPTION:
XS GIS Cut Line= 3
      2484135.50     13480269.47      2483484.50     13479844.15
      2482929.47     13479471.24
#Sta/Elev= 30
  4201.0  242.44  4210.3  242.24  4550.7  235.38  4651.5  235.08  4716.6  234.94
  4731.7  233.62  4761.9  235.39  4840.3  233.56  4861.4  232.83  4870.5  231.62
  4876.5  229.24  4882.5  229.14  4897.6  231.19  4918.7  236.89  4954.9  238.42
  4964.0  236.94  4970.0  237.47  4975.3  235.41  4981.3  235.41  4985.1  233.49
  4991.1  233.72  4997.6  229.14  4997.9  228.64  5002.5  229.14  5006.1  230.11
  5042.1  229.86  5063.1  234.31  5072.1  234.60  5462.3  241.62  5647.3  247.00
#Mann=6,-1,0
  4201.0   0.035       0  4210.3    0.07       0  4651.5    0.12       0
  4997.6    0.05       0  5002.5    0.12       0  5462.3    0.07       0
Bank Sta=4997.6,5002.5
Exp/Cntr=0.3,0.1

Type RM Length L Ch R = 1,6388,300,300,300
BEGIN DESCRIPTION:
TRIB 6 TO PERDIDO CREEK 10.0
END DESCRIPTION:
XS GIS Cut Line= 3
      2484325.01     13480225.02      2483825.00     13479525.00
      2483024.96     13479024.97
#Sta/Elev= 30
  4139.7  244.81  4168.0  244.93  4176.6  243.84  4207.0  244.32  4233.1  242.72
  4239.3  241.53  4254.0  242.59  4330.7  241.28  4492.8  237.43  4583.4  234.69
  4664.4  233.54  4761.5  232.40  4924.2  231.96  4942.3  232.50  4971.7  231.07
  4997.4  227.70  4997.8  227.20  5002.6  227.70  5013.5  228.14  5035.3  231.30
  5050.1  231.97  5102.0  231.57  5174.7  232.79  5238.8  233.32  5254.1  234.57
  5283.0  233.35  5341.9  234.21  5516.4  237.84  5641.1  240.30  5943.4  248.85
#Mann=13,-1,0
  4139.7   0.063       0  4207.0   0.035       0  4330.7    0.12       0
  4492.8    0.07       0  4664.4    0.12       0  4761.5    0.07       0
  4924.2    0.12       0  4942.3    0.07       0  4997.4    0.05       0
  5002.6    0.07       0  5174.7    0.12       0  5516.4    0.07       0
  5641.1    0.05       0
Bank Sta=4997.4,5002.6
Exp/Cntr=0.3,0.1

Type RM Length L Ch R = 1,6088,366,366,366
BEGIN DESCRIPTION:
Mapping XS 98f1b9cf
END DESCRIPTION:
XS GIS Cut Line= 3
      2484521.81     13479805.08      2484009.67     13479297.27
      2483141.64     13478863.26
#Sta/Elev= 30
  4274.1  242.71  4286.0  241.98  4307.3  238.83  4349.2  238.24  4710.3  232.03
  4745.7  232.48  4788.1  231.22  4816.4  230.87  4844.7  231.56  4929.5  230.05
  4957.8  230.99  4964.9  229.77  4972.0  230.50  4991.4  227.57  4997.3  227.56
  4997.8  227.06  5002.7  227.56  5008.9  229.01  5036.8  232.26  5059.2  230.29
  5081.5  230.09  5090.0  227.81  5098.3  227.92  5112.3  230.18  5120.7  230.66
  5313.6  231.71  5746.8  241.74  5791.5  242.16  5933.5  245.72  5965.8  246.72
#Mann=6,-1,0
  4274.1   0.063       0  4349.2    0.12       0  4997.3    0.05       0
  5002.7    0.12       0  5791.5    0.07       0  5933.5    0.05       0
Bank Sta=4997.3,5002.7
Exp/Cntr=0.3,0.1

Type RM Length L Ch R = 1,5722,251,251,251
BEGIN DESCRIPTION:
Mapping XS 51bc92ce
END DESCRIPTION:
XS GIS Cut Line= 3
      2484612.99     13479418.82      2484079.12     13479010.82
      2483276.14     13478702.65
#Sta/Elev= 30
  4323.8  237.83  4372.0  237.01  4474.3  235.35  4567.8  232.80  4711.1  230.89
  4817.2  229.69  4875.0  230.33  4981.3  229.43  4988.3  229.96  4997.3  226.62
  4997.8  226.12  5002.3  226.12  5002.7  226.62  5010.8  226.79  5021.1  228.68
  5051.1  230.12  5171.5  229.97  5310.8  232.00  5359.9  233.77  5482.1  236.00
  5524.0  238.06  5554.0  237.92  5600.0  238.84  5644.0  240.78  5668.7  240.25
  5693.4  241.56  5748.1  242.10  5792.8  243.94  5825.9  244.26  5855.8  245.23
#Mann=5,-1,0
  4323.8   0.035       0  4372.0    0.12       0  4997.3    0.05       0
  5002.7    0.12       0  5825.9    0.05       0
Bank Sta=4997.3,5002.7
Exp/Cntr=0.3,0.1

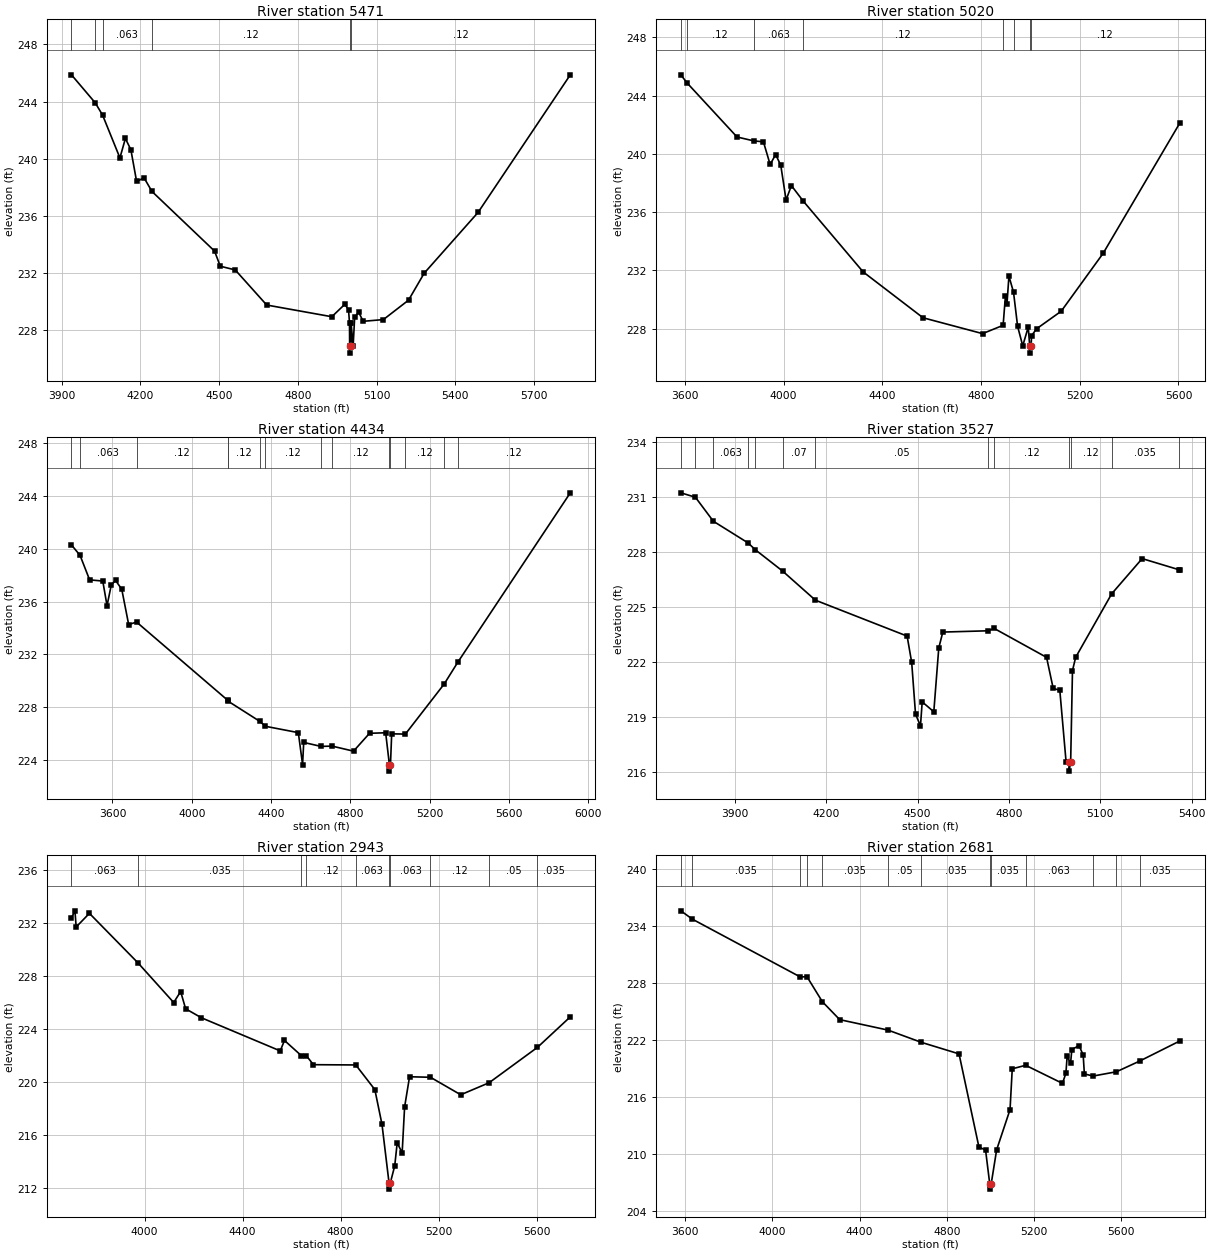
Type RM Length L Ch R = 1,5471,451,451,451
BEGIN DESCRIPTION:
TRIB 6 TO PERDIDO CREEK 8.0
END DESCRIPTION:
XS GIS Cut Line= 3
      2484925.02     13479475.01      2484125.00     13478775.00
      2483324.99     13478525.00
#Sta/Elev= 30
  3937.1  245.87  4027.6  243.91  4055.6  243.05  4121.7  240.05  4142.6  241.41
  4163.5  240.62  4185.3  238.40  4213.8  238.65  4243.8  237.70  4482.4  233.52
  4504.2  232.46  4561.2  232.20  4681.2  229.74  4929.4  228.92  4978.8  229.79
  4993.0  229.42  4996.8  228.49  4997.3  226.87  4997.7  226.37  5002.7  226.87
  5002.8  228.49  5010.6  226.87  5016.4  228.88  5031.6  229.24  5048.9  228.60
  5125.9  228.72  5221.7  230.08  5281.4  231.97  5486.8  236.23  5838.3  245.87
#Mann=6,-1,0
  3937.1    0.12       0  4027.6   0.035       0  4055.6   0.063       0
  4243.8    0.12       0  4997.3    0.05       0  5002.7    0.12       0
Bank Sta=4997.3,5002.7
Exp/Cntr=0.3,0.1

Type RM Length L Ch R = 1,5020,586,586,586
BEGIN DESCRIPTION:
TRIB 6 TO PERDIDO CREEK 7.0
END DESCRIPTION:
XS GIS Cut Line= 3
      2485174.96     13479274.97      2484075.00     13478375.00
      2483475.02     13478375.00
#Sta/Elev= 30
  3583.8  245.43  3608.0  244.89  3811.3  241.16  3879.5  240.89  3918.3  240.83
  3945.5  239.27  3967.8  239.95  3988.6  239.22  4010.1  236.83  4031.7  237.82
  4079.4  236.76  4322.4  231.89  4565.0  228.74  4806.2  227.65  4889.6  228.22
  4898.8  230.21  4905.2  229.69  4913.1  231.60  4931.7  230.50  4948.3  228.15
  4969.1  226.81  4991.4  228.10  4997.3  226.81  4997.7  226.31  5002.8  226.81
  5005.0  227.51  5025.0  227.98  5125.0  229.19  5295.0  233.17  5605.0  242.10
#Mann=8,-1,0
  3583.8   0.035       0  3608.0    0.12       0  3879.5   0.063       0
  4079.4    0.12       0  4889.6    0.12       0  4931.7    0.12       0
  4997.3    0.05       0  5002.8    0.12       0
Bank Sta=4997.3,5002.8
Exp/Cntr=0.3,0.1

Type RM Length L Ch R = 1,4434,907,907,907
BEGIN DESCRIPTION:
Mapping XS 0013da0b
END DESCRIPTION:
XS GIS Cut Line= 4
      2485091.23     13478893.93      2484440.27     13477784.48
      2483924.65     13477867.81      2483393.41     13478336.55
#Sta/Elev= 30
  3393.1  240.28  3436.4  239.49  3484.6  237.64  3551.0  237.55  3572.5  235.69
  3593.9  237.25  3615.4  237.60  3646.8  236.93  3681.7  234.26  3721.6  234.45
  4180.4  228.55  4185.3  228.45  4343.6  226.94  4371.6  226.57  4537.8  226.09
  4559.2  223.68  4565.0  225.35  4651.8  225.05  4708.6  225.07  4816.4  224.69
  4897.2  226.04  4978.5  226.08  4997.3  223.68  4997.7  223.18  5002.8  223.68
  5008.9  226.00  5078.0  225.98  5274.0  229.77  5342.4  231.41  5910.2  244.22
#Mann=14,-1,0
  3393.1   0.035       0  3436.4   0.063       0  3721.6    0.12       0
  4180.4    0.07       0  4185.3    0.12       0  4343.6    0.07       0
  4371.6    0.12       0  4651.8    0.07       0  4708.6    0.12       0
  4997.3    0.05       0  5002.8    0.12       0  5078.0    0.12       0
  5274.0    0.07       0  5342.4    0.12       0
Bank Sta=4997.3,5002.8
Exp/Cntr=0.3,0.1

Type RM Length L Ch R = 1,3527,584,584,584
BEGIN DESCRIPTION:
Mapping XS b29a3603
END DESCRIPTION:
XS GIS Cut Line= 3
      2485013.09     13478212.47      2484431.50     13477131.76
      2484036.57     13477018.92
#Sta/Elev= 30
  3722.8  231.25  3770.5  231.01  3829.4  229.70  3943.1  228.52  3967.6  228.14
  4056.8  226.98  4164.6  225.39  4465.8  223.43  4480.8  221.99  4493.4  219.17
  4509.6  218.53  4515.3  219.84  4553.4  219.30  4569.7  222.78  4583.0  223.65
  4732.3  223.72  4751.5  223.85  4923.7  222.27  4945.4  220.58  4967.2  220.47
  4987.8  216.56  4997.3  216.56  4997.7  216.06  5002.8  216.56  5008.8  221.55
  5019.2  222.27  5137.6  225.74  5237.6  227.66  5357.1  227.06  5360.8  227.06
#Mann=13,-1,0
  3722.8   0.063       0  3770.5    0.12       0  3829.4   0.063       0
  3943.1    0.07       0  3967.6    0.05       0  4056.8    0.07       0
  4164.6    0.05       0  4732.3    0.07       0  4751.5    0.12       0
  4997.3    0.05       0  5002.8    0.12       0  5137.6   0.035       0
  5357.1    0.12       0
Bank Sta=4997.3,5002.8
Exp/Cntr=0.3,0.1

Type RM Length L Ch R = 1,2943,262,262,262
BEGIN DESCRIPTION:
Mapping XS 9e7c7c9c
END DESCRIPTION:
XS GIS Cut Line= 5
      2485082.54     13478173.41      2484855.16     13476895.38
      2484836.92     13476747.33      2484828.22     13476680.61
      2484308.73     13476708.56
#Sta/Elev= 30
  3701.9  232.38  3716.0  232.90  3721.0  231.68  3775.0  232.71  3973.3  228.97
  4118.9  225.98  4147.2  226.81  4167.5  225.51  4231.9  224.83  4553.5  222.33
  4570.7  223.12  4639.7  221.97  4660.4  221.96  4688.8  221.29  4861.7  221.27
  4939.4  219.41  4968.6  216.78  4997.1  212.40  4997.6  211.90  5003.0  212.40
  5020.5  213.66  5030.6  215.39  5050.8  214.64  5060.8  218.10  5081.0  220.38
  5166.3  220.34  5289.8  219.02  5405.7  219.93  5602.9  222.60  5736.7  224.90
#Mann=10,-1,0
  3701.9   0.063       0  3973.3   0.035       0  4639.7    0.07       0
  4660.4    0.12       0  4861.7   0.063       0  4997.1    0.05       0
  5003.0   0.063       0  5166.3    0.12       0  5405.7    0.05       0
  5602.9   0.035       0
Bank Sta=4997.1,5003
Exp/Cntr=0.3,0.1

Type RM Length L Ch R = 1,2681,852,852,852
BEGIN DESCRIPTION:
Mapping XS 3617cbbd
END DESCRIPTION:
XS GIS Cut Line= 5
      2485295.21     13478173.42      2485069.12     13476772.85
      2485038.05     13476621.81      2484923.16     13476422.90
      2484473.59     13476599.99
#Sta/Elev= 30
  3581.3  235.61  3634.3  234.73  4129.2  228.65  4159.0  228.69  4229.5  226.06
  4309.2  224.17  4530.6  223.07  4683.6  221.78  4856.0  220.57  4947.2  210.77
  4977.6  210.46  4997.0  206.85  4997.5  206.35  5003.0  206.85  5028.4  210.49
  5089.7  214.71  5099.9  219.00  5161.2  219.37  5329.9  217.47  5345.7  218.53
  5351.4  220.30  5367.2  219.61  5373.0  221.03  5406.0  221.44  5424.9  220.45
  5430.4  218.46  5470.6  218.24  5577.4  218.69  5684.3  219.82  5867.1  221.92
#Mann=13,-1,0
  3581.3   0.045       0  3634.3   0.035       0  4129.2   0.045       0
  4159.0   0.063       0  4229.5   0.035       0  4530.6    0.05       0
  4683.6   0.035       0  4997.0   0.035       0  5003.0   0.035       0
  5161.2   0.063       0  5470.6    0.12       0  5577.4    0.07       0
  5684.3   0.035       0
Bank Sta=4997,5003
Exp/Cntr=0.3,0.1

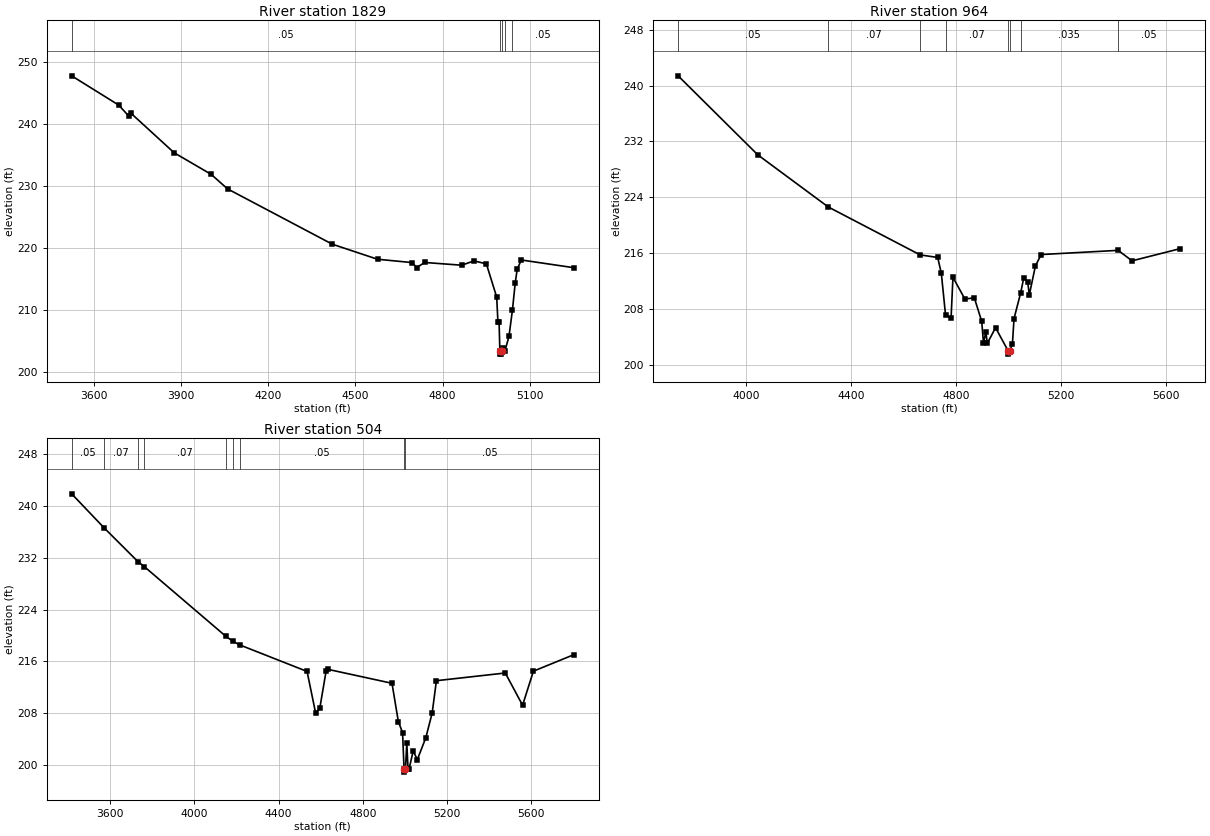
Type RM Length L Ch R = 1,1829,865,865,865
BEGIN DESCRIPTION:
Mapping XS 3a7c0e9e
END DESCRIPTION:
XS GIS Cut Line= 3
      2486332.46     13477206.21      2485283.86     13476178.44
      2485104.26     13475990.28
#Sta/Elev= 30
  3523.2  247.71  3684.9  243.01  3720.2  241.22  3727.4  241.69  3875.8  235.34
  4003.1  231.87  4059.7  229.53  4420.3  220.63  4575.9  218.21  4696.0  217.67
  4710.2  216.87  4738.5  217.69  4865.8  217.25  4908.2  217.95  4950.6  217.46
  4986.1  212.12  4990.4  208.05  4994.3  208.05  4997.0  203.45  4997.5  202.95
  5002.5  202.95  5003.0  203.45  5007.4  203.94  5014.6  203.48  5028.4  205.83
  5040.2  210.01  5049.8  214.38  5056.7  216.62  5070.9  218.09  5251.6  216.85
#Mann=5,-1,0
  3523.2    0.05       0  4997.0    0.05       0  5003.0    0.05       0
  5014.6    0.07       0  5040.2    0.05       0
Bank Sta=4997,5003
Exp/Cntr=0.3,0.1

Type RM Length L Ch R = 1,964,460,460,460
BEGIN DESCRIPTION:
Mapping XS 9a11defe
END DESCRIPTION:
XS GIS Cut Line= 4
      2486496.54     13476845.40      2486249.15     13476098.90
      2485745.68     13475799.42      2485218.13     13475920.50
#Sta/Elev= 30
  3740.0  241.41  4043.8  230.08  4312.0  222.62  4662.2  215.75  4729.1  215.38
  4743.0  213.09  4758.9  207.15  4780.0  206.65  4787.2  212.54  4832.6  209.43
  4868.7  209.59  4896.8  206.23  4903.6  203.09  4912.4  204.69  4918.3  203.08
  4949.5  205.32  4997.0  202.03  4997.5  201.53  5003.1  202.03  5013.7  202.93
  5019.9  206.62  5045.4  210.33  5056.5  212.37  5072.1  211.87  5078.1  210.01
  5101.4  214.16  5123.2  215.80  5416.7  216.40  5469.7  214.90  5653.5  216.65
#Mann=8,-1,0
  3740.0    0.05       0  4312.0    0.07       0  4662.2    0.05       0
  4758.9    0.07       0  4997.0    0.05       0  5003.1    0.07       0
  5045.4   0.035       0  5416.7    0.05       0
Bank Sta=4997,5003.1
Exp/Cntr=0.3,0.1

Type RM Length L Ch R = 1,504,0,0,0
BEGIN DESCRIPTION:
TRIB 6 TO PERDIDO CREEK 6.0
END DESCRIPTION:
XS GIS Cut Line= 4
      2486539.95     13476845.43      2486375.02     13475573.72
      2485845.51     13475517.30      2485288.23     13475653.73
#Sta/Elev= 30
  3415.7  241.88  3571.1  236.59  3730.7  231.42  3761.5  230.63  4149.3  219.87
  4182.5  219.11  4214.9  218.55  4535.4  214.45  4575.8  208.08  4595.9  208.75
  4626.2  214.55  4636.3  214.76  4939.4  212.62  4969.6  206.70  4989.7  205.01
  4996.6  199.40  4997.1  198.90  5003.4  199.40  5009.8  203.40  5015.6  199.41
  5020.6  199.40  5040.0  202.15  5060.1  200.85  5100.3  204.22  5130.5  208.04
  5150.6  213.02  5478.2  214.21  5560.5  209.23  5612.0  214.49  5804.3  217.04
#Mann=9,-1,0
  3415.7    0.05       0  3571.1    0.07       0  3730.7    0.12       0
  3761.5    0.07       0  4149.3    0.12       0  4182.5    0.07       0
  4214.9    0.05       0  4996.6    0.05       0  5003.4    0.05       0
Bank Sta=4996.6,5003.4
Exp/Cntr=0.3,0.1

Chan Stop Cuts=-1