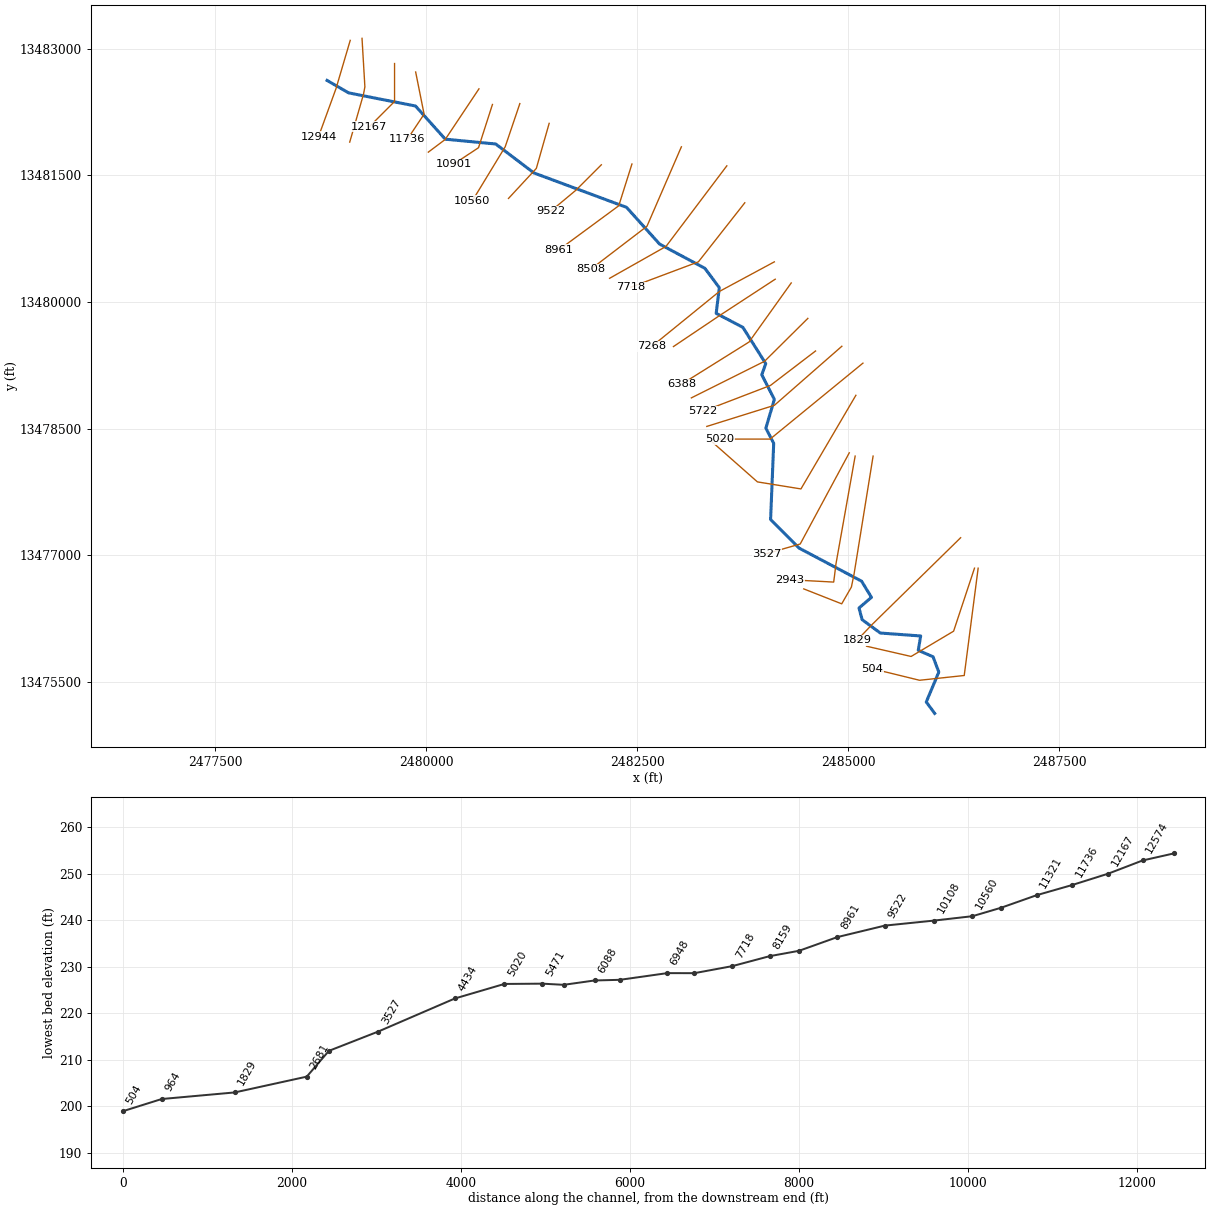
--- TRIB 6 TO PERDIDO CREEK.prj (project) ---

Proj Title=TRIB 6 TO PERDIDO CREEK Base Level Engineering
Current Plan=p01
Default Exp/Contr=0.3,0.1
English Units
Geom File=g01
Flow File=f01
Plan File=p01
Y Axis Title=Elevation
X Axis Title(PF)=Main Channel Distance
X Axis Title(XS)=Station
BEGIN DESCRIPTION:
TRIB 6 TO PERDIDO CREEK
END DESCRIPTION:
DSS Export Rating Curves= 0
DSS Export Rating Curve Sorted= 0
DSS Export Volume Flow Curves= 0
DXF OffsetX= 0
DXF OffsetY= 0
DXF ScaleX= 1
DXF ScaleY= 10

--- TRIB 6 TO PERDIDO CREEK.p01 (plan) ---

Plan Title=Multiple Run
Program Version=4.10
Short Identifier=Multiple
Geom File=g01
Flow File=f01
Subcritical Flow
K Sum by GR= 0
Std Step Tol= 0.01
Critical Tol= 0.01
Num of Std Step Trials= 20
Max Error Tol= 0.3
Flow Tol Ratio= 0.001
Split Flow NTrial= 30
Split Flow Tol= 0.02
Split Flow Ratio= 0.02
Log Output Level= 0
Friction Slope Method= 1
Unsteady Friction Slope Method= 2
Unsteady Bridges Friction Slope Method= 1
Parabolic Critical Depth
Global Vel Dist= 1 , 1 , 1
Global Log Level= 0
CheckData=True
Persistent XS Scale= 4400 , 5400 , 252 , 238 , 200 , 2
Encroach Param=-1 ,0,0, 0
BEGIN DESCRIPTION:
Multiple Run
END DESCRIPTION:
Computation Interval=1HOUR
Output Interval=1HOUR
Run HTab= 0
Run UNet= 0
Run PostProcess= 0
Run WQNet= 0
UNET Theta= 1
UNET Theta Warmup= 1
UNET ZTol= 0.02
UNET ZSATol= 0.05
UNET MxIter= 20
UNET MaxInSteps= 0
UNET DtIC= 0
UNET DtMin= 0
UNET MaxCRTS= 20
UNET WFStab= 2
UNET SFStab= 1
UNET WFX= 1
UNET SFX= 1
UNET DSS MLevel= 4
UNET DZMax Abort= 100
UNET Convert EG Bridges= 0
UNET Use Existing IB Tables=-1
UNET Froude Reduction=False
UNET Froude Limit= 1
UNET Froude Power= 10
UNET Time Slicing=0,0, 5
UNET Junction Losses=0
Instantaneous Interval=1HOUR
Write IC File= 0
Write IC File at Sim End=0
Echo Input=False
Echo Parameters=False
Echo Output=False
Write Detailed= 0
WQ AD Non Conservative
WQ ULTIMATE=-1
WQ Max Comp Step=1HOUR
WQ Output Interval=15MIN
WQ Output Selected Increments= 0
WQ Output face flow=0
WQ Output face velocity=0
WQ Output face area=0
WQ Output face dispersion=0
WQ Output cell volume=0
WQ Output cell surface area=0
WQ Output cell continuity=0
WQ Output cumulative cell continuity=0
WQ Output face conc=0
WQ Output face dconc_dx=0
WQ Output face courant=0
WQ Output face peclet=0
WQ Output face adv mass=0
WQ Output face disp mass=0
WQ Output cell mass=0
WQ Output cell source sink temp=0
WQ Output cell source sink nsm=0
WQ Output MaxMinRange=-1
WQ Daily Max Min Mean=-1
WQ Daily Range=0
WQ Daily Time=0
WQ Create Restart=0
WQ Fixed Restart=0
WQ System Summary=0
WQ Use Fixed Temperature=0
Sorting and Armoring Iterations= 10
XS Update Threshold= 0.02
Hydraulics Update Threshold= 0.02
Energy Slope Method= 1
Volume Change Method= 0
XS Weighting Method= 0
Number of US Weighted Cross Sections= 1
Number of DS Weighted Cross Sections= 1
Upstream XS Weight=0.25
Main XS Weight=0.5
Downstream XS Weight=0.25
Number of DS XS's Weighted with US Boundary= 1
Upstream Boundary Weight= 1
Weight of XSs Associated with US Boundary= 0
Number of US XS's Weighted with DS Boundary= 1
Downstream Boundary Weight= 0.5
Weight of XSs Associated with DS Boundary= 0.5
Sediment Output Level= 4
Mass or Volume Output= 0
Output Increment Type= 1
Profile and TS Output Increment= 10
XS Output Flag= 0
XS Output Increment= 10
Disregard all LS=0
Disregard all Conn=0
Disregard all Breaches=0
Disregard all Pumps=0

--- TRIB 6 TO PERDIDO CREEK.f01 (steady flow) ---

Flow Title=Multiple
Number of Profiles=7
Profile Names=10-year,25-year,50-year,1pct_min,100-year,1pct_plu,500-year
River Rch & RM= TRIB 6 TO PERDID,Reach-1,12944
     409     642     846     541    1080    2155    1739
River Rch & RM= TRIB 6 TO PERDID,Reach-1,11321
     655    1054    1412     916    1827    3646    3027
River Rch & RM= TRIB 6 TO PERDID,Reach-1,8508
    1018    1675    2278    1497    2987    5960    5084
River Rch & RM= TRIB 6 TO PERDID,Reach-1,5471
    1297    2161    2965    1964    3919    7820    6781
Boundary for River Rch & Prof#=TRIB 6 TO PERDID,Reach-1,1
Up Type=0
Dn Type=3
Dn Slope=0.005
Boundary for River Rch & Prof#=TRIB 6 TO PERDID,Reach-1,2
Up Type=0
Dn Type=3
Dn Slope=0.005
Boundary for River Rch & Prof#=TRIB 6 TO PERDID,Reach-1,3
Up Type=0
Dn Type=3
Dn Slope=0.005
Boundary for River Rch & Prof#=TRIB 6 TO PERDID,Reach-1,4
Up Type=0
Dn Type=3
Dn Slope=0.005
Boundary for River Rch & Prof#=TRIB 6 TO PERDID,Reach-1,5
Up Type=0
Dn Type=3
Dn Slope=0.005
Boundary for River Rch & Prof#=TRIB 6 TO PERDID,Reach-1,6
Up Type=0
Dn Type=3
Dn Slope=0.005
Boundary for River Rch & Prof#=TRIB 6 TO PERDID,Reach-1,7
Up Type=0
Dn Type=3
Dn Slope=0.005

--- TRIB 6 TO PERDIDO CREEK.g01 (geometry) ---

Geom Title=Existing Conditions
Program Version=4.10

River Reach=TRIB 6 TO PERDID,Reach-1
Reach XY= 30
        2478825.       13482625.      2479080.97     13482477.17
       2479873.5     13482321.39      2480226.25     13481928.46
       2480823.5     13481871.53      2481276.47     13481528.54
      2482373.42     13481121.18      2482765.32     13480685.78
      2483302.01     13480398.52      2483472.94     13480169.15
       2483436.1     13479864.89      2483752.28     13479698.89
      2484023.38     13479268.96       2483976.2     13479137.02
      2484125.36     13478845.15       2484024.6     13478504.87
      2484117.47     13478325.01       2484080.7     13477422.46
      2484418.67     13477083.04      2485158.36     13476691.71
      2485275.62     13476499.91      2485128.37     13476373.71
      2485164.94     13476235.63      2485380.85     13476077.06
      2485858.86     13476042.09      2485830.28     13475872.29
      2486005.57     13475795.64       2486073.9     13475614.45
        2485925.     13475259.59        2486025.       13475125.

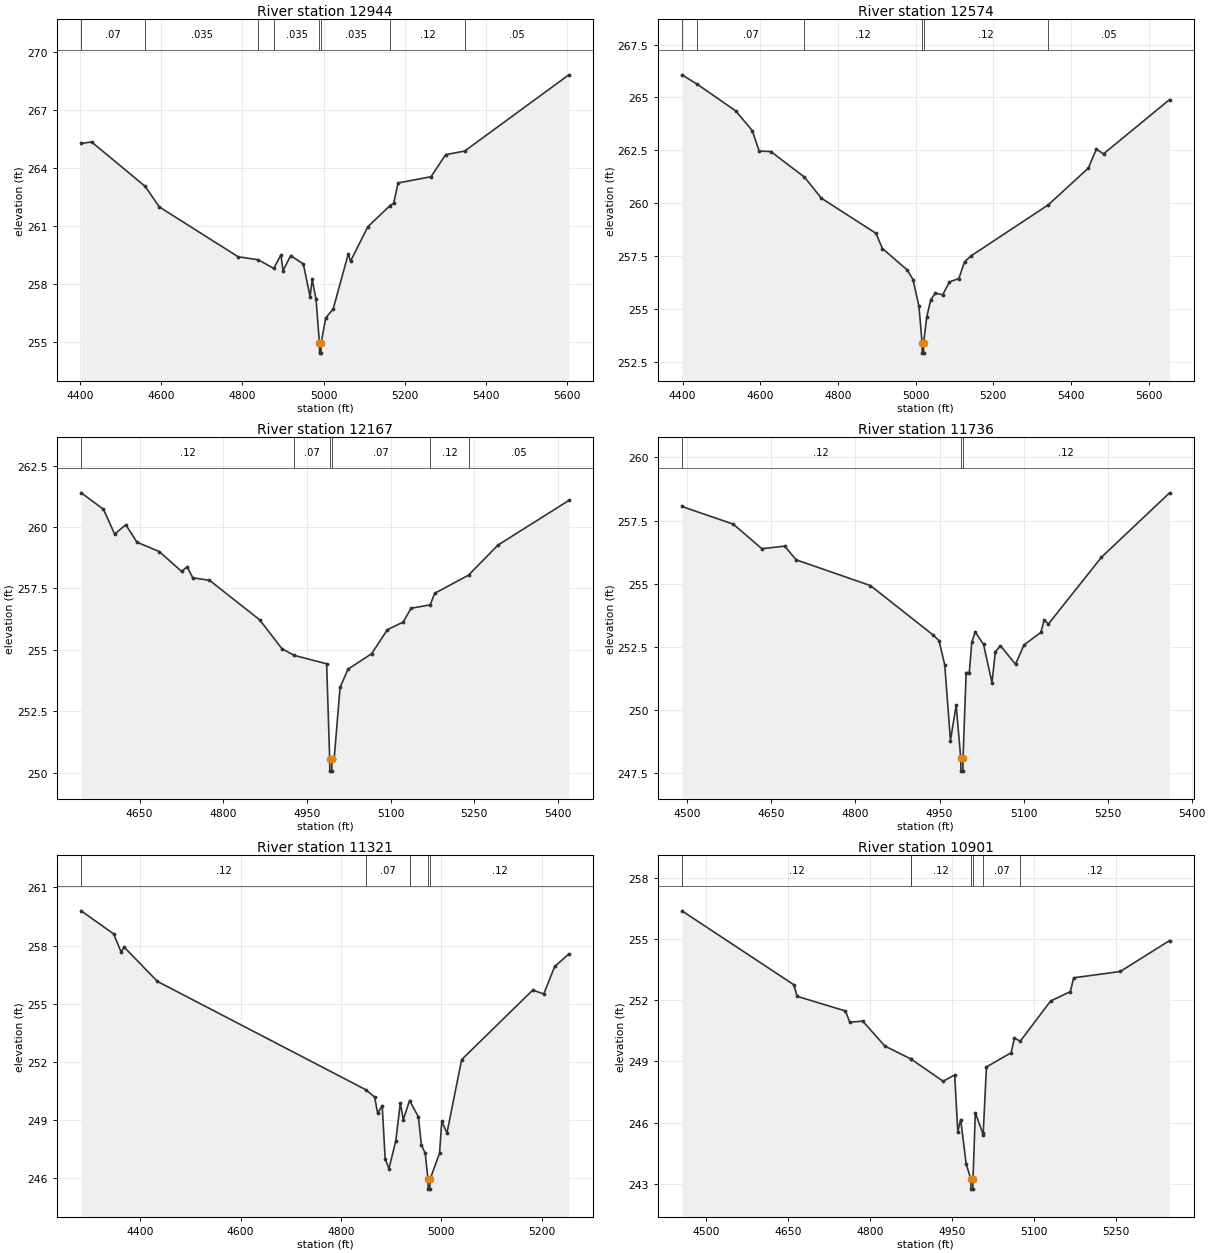
Type RM Length L Ch R = 1 ,12944   ,370,370,370
BEGIN DESCRIPTION:
TRIB 6 TO PERDIDO CREEK 24.0
END DESCRIPTION:
XS GIS Cut Line= 3
      2479099.76     13483099.52      2478930.88     13482527.12
      2478724.51     13481959.78
#Sta/Elev= 30
  4403.2  265.26  4428.8  265.34  4560.4  263.05  4595.6  261.98  4789.8   259.4
  4838.9  259.25  4877.3   258.8  4894.9   259.5  4900.1  258.68  4918.8  259.46
  4950.1  259.03  4966.7  257.34  4971.9  258.23  4981.4   257.2  4989.8  254.92
    4990  254.42  4993.5  254.42  4993.8  254.92  5005.1  256.24  5023.5   256.7
  5060.9  259.56  5066.2  259.17  5108.7  260.95  5163.5  262.05  5172.5  262.17
  5183.3  263.22  5264.4  263.54  5300.3  264.68  5347.4  264.87  5603.7  268.81
#Mann= 8 ,-1 , 0
  4403.2     .07       0  4560.4    .035       0  4838.9     .07       0
  4877.3    .035       0  4989.8    .035       0  4993.8    .035       0
  5163.5     .12       0  5347.4     .05       0
Bank Sta=4989.8,4993.8
XS Rating Curve= 0 ,0
Exp/Cntr=0.3,0.1

Type RM Length L Ch R = 1 ,12574   ,407,407,407
BEGIN DESCRIPTION:
Mapping XS 32352395
END DESCRIPTION:
XS GIS Cut Line= 4
      2479239.49     13483123.49      2479273.43     13482548.51
      2479257.46     13482462.67      2479093.76     13481893.74
#Sta/Elev= 30
  4398.5  266.07  4438.4  265.62  4537.2  264.36  4579.6  263.43  4597.3  262.46
  4627.4  262.44  4713.9  261.23  4757.6  260.23  4897.9  258.57  4914.6  257.85
  4978.8  256.83  4993.3  256.38  5008.6  255.12  5016.7   253.4    5017   252.9
  5020.5   252.9  5020.7   253.4  5028.9  254.63  5039.1  255.43  5051.1  255.74
  5069.8  255.66  5087.1  256.27  5111.4  256.43    5126  257.22  5142.6   257.5
    5341  259.91  5444.4  261.65  5465.2  262.55  5483.7  262.33  5653.8   264.9
#Mann= 6 ,-1 , 0
  4398.5     .12       0  4438.4     .07       0  4713.9     .12       0
  5016.7     .05       0  5020.7     .12       0    5341     .05       0
Bank Sta=5016.7,5020.7
XS Rating Curve= 0 ,0
Exp/Cntr=0.3,0.1

Type RM Length L Ch R = 1 ,12167   ,431,431,431
BEGIN DESCRIPTION:
TRIB 6 TO PERDIDO CREEK 23.0
END DESCRIPTION:
XS GIS Cut Line= 3
        2479625.     13482824.98        2479625.       13482375.
      2479325.03     13482075.03
#Sta/Elev= 30
  4545.2  261.39  4585.2  260.72  4605.2  259.71  4625.2  260.09  4645.2  259.38
  4685.2     259  4725.2  258.19  4735.2  258.38  4745.2  257.93  4775.2  257.83
  4865.2  256.22  4905.2  255.04  4927.5  254.77  4985.2  254.43  4990.7  250.56
  4990.9  250.06  4994.4  250.06  4994.7  250.56  4998.7  250.56  5009.3  253.47
  5023.5  254.21  5065.9  254.84  5094.2  255.82  5122.5  256.13  5136.6  256.69
  5170.8  256.83    5179   257.3  5239.7  258.04  5292.2  259.26  5419.4  261.08
#Mann= 6 ,-1 , 0
  4545.2     .12       0  4927.5     .07       0  4990.7     .05       0
  4994.7     .07       0  5170.8     .12       0  5239.7     .05       0
Bank Sta=4990.7,4994.7
XS Rating Curve= 0 ,0
Exp/Cntr=0.3,0.1

Type RM Length L Ch R = 1 ,11736   ,415,415,415
BEGIN DESCRIPTION:
TRIB 6 TO PERDIDO CREEK 22.0
END DESCRIPTION:
XS GIS Cut Line= 3
      2479875.01     13482724.96        2479975.       13482225.
      2479775.01     13481925.02
#Sta/Elev= 30
  4490.2  258.06  4581.9  257.36  4632.9  256.39  4673.7  256.49  4694.1  255.95
  4826.7  254.93  4938.9  252.97  4949.1  252.75  4959.3  251.79  4969.5   248.8
  4979.7   250.2  4987.9  248.09  4988.1  247.59  4991.6  247.59  4991.9  248.09
  4997.5  251.49  5003.1  251.49  5007.6  252.69  5013.6   253.1  5028.6   252.6
  5043.6  251.09  5049.6  252.31  5058.7  252.55  5085.7  251.82  5100.7  252.58
  5130.8  253.08  5136.8  253.57  5144.3  253.41  5238.9  256.05  5360.6   258.6
#Mann= 3 ,-1 , 0
  4490.2     .12       0  4987.9     .05       0  4991.9     .12       0
Bank Sta=4987.9,4991.9
XS Rating Curve= 0 ,0
Exp/Cntr=0.3,0.1

Type RM Length L Ch R = 1 ,11321   ,420,420,420
BEGIN DESCRIPTION:
TRIB 6 TO PERDIDO CREEK 21.0
END DESCRIPTION:
XS GIS Cut Line= 3
        2480625.       13482525.        2480225.       13481925.
      2480025.01     13481775.01
#Sta/Elev= 30
  4282.7  259.79  4347.3   258.6  4362.3  257.66  4368.3  257.92  4434.4  256.15
  4849.4  250.56  4867.1  250.18  4873.1  249.34  4882.1  249.74  4888.1  246.98
  4895.6  246.49  4909.2  247.92  4918.2  249.88  4924.2  249.01  4936.5     250
  4954.2  249.16  4960.2  247.71  4967.8  247.28  4973.3  245.93  4973.5  245.43
    4977  245.43  4977.3  245.93  4996.3  247.28  5000.8  248.93  5011.1  248.33
  5040.3  252.11  5181.9   255.7  5203.8   255.5  5225.7  256.92  5253.8  257.56
#Mann= 5 ,-1 , 0
  4282.7     .12       0  4849.4     .07       0  4936.5     .12       0
  4973.3     .05       0  4977.3     .12       0
Bank Sta=4973.3,4977.3
XS Rating Curve= 0 ,0
Exp/Cntr=0.3,0.1

Type RM Length L Ch R = 1 ,10901   ,341,341,341
BEGIN DESCRIPTION:
Mapping XS f6644389
END DESCRIPTION:
XS GIS Cut Line= 3
      2480784.85     13482339.84      2480619.91     13481827.66
      2480324.78     13481632.34
#Sta/Elev= 30
  4455.7   256.4  4660.4  252.77  4666.5   252.2  4754.9  251.48  4762.7  250.93
  4786.5  250.98  4826.8  249.76  4874.7  249.12  4875.2  249.11  4933.5  248.03
  4954.6  248.34  4960.3  245.56  4965.6  246.15  4975.6  243.97  4984.1  243.23
  4984.3  242.73  4987.8  242.73  4988.1  243.23  4992.4  246.48  5005.9  245.48
  5006.7  245.41  5012.7  248.73  5057.8  249.43  5063.8  250.14  5074.7     250
    5130  251.97  5166.2  252.43  5172.2  253.11  5257.5  253.42  5347.7  254.94
#Mann= 7 ,-1 , 0
  4455.7     .12       0  4874.7     .07       0  4875.2     .12       0
  4984.1     .05       0  4988.1     .12       0  5005.9     .07       0
  5074.7     .12       0
Bank Sta=4984.1,4988.1
XS Rating Curve= 0 ,0
Exp/Cntr=0.3,0.1

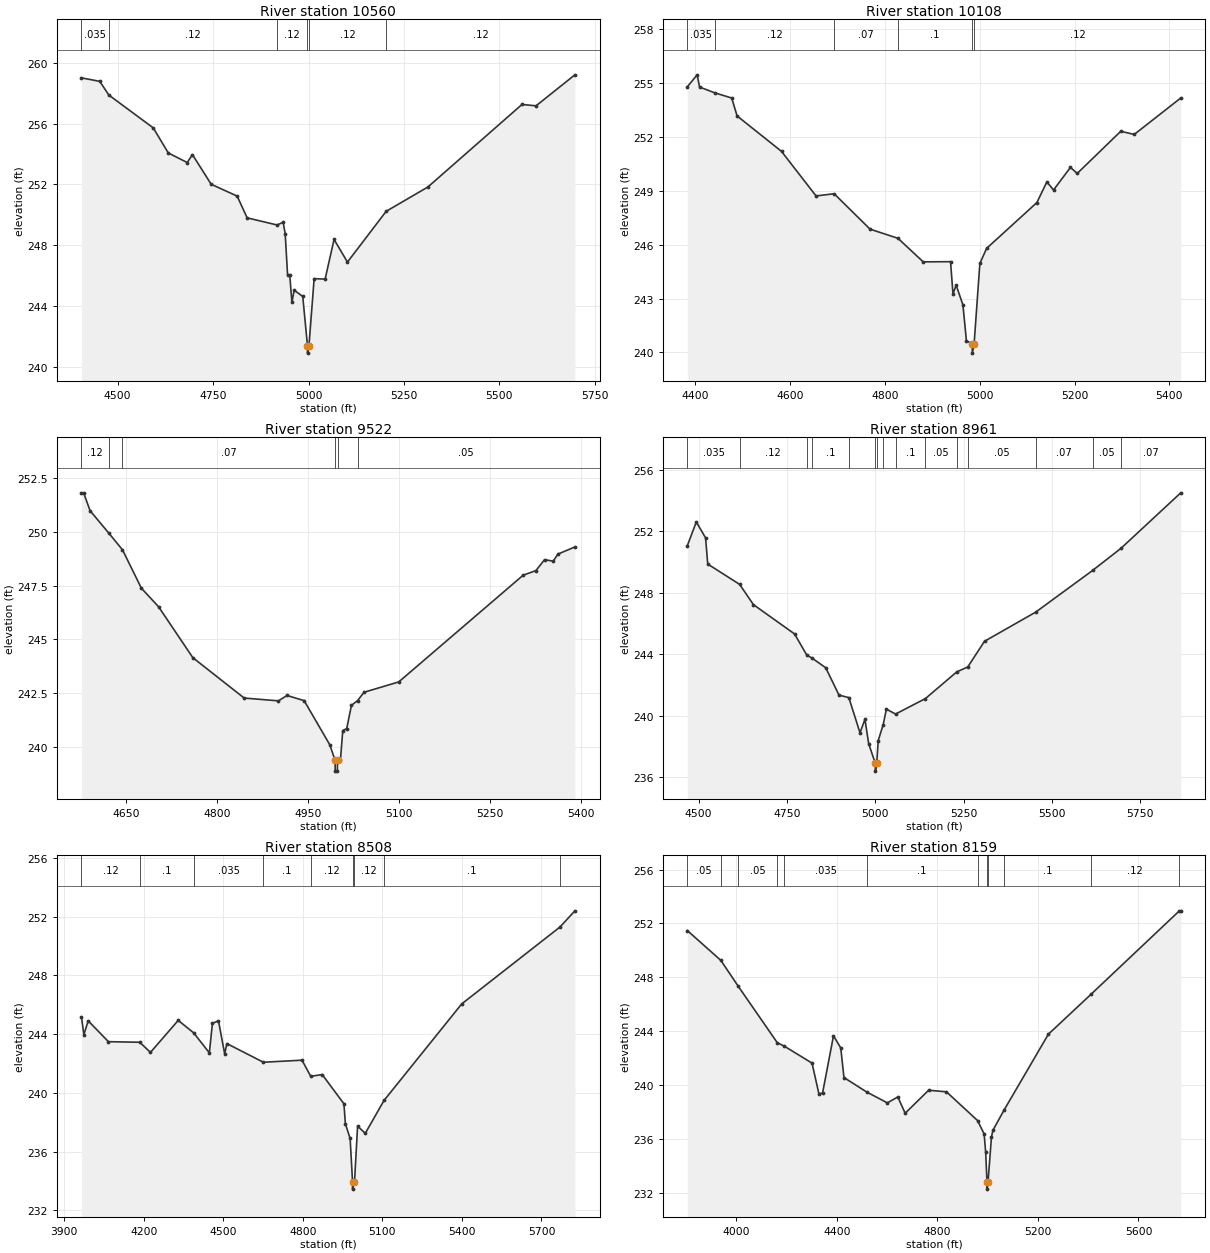
Type RM Length L Ch R = 1 ,10560   ,452,452,452
BEGIN DESCRIPTION:
Mapping XS f43fbdcd
END DESCRIPTION:
XS GIS Cut Line= 3
      2481109.54     13482350.45      2480935.93      13481838.3
       2480545.3     13481195.92
#Sta/Elev= 30
  4405.2  259.01  4453.2  258.78  4476.9  257.88  4593.2  255.72  4632.7  254.07
  4682.2  253.44    4696  253.96    4745  252.01  4813.1  251.23  4839.2   249.8
  4917.8  249.33  4933.5  249.51  4938.9  248.76  4945.1  246.05  4950.8  246.05
  4956.5  244.24  4962.4  245.04  4984.9  244.63  4997.2   241.4  4997.4   240.9
  5001.2   241.4  5014.7   245.8  5043.5  245.77  5066.9  248.38    5102  246.89
  5203.4  250.23  5312.7  251.83  5559.2  257.26    5596  257.17  5697.8  259.21
#Mann= 6 ,-1 , 0
  4405.2    .035       0  4476.9     .12       0  4917.8     .12       0
  4997.2     .05       0  5001.2     .12       0  5203.4     .12       0
Bank Sta=4997.2,5001.2
XS Rating Curve= 0 ,0
Exp/Cntr=0.3,0.1

Type RM Length L Ch R = 1 ,10108   ,586,586,586
BEGIN DESCRIPTION:
Mapping XS a4a5f412
END DESCRIPTION:
XS GIS Cut Line= 3
      2481456.75     13482116.04      2481304.85     13481582.22
      2480974.97     13481226.29
#Sta/Elev= 30
  4383.6  254.78  4404.3  255.45  4409.5  254.77  4442.3  254.44  4477.2  254.16
  4488.6  253.16  4582.2  251.19    4655  248.71  4693.2  248.83  4768.9  246.86
  4827.8  246.35  4880.9  245.04  4938.6  245.05  4943.7  243.26  4950.5  243.74
  4964.7  242.64    4972  240.66  4984.2  240.46  4984.5  239.96  4988.2  240.46
  5000.4  244.95  5014.6  245.79  5120.6  248.34  5141.6  249.49  5155.7  249.04
  5191.4   250.3  5205.6  249.96  5297.5  252.31  5325.8  252.13  5423.9  254.16
#Mann= 6 ,-1 , 0
  4383.6    .035       0  4442.3     .12       0  4693.2     .07       0
  4827.8      .1       0  4984.2     .05       0  4988.2     .12       0
Bank Sta=4984.2,4988.2
XS Rating Curve= 0 ,0
Exp/Cntr=0.3,0.1

Type RM Length L Ch R = 1 ,9522    ,561,561,561
BEGIN DESCRIPTION:
TRIB 6 TO PERDIDO CREEK 17.0
END DESCRIPTION:
XS GIS Cut Line= 3
      2482075.02     13481625.02        2481775.       13481325.
      2481475.01     13481075.01
#Sta/Elev= 30
  4575.7  251.82  4579.3  251.82  4589.9  250.99  4621.3  249.93  4643.4  249.17
  4674.7  247.38    4703  246.52  4759.6  244.15  4844.4  242.27    4901  242.14
  4915.1  242.39  4943.4  242.15  4985.9  240.09  4994.5  239.37  4994.7  238.87
  4998.2  238.87  4998.5  239.37  5003.3  239.37  5007.2  240.76  5013.7  240.85
  5021.5  241.93  5031.6  242.15  5042.3  242.54  5099.6  243.02  5305.2  247.99
  5326.1   248.2  5340.4  248.71  5354.7  248.64  5362.5  248.97  5390.5   249.3
#Mann= 6 ,-1 , 0
  4575.7     .12       0  4621.3    .035       0  4643.4     .07       0
  4994.5     .05       0  4998.5     .07       0  5031.6     .05       0
Bank Sta=4994.5,4998.5
XS Rating Curve= 0 ,0
Exp/Cntr=0.3,0.1

Type RM Length L Ch R = 1 ,8961    ,453,453,453
BEGIN DESCRIPTION:
Mapping XS 17b369ec
END DESCRIPTION:
XS GIS Cut Line= 3
      2482437.68     13481634.33      2482281.42     13481139.51
      2481574.85     13480619.34
#Sta/Elev= 30
  4468.2  251.05  4493.7   252.6  4519.9  251.56    4526  249.86  4616.2  248.54
  4655.4  247.22  4771.6  245.32  4806.4  243.94  4820.9  243.75  4859.9  243.12
  4897.5  241.34  4925.3  241.18  4956.9  238.89  4970.9  239.77  4981.4  238.19
  5000.2   236.9  5000.5   236.4  5004.2   236.9  5008.4  238.38  5022.6  239.43
  5031.5  240.43  5057.6  240.11  5142.2  241.12  5230.6  242.85  5261.8  243.17
  5309.2  244.84  5454.4  246.74  5615.4  249.45  5695.2  250.88  5864.5  254.49
#Mann= 15 ,-1 , 0
  4468.2    .035       0  4616.2     .12       0  4806.4     .07       0
  4820.9      .1       0  4925.3     .12       0  5000.2     .05       0
  5004.2     .12       0  5022.6     .07       0  5057.6      .1       0
  5142.2     .05       0  5230.6     .07       0  5261.8     .05       0
  5454.4     .07       0  5615.4     .05       0  5695.2     .07       0
Bank Sta=5000.2,5004.2
XS Rating Curve= 0 ,0
Exp/Cntr=0.3,0.1

Type RM Length L Ch R = 1 ,8508    ,349,349,349
BEGIN DESCRIPTION:
Mapping XS 35ed39ef
END DESCRIPTION:
XS GIS Cut Line= 3
      2483023.61     13481838.31      2482615.62     13480896.46
      2481952.43     13480389.31
#Sta/Elev= 30
  3964.9  245.17    3974  243.97  3990.3  244.91  4066.6  243.49  4184.8  243.45
  4225.1  242.76  4329.9  244.94  4388.2  244.09  4447.3  242.73  4458.9  244.73
  4481.7  244.92  4505.1  242.66  4513.4  243.36  4651.2  242.09  4796.8  242.23
  4829.8  241.13    4873  241.25    4955  239.26  4960.4   237.9  4978.4   236.9
  4987.4  233.95  4987.6  233.45  4991.4  233.95  4994.9  233.95  5006.5  237.74
  5035.5  237.25  5106.3  239.49  5399.1  246.06  5770.1   251.3  5826.2   252.4
#Mann= 9 ,-1 , 0
  3964.9     .12       0  4184.8      .1       0  4388.2    .035       0
  4651.2      .1       0  4829.8     .12       0  4987.4     .05       0
  4991.4     .12       0  5106.3      .1       0  5770.1     .07       0
Bank Sta=4987.4,4991.4
XS Rating Curve= 0 ,0
Exp/Cntr=0.3,0.1

Type RM Length L Ch R = 1 ,8159    ,441,441,441
BEGIN DESCRIPTION:
Mapping XS b2719491
END DESCRIPTION:
XS GIS Cut Line= 3
      2483561.78     13481612.58      2482841.31     13480657.74
      2482172.95     13480280.16
#Sta/Elev= 30
  3804.5  251.48  3938.1  249.26  4006.2  247.37  4162.4  243.16  4191.2  242.89
  4300.9  241.64    4328  239.38  4342.6   239.4  4386.3  243.67  4415.3  242.76
  4427.9  240.57  4518.2   239.5  4600.7  238.69  4642.3  239.13  4671.5  237.92
  4765.1  239.63  4835.9  239.51  4959.5  237.38  4985.8  236.39    4992  235.02
  4997.2  232.79  4997.5  232.29  5001.2  232.79    5015  236.15  5020.8  236.66
  5065.9  238.18  5241.7  243.79  5410.9  246.74  5762.3  252.93  5768.3  252.94
#Mann= 12 ,-1 , 0
  3804.5     .05       0  3938.1     .07       0  4006.2     .05       0
  4162.4     .07       0  4191.2    .035       0  4518.2      .1       0
  4959.5     .12       0  4997.2     .05       0  5001.2     .12       0
  5065.9      .1       0  5410.9     .12       0  5762.3     .07       0
Bank Sta=4997.2,5001.2
XS Rating Curve= 0 ,0
Exp/Cntr=0.3,0.1

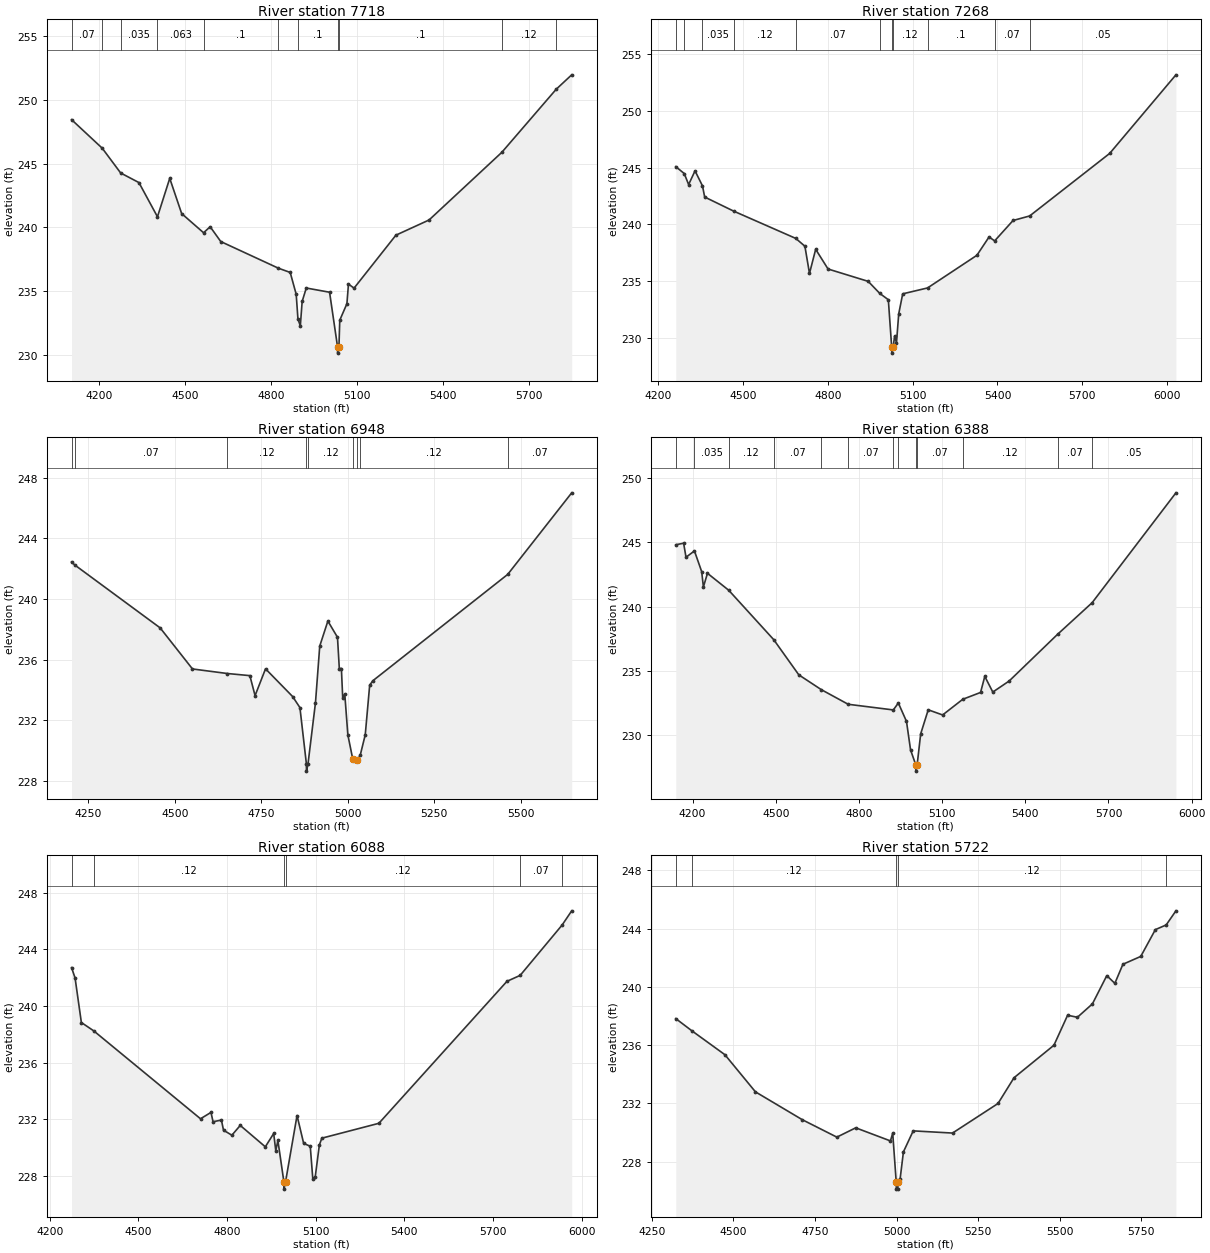
Type RM Length L Ch R = 1 ,7718    ,450,450,450
BEGIN DESCRIPTION:
TRIB 6 TO PERDIDO CREEK 13.0
END DESCRIPTION:
XS GIS Cut Line= 3
      2483774.99     13481174.99        2483225.       13480475.
      2482425.01       13480175.
#Sta/Elev= 30
  4103.6  248.44  4210.7   246.2    4275  244.26  4338.6  243.51  4403.3  240.83
  4446.1  243.84  4487.7  241.08  4564.1  239.58  4587.1  240.05  4624.1  238.89
  4825.4   236.8  4866.3  236.47  4887.2  234.76  4893.3  232.82  4901.6  232.28
    4908   234.2  4922.4  235.25  5003.6  234.92  5031.4  230.65  5031.8  230.15
  5036.3  230.65  5039.2  232.73  5064.1  234.02  5069.5  235.56    5089  235.24
    5235  239.39  5350.7  240.58  5604.5  245.88  5794.1  250.82  5848.2  251.95
#Mann= 11 ,-1 , 0
  4103.6     .07       0  4210.7     .12       0    4275    .035       0
  4403.3    .063       0  4564.1      .1       0  4825.4     .12       0
  4893.3      .1       0  5031.4     .05       0  5036.3      .1       0
  5604.5     .12       0  5794.1     .07       0
Bank Sta=5031.4,5036.3
XS Rating Curve= 0 ,0
Exp/Cntr=0.3,0.1

Type RM Length L Ch R = 1 ,7268    ,320,320,320
BEGIN DESCRIPTION:
TRIB 6 TO PERDIDO CREEK 12.0
END DESCRIPTION:
XS GIS Cut Line= 3
      2484124.96     13480474.98        2483475.       13480125.
      2482674.98     13479474.98
#Sta/Elev= 30
  4262.3  245.08  4292.3  244.47  4307.7   243.5  4330.4  244.71  4356.8  243.38
  4364.5   242.4  4466.8  241.16  4686.7  238.75    4719  238.06  4735.2  235.66
  4757.1  237.79  4800.9  236.05  4942.9  234.96  4983.7   233.9  5014.1  233.34
    5026  229.13  5026.4  228.63  5030.9  229.13  5036.4  230.14  5042.9  229.54
  5050.8  232.09  5064.9  233.86  5152.8  234.38  5327.3  237.26  5370.4  238.88
  5390.1  238.53  5455.2  240.33  5513.9  240.73  5797.1  246.25  6031.3  253.18
#Mann= 11 ,-1 , 0
  4262.3    .035       0  4292.3    .063       0  4356.8    .035       0
  4466.8     .12       0  4686.7     .07       0  4983.7     .12       0
    5026     .05       0  5030.9     .12       0  5152.8      .1       0
  5390.1     .07       0  5513.9     .05       0
Bank Sta=5026,5030.9
XS Rating Curve= 0 ,0
Exp/Cntr=0.3,0.1

Type RM Length L Ch R = 1 ,6948    ,560,560,560
BEGIN DESCRIPTION:
Mapping XS 4cbf0c69
END DESCRIPTION:
XS GIS Cut Line= 3
       2484135.5     13480269.47       2483484.5     13479844.15
      2482929.47     13479471.24
#Sta/Elev= 30
    4201  242.44  4210.3  242.24  4457.2  238.09  4550.7  235.38  4651.5  235.08
  4716.6  234.94  4731.7  233.62  4761.9  235.39  4840.3  233.56  4861.4  232.83
    4880  229.14  4880.4  228.64  4884.9  229.14  4906.4  233.16  4918.7  236.89
  4942.2  238.54    4970  237.47  4975.3  235.41  4981.3  235.41  4985.1  233.49
  4991.1  233.72    5000  231.03  5014.2  229.43  5027.1  229.35    5036  229.71
  5050.3  231.04  5063.1  234.31  5072.1   234.6  5462.3  241.62  5647.3     247
#Mann= 9 ,-1 , 0
    4201    .035       0  4210.3     .07       0  4651.5     .12       0
    4880     .07       0  4884.9     .12       0  5014.2     .05       0
  5027.1     .07       0    5036     .12       0  5462.3     .07       0
Bank Sta=5014.2,5027.1
XS Rating Curve= 0 ,0
Exp/Cntr=0.3,0.1

Type RM Length L Ch R = 1 ,6388    ,300,300,300
BEGIN DESCRIPTION:
TRIB 6 TO PERDIDO CREEK 10.0
END DESCRIPTION:
XS GIS Cut Line= 3
      2484325.01     13480225.02        2483825.       13479525.
      2483024.96     13479024.97
#Sta/Elev= 30
  4139.7  244.81    4168  244.93  4176.6  243.84    4207  244.33  4233.1  242.72
  4239.3  241.53    4254  242.59  4330.7  241.27  4492.8  237.43  4583.4  234.69
  4664.4  233.54  4761.5   232.4  4924.2  231.96  4942.3   232.5  4971.7  231.07
  4986.4  228.85    5005   227.7  5005.4   227.2  5010.2   227.7  5022.9   230.1
  5050.1  231.97    5102  231.57  5174.7  232.79  5238.8  233.32  5254.1  234.57
    5283  233.35  5341.9  234.21  5516.4  237.84  5641.1   240.3  5943.4  248.85
#Mann= 13 ,-1 , 0
  4139.7    .063       0    4207    .035       0  4330.7     .12       0
  4492.8     .07       0  4664.4     .12       0  4761.5     .07       0
  4924.2     .12       0  4942.3     .07       0    5005     .05       0
  5010.2     .07       0  5174.7     .12       0  5516.4     .07       0
  5641.1     .05       0
Bank Sta=5005,5010.2
XS Rating Curve= 0 ,0
Exp/Cntr=0.3,0.1

Type RM Length L Ch R = 1 ,6088    ,366,366,366
BEGIN DESCRIPTION:
Mapping XS 98f1b9cf
END DESCRIPTION:
XS GIS Cut Line= 3
      2484521.81     13479805.08      2484009.67     13479297.27
      2483141.64     13478863.26
#Sta/Elev= 30
  4274.1  242.71    4286  241.98  4307.3  238.83  4349.2  238.24  4710.3  232.03
  4745.7  232.48  4752.7  231.82    4781  231.94  4788.1  231.22  4816.4  230.87
  4844.7  231.56  4929.5  230.05  4957.8  230.99  4964.9  229.77    4972   230.5
  4992.4  227.56  4992.8  227.06  4997.8  227.56  5036.8  232.26  5059.2  230.29
  5081.5  230.09    5090  227.81  5098.3  227.92  5112.3  230.18  5120.7  230.66
  5313.6  231.71  5746.8  241.74  5791.5  242.16  5933.5  245.72  5965.8  246.72
#Mann= 6 ,-1 , 0
  4274.1    .063       0  4349.2     .12       0  4992.4     .05       0
  4997.8     .12       0  5791.5     .07       0  5933.5     .05       0
Bank Sta=4992.4,4997.8
XS Rating Curve= 0 ,0
Exp/Cntr=0.3,0.1

Type RM Length L Ch R = 1 ,5722    ,251,251,251
BEGIN DESCRIPTION:
Mapping XS 51bc92ce
END DESCRIPTION:
XS GIS Cut Line= 3
      2484612.99     13479418.82      2484079.12     13479010.82
      2483276.14     13478702.65
#Sta/Elev= 30
  4323.8  237.83    4372  237.01  4474.3  235.35  4567.8   232.8  4711.1  230.89
  4817.2  229.69    4875  230.33  4981.3  229.43  4988.3  229.96    4999  226.62
  4999.5  226.12    5004  226.12  5004.4  226.62  5010.8  226.79  5021.1  228.68
  5051.1  230.12  5171.5  229.97  5310.8     232  5359.9  233.77  5482.1     236
    5524  238.06    5554  237.92    5600  238.84    5644  240.78  5668.7  240.25
  5693.4  241.56  5748.1   242.1  5792.8  243.94  5825.9  244.26  5855.8  245.23
#Mann= 5 ,-1 , 0
  4323.8    .035       0    4372     .12       0    4999     .05       0
  5004.4     .12       0  5825.9     .05       0
Bank Sta=4999,5004.4
XS Rating Curve= 0 ,0
Exp/Cntr=0.3,0.1

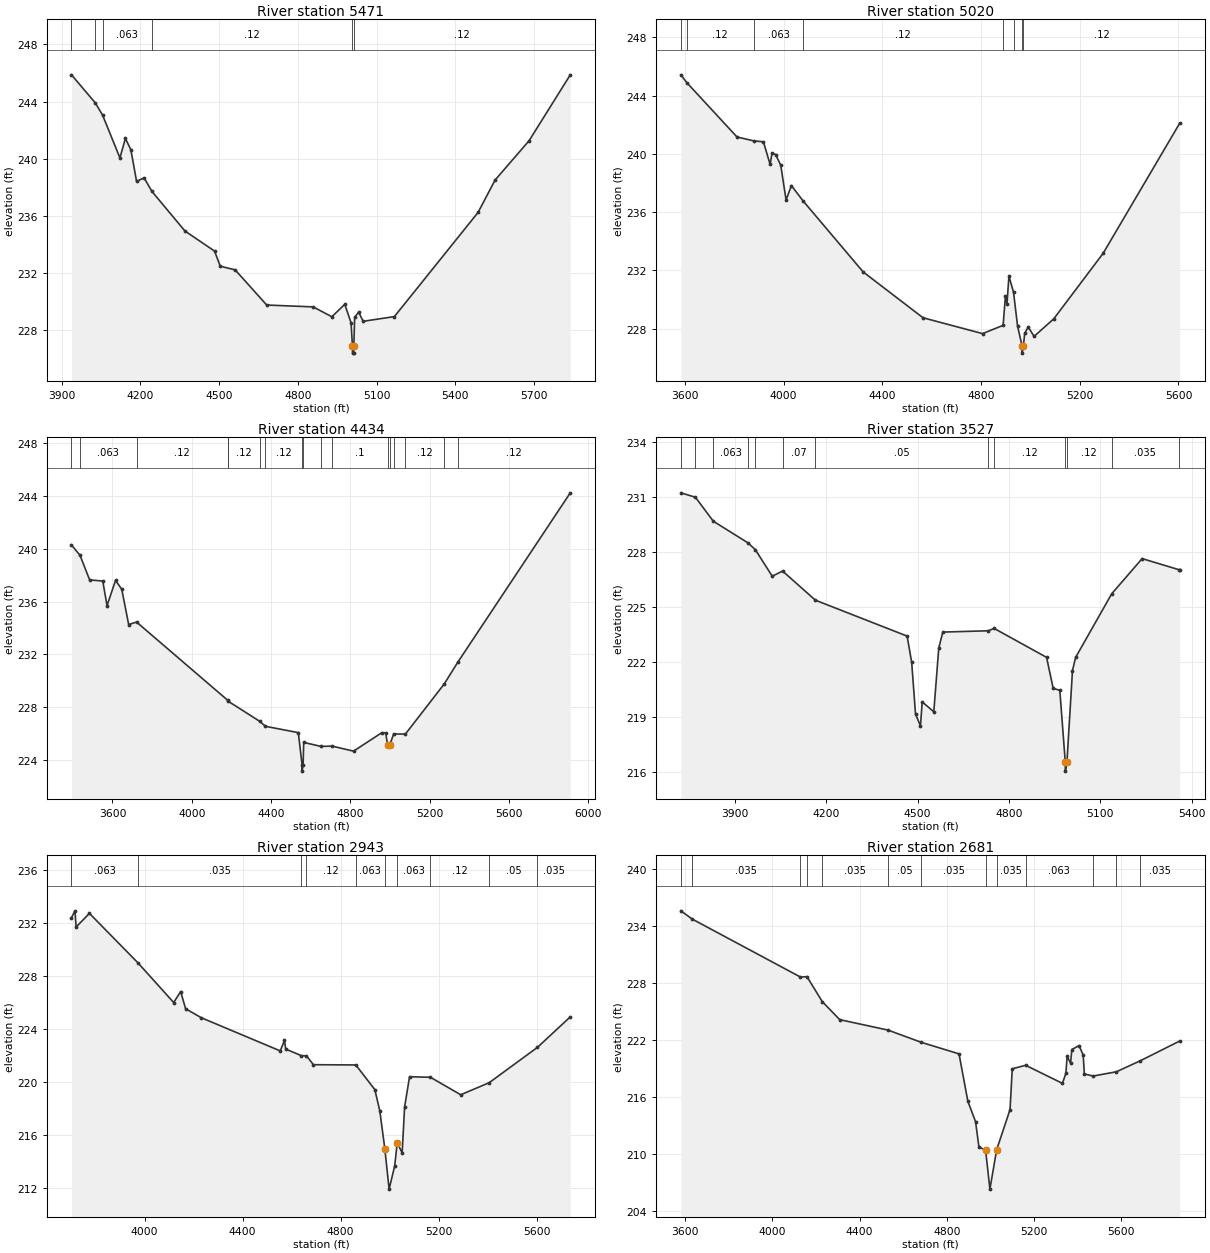
Type RM Length L Ch R = 1 ,5471    ,451,451,451
BEGIN DESCRIPTION:
TRIB 6 TO PERDIDO CREEK 8.0
END DESCRIPTION:
XS GIS Cut Line= 3
      2484925.02     13479475.01        2484125.       13478775.
      2483324.99       13478525.
#Sta/Elev= 30
  3937.1  245.87  4027.6  243.91  4055.6  243.05  4121.7  240.05  4142.6  241.41
  4163.5  240.62  4185.3   238.4  4213.8  238.65  4243.8   237.7  4369.4  234.93
  4482.4  233.52  4504.2  232.46  4561.2   232.2  4681.2  229.74  4858.2  229.61
  4929.4  228.92  4978.8  229.79  5002.8  228.49  5007.9  226.87  5008.3  226.37
  5012.9  226.37  5013.3  226.87  5016.4  228.88  5031.6  229.24  5048.9   228.6
  5167.8  228.93  5486.8  236.23  5551.7   238.5  5681.1  241.25  5838.3  245.87
#Mann= 6 ,-1 , 0
  3937.1     .12       0  4027.6    .035       0  4055.6    .063       0
  4243.8     .12       0  5007.9     .05       0  5013.3     .12       0
Bank Sta=5007.9,5013.3
XS Rating Curve= 0 ,0
Exp/Cntr=0.3,0.1

Type RM Length L Ch R = 1 ,5020    ,586,586,586
BEGIN DESCRIPTION:
TRIB 6 TO PERDIDO CREEK 7.0
END DESCRIPTION:
XS GIS Cut Line= 3
      2485174.96     13479274.97        2484075.       13478375.
      2483475.02       13478375.
#Sta/Elev= 30
  3583.8  245.43    3608  244.89  3811.3  241.16  3879.5  240.89  3918.3  240.83
  3945.5  239.27  3953.4  240.07  3967.8  239.95  3988.6  239.22  4010.1  236.83
  4031.7  237.82  4079.4  236.76  4322.4  231.89    4565  228.74  4806.2  227.65
  4889.6  228.22  4898.8  230.21  4905.2  229.69  4913.1   231.6  4931.7   230.5
  4948.3  228.15  4966.4  226.81  4966.8  226.31  4971.9  226.81    4977  227.68
  4991.4   228.1    5015  227.46    5095  228.67    5295  233.17    5605   242.1
#Mann= 8 ,-1 , 0
  3583.8    .035       0    3608     .12       0  3879.5    .063       0
  4079.4     .12       0  4889.6      .1       0  4931.7     .12       0
  4966.4     .05       0  4971.9     .12       0
Bank Sta=4966.4,4971.9
XS Rating Curve= 0 ,0
Exp/Cntr=0.3,0.1

Type RM Length L Ch R = 1 ,4434    ,907,907,907
BEGIN DESCRIPTION:
Mapping XS 0013da0b
END DESCRIPTION:
XS GIS Cut Line= 4
      2485091.23     13478893.93      2484440.27     13477784.48
      2483924.65     13477867.81      2483393.41     13478336.55
#Sta/Elev= 30
  3393.1  240.28  3436.4  239.49  3484.6  237.64    3551  237.55  3572.5  235.69
  3615.4   237.6  3646.8  236.93  3681.7  234.26  3721.6  234.45  4180.4  228.55
  4185.3  228.45  4343.6  226.94  4371.6  226.57  4537.8  226.09  4556.5  223.68
  4556.9  223.18    4562  223.68    4565  225.35  4651.8  225.05  4708.6  225.07
  4816.4  224.69  4958.3  226.08  4978.5  226.08  4988.7  225.13  4998.8  225.16
    5019  225.99    5078  225.98    5274  229.77  5342.4  231.41  5910.2  244.22
#Mann= 17 ,-1 , 0
  3393.1    .035       0  3436.4    .063       0  3721.6     .12       0
  4180.4     .07       0  4185.3     .12       0  4343.6     .07       0
  4371.6     .12       0  4556.5     .07       0    4562     .12       0
  4651.8     .07       0  4708.6      .1       0  4988.7     .05       0
  4998.8     .07       0    5019      .1       0    5078     .12       0
    5274     .07       0  5342.4     .12       0
Bank Sta=4988.7,4998.8
XS Rating Curve= 0 ,0
Exp/Cntr=0.3,0.1

Type RM Length L Ch R = 1 ,3527    ,584,584,584
BEGIN DESCRIPTION:
Mapping XS b29a3603
END DESCRIPTION:
XS GIS Cut Line= 3
      2485013.09     13478212.47       2484431.5     13477131.76
      2484036.57     13477018.92
#Sta/Elev= 30
  3722.8  231.25  3770.5  231.01  3829.4   229.7  3943.1  228.52  3967.6  228.14
  4022.8   226.7  4056.8  226.98  4164.6  225.39  4465.8  223.43  4480.8  221.99
  4493.4  219.17  4509.6  218.53  4515.3  219.84  4553.4   219.3  4569.7  222.78
    4583  223.65  4732.3  223.72  4751.5  223.85  4923.7  222.27  4945.4  220.58
  4967.2  220.47  4985.1  216.56  4985.5  216.06  4990.6  216.56  5008.8  221.55
  5019.2  222.27  5137.6  225.74  5237.6  227.66  5357.1  227.06  5360.8  227.06
#Mann= 13 ,-1 , 0
  3722.8    .063       0  3770.5     .12       0  3829.4    .063       0
  3943.1     .07       0  3967.6     .05       0  4056.8     .07       0
  4164.6     .05       0  4732.3     .07       0  4751.5     .12       0
  4985.1     .05       0  4990.6     .12       0  5137.6    .035       0
  5357.1     .12       0
Bank Sta=4985.1,4990.6
XS Rating Curve= 0 ,0
Exp/Cntr=0.3,0.1

Type RM Length L Ch R = 1 ,2943    ,262,262,262
BEGIN DESCRIPTION:
Mapping XS 9e7c7c9c
END DESCRIPTION:
XS GIS Cut Line= 5
      2485082.54     13478173.41      2484855.16     13476895.38
      2484836.92     13476747.33      2484828.22     13476680.61
      2484308.73     13476708.56
#Sta/Elev= 30
  3701.9  232.38    3716   232.9    3721  231.68    3775  232.71  3973.3  228.97
  4118.9  225.98  4147.2  226.81  4167.5  225.51  4231.9  224.83  4553.5  222.33
  4570.7  223.12  4575.8  222.47  4639.7  221.97  4660.4  221.96  4688.8  221.29
  4861.7  221.27  4939.4  219.41  4959.8  217.79  4980.1  214.95  4997.6   211.9
  5020.5  213.66  5030.6  215.39  5050.8  214.64  5060.8   218.1    5081  220.38
  5166.3  220.34  5289.8  219.02  5405.7  219.93  5602.9   222.6  5736.7   224.9
#Mann= 10 ,-1 , 0
  3701.9    .063       0  3973.3    .035       0  4639.7     .07       0
  4660.4     .12       0  4861.7    .063       0  4980.1     .05       0
  5030.6    .063       0  5166.3     .12       0  5405.7     .05       0
  5602.9    .035       0
Bank Sta=4980.1,5030.6
XS Rating Curve= 0 ,0
Exp/Cntr=0.3,0.1

Type RM Length L Ch R = 1 ,2681    ,852,852,852
BEGIN DESCRIPTION:
Mapping XS 3617cbbd
END DESCRIPTION:
XS GIS Cut Line= 5
      2485295.21     13478173.42      2485069.12     13476772.85
      2485038.05     13476621.81      2484923.16      13476422.9
      2484473.59     13476599.99
#Sta/Elev= 30
  3581.3  235.61  3634.3  234.73  4129.2  228.65    4159  228.69  4229.5  226.06
  4309.2  224.17  4530.6  223.07  4683.6  221.78    4856  220.57  4896.5  215.58
  4931.8  213.44  4947.2  210.77  4977.6  210.46  4997.5  206.35  5028.4  210.49
  5089.7  214.71  5099.9     219  5161.2  219.37  5329.9  217.47  5345.7  218.53
  5351.4   220.3  5367.2  219.61    5373  221.03    5406  221.44  5424.9  220.45
  5430.4  218.46  5470.6  218.24  5577.4  218.69  5684.3  219.82  5867.1  221.92
#Mann= 13 ,-1 , 0
  3581.3    .045       0  3634.3    .035       0  4129.2    .045       0
    4159    .063       0  4229.5    .035       0  4530.6     .05       0
  4683.6    .035       0  4977.6    .035       0  5028.4    .035       0
  5161.2    .063       0  5470.6     .12       0  5577.4     .07       0
  5684.3    .035       0
Bank Sta=4977.6,5028.4
XS Rating Curve= 0 ,0
Exp/Cntr=0.3,0.1

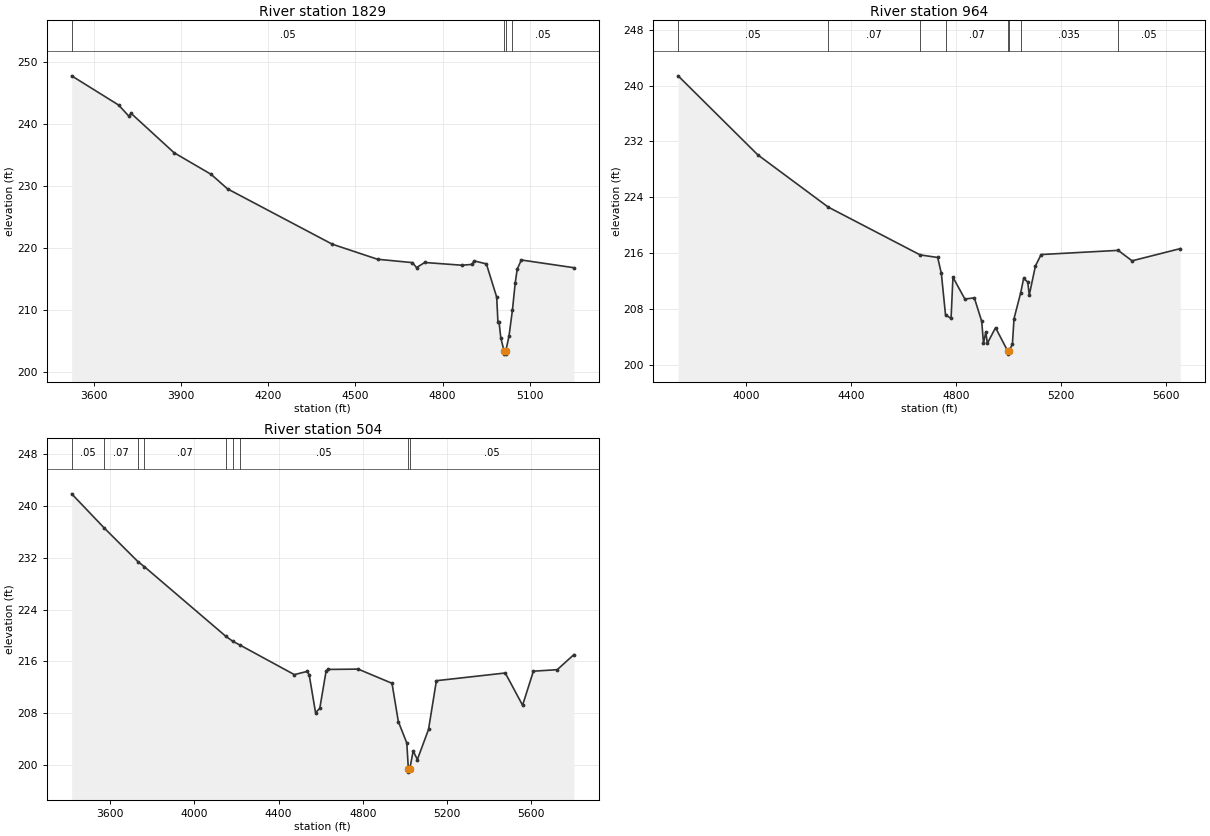
Type RM Length L Ch R = 1 ,1829    ,865,865,865
BEGIN DESCRIPTION:
Mapping XS 3a7c0e9e
END DESCRIPTION:
XS GIS Cut Line= 3
      2486332.46     13477206.21      2485283.86     13476178.44
      2485104.26     13475990.28
#Sta/Elev= 30
  3523.2  247.71  3684.9  243.01  3720.2  241.22  3727.4  241.69  3875.8  235.34
  4003.1  231.87  4059.7  229.53  4420.3  220.63  4575.9  218.21    4696  217.67
  4710.2  216.87  4738.5  217.69  4865.8  217.25  4901.2  217.38  4908.2  217.95
  4950.6  217.46  4986.1  212.12  4990.4  208.05  4994.3  208.05  5000.1  205.61
  5011.3  203.45  5011.8  202.95  5016.8  202.95  5017.3  203.45  5028.4  205.83
  5040.2  210.01  5049.8  214.38  5056.7  216.62  5070.9  218.09  5251.6  216.85
#Mann= 4 ,-1 , 0
  3523.2     .05       0  5011.3     .05       0  5017.3     .05       0
  5040.2     .05       0
Bank Sta=5011.3,5017.3
XS Rating Curve= 0 ,0
Exp/Cntr=0.3,0.1

Type RM Length L Ch R = 1 ,964     ,460,460,460
BEGIN DESCRIPTION:
Mapping XS 9a11defe
END DESCRIPTION:
XS GIS Cut Line= 4
      2486496.54      13476845.4      2486249.15      13476098.9
      2485745.68     13475799.42      2485218.13      13475920.5
#Sta/Elev= 30
    3740  241.41  4043.8  230.08    4312   222.6  4662.2  215.75  4729.1  215.38
    4743  213.09  4758.9  207.15    4780  206.65  4787.2  212.54  4832.6  209.43
  4868.7  209.59  4896.8  206.23  4903.6  203.09  4912.4  204.69  4918.3  203.08
  4949.5  205.32  4995.1  202.03  4995.6  201.53  5001.2  202.03  5013.7  202.93
  5019.9  206.62  5045.4  210.33  5056.5  212.37  5072.1  211.87  5078.1  210.01
  5101.4  214.16  5123.2   215.8  5416.7   216.4  5469.7   214.9  5653.5  216.65
#Mann= 8 ,-1 , 0
    3740     .05       0    4312     .07       0  4662.2     .05       0
  4758.9     .07       0  4995.1     .05       0  5001.2     .07       0
  5045.4    .035       0  5416.7     .05       0
Bank Sta=4995.1,5001.2
XS Rating Curve= 0 ,0
Exp/Cntr=0.3,0.1

Type RM Length L Ch R = 1 ,504     ,0,0,0
BEGIN DESCRIPTION:
TRIB 6 TO PERDIDO CREEK 6.0
END DESCRIPTION:
XS GIS Cut Line= 4
      2486539.95     13476845.43      2486375.02     13475573.72
      2485845.51      13475517.3      2485288.23     13475653.73
#Sta/Elev= 30
  3415.7  241.88  3571.1  236.59  3730.7  231.42  3761.5  230.63  4149.3  219.87
  4182.5   219.1  4214.9  218.55  4474.9  213.96  4535.4  214.45  4545.5  213.94
  4575.8  208.08  4595.9  208.75  4626.2  214.55  4636.3  214.76  4778.5  214.81
  4939.4  212.62  4969.6   206.7  5009.8   203.4  5017.2   199.4  5017.7   198.9
    5024   199.4    5040  202.15  5060.1  200.85  5113.1  205.49  5150.6  213.02
  5478.2  214.21  5560.5  209.23    5612  214.49  5725.3  214.72  5804.3  217.04
#Mann= 9 ,-1 , 0
  3415.7     .05       0  3571.1     .07       0  3730.7     .12       0
  3761.5     .07       0  4149.3     .12       0  4182.5     .07       0
  4214.9     .05       0  5017.2     .05       0    5024     .05       0
Bank Sta=5017.2,5024
XS Rating Curve= 0 ,0
Exp/Cntr=0.3,0.1

Chan Stop Cuts=-1
Use User Specified Reach Order=0
Composite Channel Slope=5