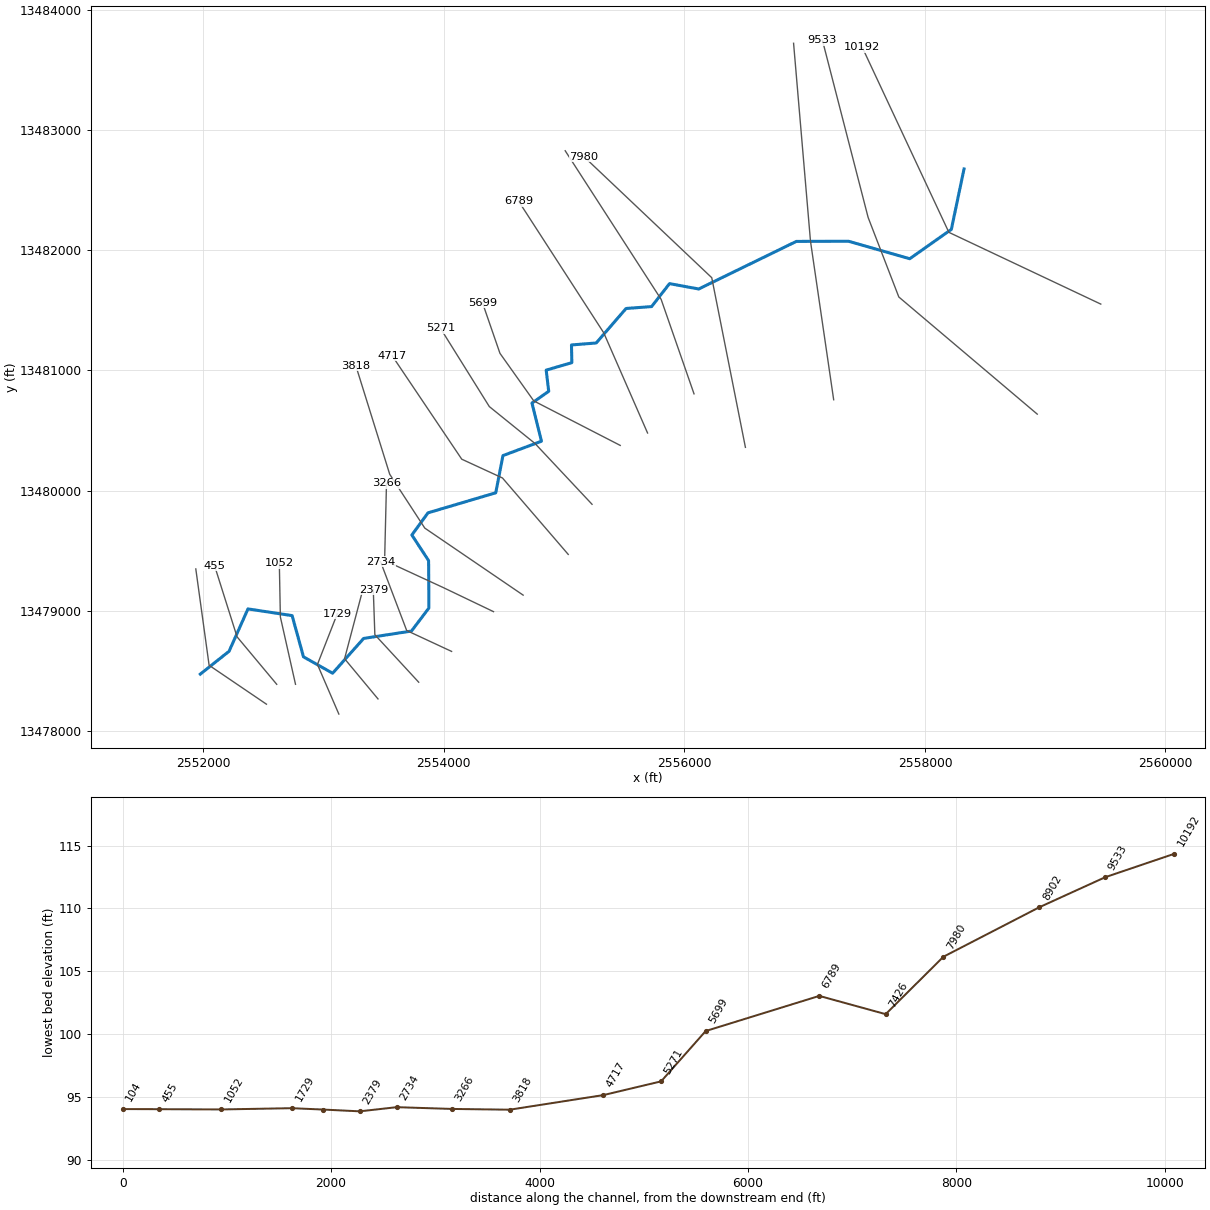
--- TRIB 7 TO COLETO CREEK RESERVOIR.prj (project) ---

Proj Title=TRIB 7 TO COLETO CREEK RESERVOIR Base Level Engineering
Current Plan=p01
Default Exp/Contr=0.3,0.1
English Units
Geom File=g01
Flow File=f01
Plan File=p01
Y Axis Title=Elevation
X Axis Title(PF)=Main Channel Distance
X Axis Title(XS)=Station
BEGIN DESCRIPTION:
TRIB 7 TO COLETO CREEK RESERVOIR
END DESCRIPTION:
DSS Export Rating Curves= 0
DSS Export Rating Curve Sorted= 0
DSS Export Volume Flow Curves= 0
DXF OffsetX= 0
DXF OffsetY= 0
DXF ScaleX= 1
DXF ScaleY= 10

--- TRIB 7 TO COLETO CREEK RESERVOIR.p01 (plan) ---

Plan Title=Multiple Run
Short Identifier=Multiple
Geom File=g01
Flow File=f01
Subcritical Flow
K Sum by GR= 0
Std Step Tol= 0.01
Critical Tol= 0.01
Num of Std Step Trials= 20
Max Error Tol= 0.3
Flow Tol Ratio= 0.001
Split Flow NTrial= 30
Split Flow Tol= 0.02
Split Flow Ratio= 0.02
Log Output Level= 0
Friction Slope Method= 1
Unsteady Friction Slope Method= 2
Unsteady Bridges Friction Slope Method= 1
Parabolic Critical Depth
Global Vel Dist=  1 , 1 , 1
Global Log Level= 0
CheckData=True
Encroach Param= -1, 0, 0, 0
BEGIN DESCRIPTION:
Multiple Run
END DESCRIPTION:

--- TRIB 7 TO COLETO CREEK RESERVOIR.f01 (steady flow) ---

Flow Title=Multiple
Number of Profiles=7
Profile Names=10-year,25-year,50-year,1pct_min,100-year,1pct_plu,500-year
River Rch & RM= TRIB 7 TO COLETO,Reach-1,10192
     729    1151    1524     975    1945    3881    3132
River Rch & RM= TRIB 7 TO COLETO,Reach-1,7980
    1646    2724    3721    2451    4891    9759    8360
River Rch & RM= TRIB 7 TO COLETO,Reach-1,3818
    1797    2977    4067    2679    5344   10664    9129
Boundary for River Rch & Prof#=TRIB 7 TO COLETO,Reach-1,1
Up Type=0
Dn Type=3
Dn Slope=0.005
Boundary for River Rch & Prof#=TRIB 7 TO COLETO,Reach-1,2
Up Type=0
Dn Type=3
Dn Slope=0.005
Boundary for River Rch & Prof#=TRIB 7 TO COLETO,Reach-1,3
Up Type=0
Dn Type=3
Dn Slope=0.005
Boundary for River Rch & Prof#=TRIB 7 TO COLETO,Reach-1,4
Up Type=0
Dn Type=3
Dn Slope=0.005
Boundary for River Rch & Prof#=TRIB 7 TO COLETO,Reach-1,5
Up Type=0
Dn Type=3
Dn Slope=0.005
Boundary for River Rch & Prof#=TRIB 7 TO COLETO,Reach-1,6
Up Type=0
Dn Type=3
Dn Slope=0.005
Boundary for River Rch & Prof#=TRIB 7 TO COLETO,Reach-1,7
Up Type=0
Dn Type=3
Dn Slope=0.005

--- TRIB 7 TO COLETO CREEK RESERVOIR.g01 (geometry) ---

Geom Title=Existing Conditions
Program Version=4.10

River Reach=TRIB 7 TO COLETO,Reach-1
Reach XY= 30
        2558325.       13482675.      2558219.48     13482172.56
      2557873.53     13481928.53      2557364.56     13482073.94
      2556930.94     13482072.74      2556119.11     13481676.97
      2555876.28     13481721.63       2555727.3      13481530.8
      2555515.01     13481514.93       2555266.7     13481228.07
      2555061.19     13481211.77      2555064.04     13481064.57
      2554850.84      13481002.3      2554871.96     13480826.42
      2554732.67     13480728.66      2554811.78     13480411.33
       2554491.3     13480291.77      2554431.52     13479982.68
      2553868.05     13479815.82      2553733.98     13479631.66
       2553873.2     13479418.89      2553875.85     13479024.99
      2553731.05     13478833.12      2553333.34     13478771.83
      2553075.09     13478482.29        2552833.     13478618.67
      2552738.43     13478961.46      2552371.38     13479017.14
      2552214.35       13478665.        2551975.       13478475.

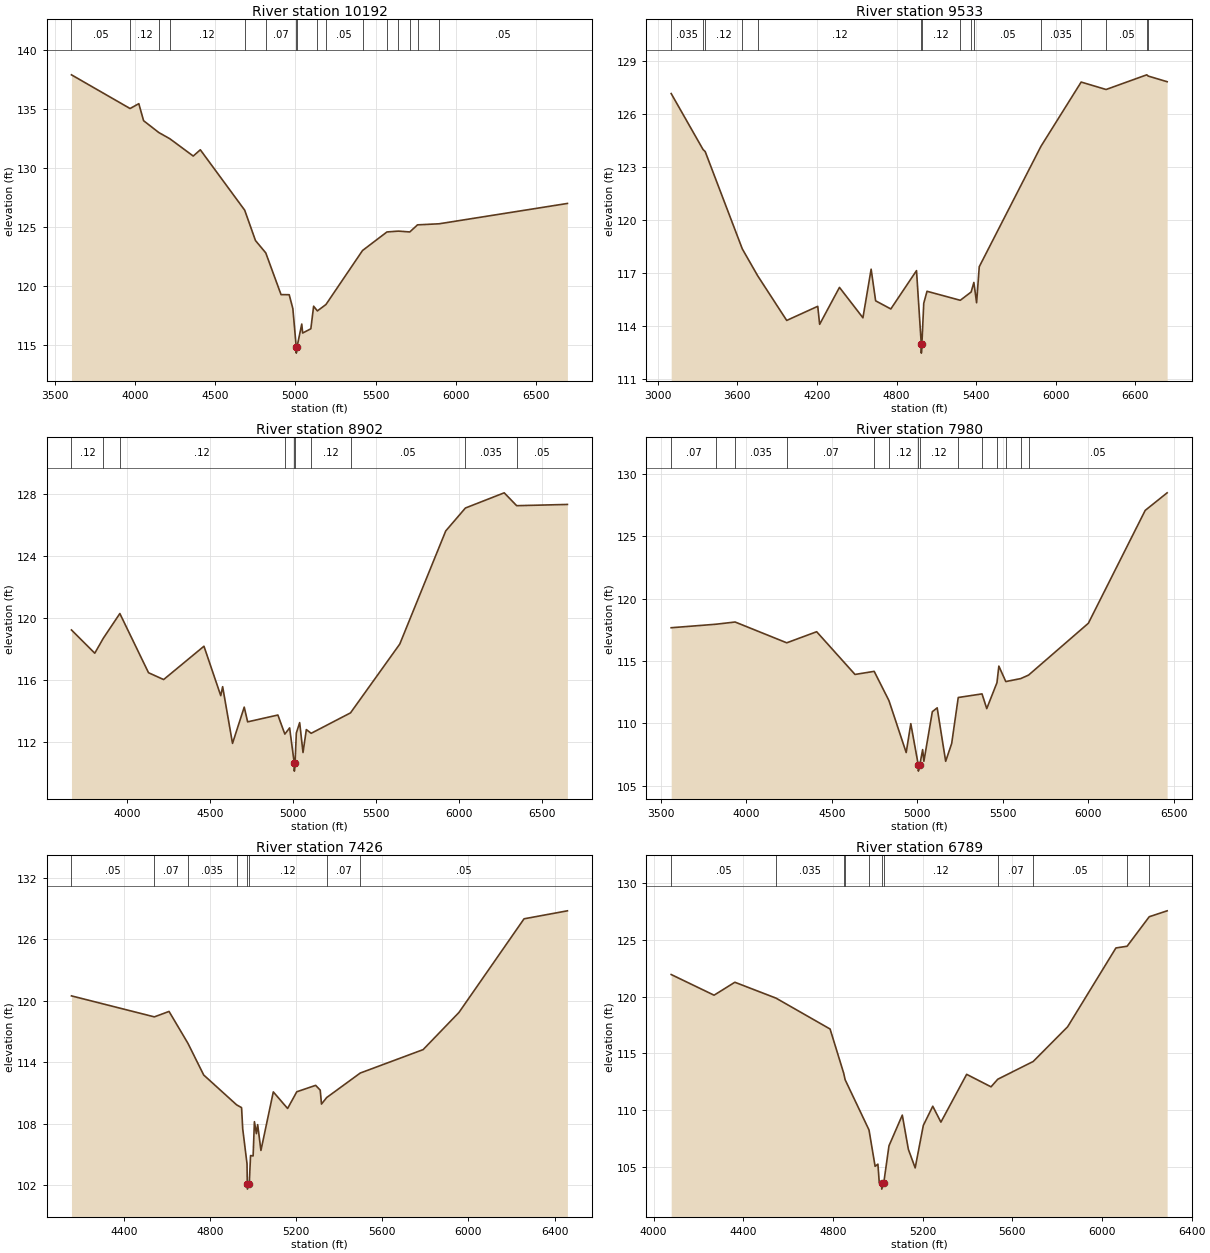
Type RM Length L Ch R = 1 ,10192   ,659,659,659
BEGIN DESCRIPTION:
Mapping XS c43d60ec
END DESCRIPTION:
XS GIS Cut Line= 3
      2559461.93     13481551.44      2558198.85     13482148.06
      2557479.21     13483685.15
#Sta/Elev= 30
  3603.1  137.87  3968.7  135.02  4023.3  135.43  4053.1  133.99  4147.9  132.99
  4217.3  132.46  4362.8     131    4407  131.53  4683.9  126.42  4751.2  123.85
  4815.3  122.81  4910.6  119.28  4961.6  119.27  4984.4  118.09  5005.5  114.83
  5005.8  114.33  5009.9  114.83  5039.9  116.79  5045.4  116.03  5096.6  116.39
  5113.9   118.3  5137.2   117.9  5190.7  118.44    5419  123.01  5571.4  124.58
  5642.5  124.65  5713.8  124.58  5762.1  125.18  5896.8  125.27  6697.2  126.99
#Mann= 16 ,-1 , 0
  3603.1     .05       0  3968.7     .12       0  4147.9    .035       0
  4217.3     .12       0  4683.9    .035       0  4815.3     .07       0
  5005.5     .05       0  5009.9     .07       0  5137.2     .07       0
  5190.7     .05       0    5419    .035       0  5571.4     .05       0
  5642.5    .035       0  5713.8     .07       0  5762.1    .035       0
  5896.8     .05       0
Bank Sta=5005.5,5009.9
XS Rating Curve= 0 ,0
Exp/Cntr=0.3,0.1

Type RM Length L Ch R = 1 ,9533    ,631,631,631
BEGIN DESCRIPTION:
Mapping XS 0cd39a86
END DESCRIPTION:
XS GIS Cut Line= 4
      2558933.75     13480636.54      2557782.73     13481610.49
      2557527.52     13482271.94       2557147.3     13483745.93
#Sta/Elev= 30
  3101.1  127.17  3341.6     124  3357.3  123.89  3637.2  118.38    3753  116.86
    3972  114.33    4206  115.13  4220.3  114.11  4369.7   116.2  4546.6  114.48
  4608.5  117.23  4642.4  115.44  4756.9  114.98  4950.6  117.15  4986.6  112.98
    4987  112.48  4991.1  112.98  5005.2   115.3  5029.8  115.98  5280.7  115.47
  5362.6  115.94    5383  116.48  5403.6  115.33  5423.6  117.37  5888.5  124.18
  6191.9  127.82  6379.9   127.4  6686.5  128.23  6697.4  128.16  6840.1  127.84
#Mann= 15 ,-1 , 0
  3101.1    .035       0  3341.6     .05       0  3357.3     .12       0
  3637.2    .035       0    3753     .12       0  4986.6     .05       0
  4991.1     .12       0  5280.7     .07       0  5362.6     .12       0
    5383     .05       0  5888.5    .035       0  6191.9     .07       0
  6379.9     .05       0  6686.5    .035       0  6697.4     .05       0
Bank Sta=4986.6,4991.1
XS Rating Curve= 0 ,0
Exp/Cntr=0.3,0.1

Type RM Length L Ch R = 1 ,8902    ,922,922,922
BEGIN DESCRIPTION:
Mapping XS e4d623e0
END DESCRIPTION:
XS GIS Cut Line= 3
      2557241.07     13480756.27      2557048.35     13482074.03
      2556907.73     13483719.86
#Sta/Elev= 30
  3667.2  119.21  3807.4  117.71  3859.1  118.68  3958.3  120.27  4130.8  116.45
  4221.8  116.01  4464.3  118.16  4565.4  114.97  4576.7  115.55  4636.1  111.89
  4706.5  114.23  4727.1  113.28    4909  113.72  4950.9  112.49  4979.7  112.89
  5007.7   110.6    5008   110.1  5012.2   110.6    5020  112.56  5040.1  113.23
  5060.2   111.3  5080.2  112.78  5109.3  112.54    5346  113.86  5642.3   118.3
  5918.8   125.6  6037.2  127.08  6270.6  128.06  6345.5  127.23  6650.8  127.31
#Mann= 10 ,-1 , 0
  3667.2     .12       0  3859.1    .035       0  3958.3     .12       0
  4950.9     .07       0  5007.7     .05       0  5012.2     .07       0
  5109.3     .12       0    5346     .05       0  6037.2    .035       0
  6345.5     .05       0
Bank Sta=5007.7,5012.2
XS Rating Curve= 0 ,0
Exp/Cntr=0.3,0.1

Type RM Length L Ch R = 1 ,7980    ,554,554,554
BEGIN DESCRIPTION:
Mapping XS 6ea1fb90
END DESCRIPTION:
XS GIS Cut Line= 3
      2556507.33     13480360.33      2556227.38     13481770.95
      2555165.28     13482776.76
#Sta/Elev= 30
  3561.1  117.67  3821.7  117.95    3935  118.13    4237  116.46    4412  117.35
  4636.3  113.92  4748.5  114.17  4834.8  111.82  4935.7  107.65  4962.6  109.97
  5006.4  106.66  5006.9  106.16  5015.3  106.66  5031.9  107.89  5039.2  106.95
  5088.6  110.93  5116.9  111.24  5166.6  106.95  5201.8  108.38  5240.2  112.07
  5379.2  112.36  5406.9  111.18  5466.6  113.26  5477.7  114.59  5518.3  113.35
  5605.9  113.59  5651.6  113.87  6001.2  118.03  6333.7  127.09    6462   128.5
#Mann= 14 ,-1 , 0
  3561.1     .07       0  3821.7     .05       0    3935    .035       0
    4237     .07       0  4748.5    .035       0  4834.8     .12       0
  5006.4     .05       0  5015.3     .12       0  5240.2    .035       0
  5379.2     .07       0  5466.6     .12       0  5518.3     .07       0
  5605.9     .12       0  5651.6     .05       0
Bank Sta=5006.4,5015.3
XS Rating Curve= 0 ,0
Exp/Cntr=0.3,0.1

Type RM Length L Ch R = 1 ,7426    ,637,637,637
BEGIN DESCRIPTION:
Mapping XS 5c5a75a6
END DESCRIPTION:
XS GIS Cut Line= 3
      2556079.99     13480805.25      2555806.55     13481590.83
      2555008.96     13482826.22
#Sta/Elev= 30
  4157.2  120.48  4541.9  118.43  4610.2  118.96  4697.8  115.85  4771.1  112.75
  4923.6  109.84  4946.9  109.56  4952.2  107.49  4972.2  104.07  4973.5   102.1
    4974   101.6  4982.5   102.1  4988.6  104.88  5000.5  104.84  5006.5  108.19
  5015.7  107.02  5021.6   107.9  5036.8  105.38  5094.2   111.1  5160.6  109.48
  5203.1  111.11  5290.8  111.74    5312  111.27  5317.9  109.91  5342.1  110.55
  5497.7  112.94  5789.7  115.23    5956  118.86  6258.2  128.01  6459.5  128.79
#Mann= 8 ,-1 , 0
  4157.2     .05       0  4541.9     .07       0  4697.8    .035       0
  4923.6     .12       0  4973.5     .05       0  4982.5     .12       0
  5342.1     .07       0  5497.7     .05       0
Bank Sta=4973.5,4982.5
XS Rating Curve= 0 ,0
Exp/Cntr=0.3,0.1

Type RM Length L Ch R = 1 ,6789    ,1090,1090,1090
BEGIN DESCRIPTION:
Mapping XS 6eab4380
END DESCRIPTION:
XS GIS Cut Line= 3
      2555693.69     13480479.75      2555329.12     13481313.05
      2554621.64     13482406.82
#Sta/Elev= 30
  4078.4  121.95  4269.7  120.13  4362.3  121.27  4546.1  119.87  4787.2  117.15
  4847.7  113.27  4854.4  112.68  4960.8  108.26    4988  105.06  5000.5  105.25
  5006.5  103.62  5017.1  103.55  5017.6  103.05  5026.2  103.55  5049.8  106.86
  5109.3  109.57  5136.4  106.55  5166.7  104.92    5203  108.66  5245.2  110.35
  5281.5  108.95  5396.3  113.16  5505.1  112.06  5535.2  112.73  5693.1  114.29
  5846.8  117.35  6062.1  124.29    6112  124.44  6210.8  127.04  6290.6  127.56
#Mann= 11 ,-1 , 0
  4078.4     .05       0  4546.1    .035       0  4847.7     .05       0
  4854.4    .035       0  4960.8     .12       0  5017.1     .05       0
  5026.2     .12       0  5535.2     .07       0  5693.1     .05       0
    6112    .035       0  6210.8     .05       0
Bank Sta=5017.1,5026.2
XS Rating Curve= 0 ,0
Exp/Cntr=0.3,0.1

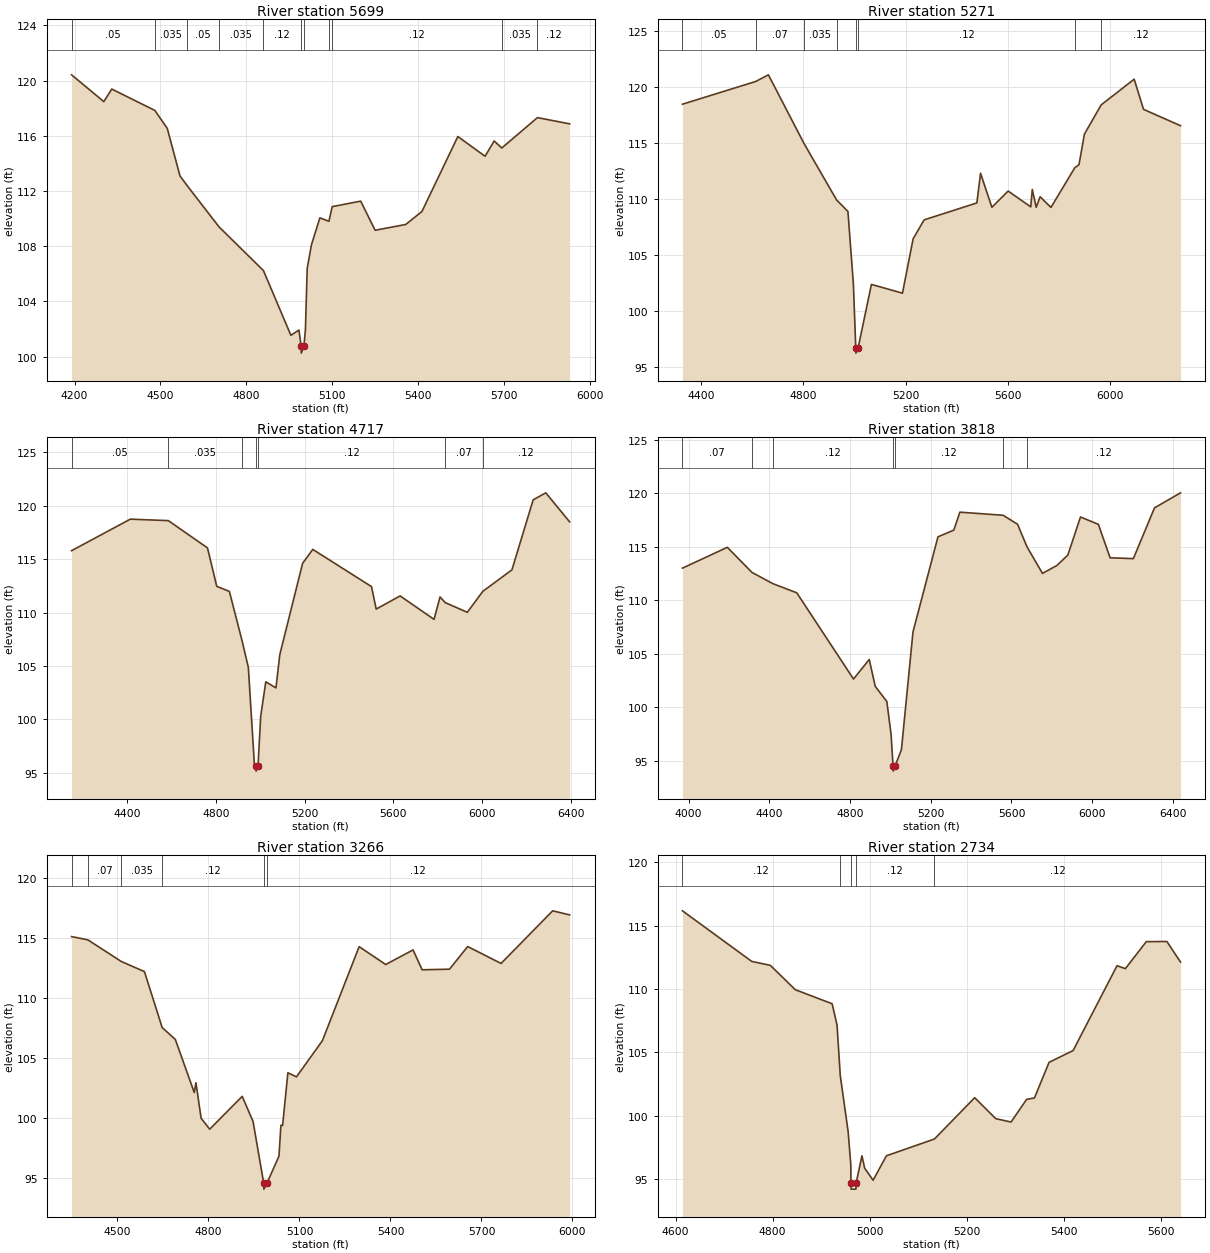
Type RM Length L Ch R = 1 ,5699    ,428,428,428
BEGIN DESCRIPTION:
Mapping XS 9fa56c85
END DESCRIPTION:
XS GIS Cut Line= 4
      2555466.49     13480376.56      2554747.71     13480746.37
      2554466.46      13481142.2      2554320.62     13481564.09
#Sta/Elev= 30
  4189.7  120.42  4302.4  118.48  4330.2  119.39  4480.8  117.84  4524.1  116.54
  4568.5   113.1    4593  112.41  4705.2   109.4  4860.2  106.24  4956.1  101.55
  4984.2  101.93    4992  100.76  4992.5  100.26  5001.5  100.76  5006.9  101.97
  5013.1   106.4  5027.8   108.1  5057.4  110.06    5089  109.81  5100.4  110.87
    5200  111.27  5250.4  109.16  5357.4  109.58    5414  110.52  5539.5  115.95
  5634.7  114.52  5666.4  115.63  5693.1  115.12  5817.6  117.32    5930  116.87
#Mann= 11 ,-1 , 0
  4189.7     .05       0  4480.8    .035       0    4593     .05       0
  4705.2    .035       0  4860.2     .12       0    4992     .05       0
  5001.5     .12       0    5089     .07       0  5100.4     .12       0
  5693.1    .035       0  5817.6     .12       0
Bank Sta=4992,5001.5
XS Rating Curve= 0 ,0
Exp/Cntr=0.3,0.1

Type RM Length L Ch R = 1 ,5271    ,554,554,554
BEGIN DESCRIPTION:
Mapping XS 713dd37c
END DESCRIPTION:
XS GIS Cut Line= 4
      2555232.08       13479887.      2554758.13      13480392.2
      2554377.92     13480699.49      2553971.82      13481350.3
#Sta/Elev= 30
  4326.6  118.47  4613.6   120.5  4662.8  121.09  4802.5  114.95  4929.6  109.93
    4974   108.9  4995.4  102.41  5004.6   96.76  5005.1   96.26  5014.2   96.76
  5065.9  102.39  5187.4  101.61  5229.1  106.46  5272.2  108.15  5478.5  109.66
  5492.9  112.31  5537.2  109.27  5600.9  110.72  5689.4  109.31  5695.3  110.86
  5710.6  109.27  5725.9  110.21  5768.4  109.26  5861.6   112.8  5878.1  113.07
  5899.3   115.8    5965  118.41    6094   120.7  6130.6  118.01  6275.3  116.55
#Mann= 8 ,-1 , 0
  4326.6     .05       0  4613.6     .07       0  4802.5    .035       0
  4929.6     .12       0  5004.6     .05       0  5014.2     .12       0
  5861.6    .035       0    5965     .12       0
Bank Sta=5004.6,5014.2
XS Rating Curve= 0 ,0
Exp/Cntr=0.3,0.1

Type RM Length L Ch R = 1 ,4717    ,899,899,899
BEGIN DESCRIPTION:
Mapping XS 4307ec1b
END DESCRIPTION:
XS GIS Cut Line= 4
      2555034.15     13479470.35      2554487.29     13480105.74
      2554148.75     13480261.99      2553571.08     13481120.69
#Sta/Elev= 30
  4149.1  115.78  4414.3  118.73  4585.6  118.59  4762.1  116.04  4803.8  112.45
  4860.9  111.97  4918.5  107.32  4946.4  104.86  4973.9   95.68  4980.5   95.67
    4981   95.17  4990.1   95.67    5002  100.29    5025  103.52  5070.9  102.95
  5088.3  106.07  5191.1   114.6    5237   115.9  5501.9  112.42  5522.9  110.32
  5630.9  111.55  5783.9  109.36  5810.9  111.45  5834.8  110.92  5933.9  110.02
  6003.9  111.98  6135.2  113.99  6230.8  120.53  6287.8  121.19  6395.2  118.48
#Mann= 7 ,-1 , 0
  4149.1     .05       0  4585.6    .035       0  4918.5     .12       0
  4980.5     .05       0  4990.1     .12       0  5834.8     .07       0
  6003.9     .12       0
Bank Sta=4980.5,4990.1
XS Rating Curve= 0 ,0
Exp/Cntr=0.3,0.1

Type RM Length L Ch R = 1 ,3818    ,552,552,552
BEGIN DESCRIPTION:
Mapping XS 0287ef2f
END DESCRIPTION:
XS GIS Cut Line= 4
      2554659.18     13479131.78      2553841.46     13479689.08
      2553549.79     13480136.99      2553268.54     13481038.04
#Sta/Elev= 30
  3969.8  113.01  4192.1  114.96  4314.2  112.61  4417.5  111.56  4536.2   110.7
  4817.4  102.63  4895.3  104.46  4925.2  101.94  4982.4  100.53  5003.4   97.48
  5013.2   94.51  5013.7   94.01  5023.9   94.51  5054.8   96.02  5112.1  107.04
  5235.9  115.94  5314.4  116.57  5344.6  118.25  5558.6  117.96  5630.3  117.12
  5676.8  115.02  5753.7  112.52  5825.3  113.26  5879.4  114.23  5942.2   117.8
  6030.7  117.11  6088.9  113.98  6204.1   113.9  6308.9  118.65  6437.8  120.06
#Mann= 7 ,-1 , 0
  3969.8     .07       0  4314.2    .035       0  4417.5     .12       0
  5013.2     .05       0  5023.9     .12       0  5558.6    .035       0
  5676.8     .12       0
Bank Sta=5013.2,5023.9
XS Rating Curve= 0 ,0
Exp/Cntr=0.3,0.1

Type RM Length L Ch R = 1 ,3266    ,532,532,532
BEGIN DESCRIPTION:
Mapping XS 905f4b03
END DESCRIPTION:
XS GIS Cut Line= 4
      2554412.92      13478994.4      2553996.25     13479194.06
      2553507.53     13479419.75      2553523.12     13480060.81
#Sta/Elev= 30
  4348.9  115.14  4402.5  114.87    4513  113.06  4589.1  112.22  4647.6  107.55
  4690.9  106.56  4753.3  102.13  4758.8  102.95    4776   99.98  4804.2   99.07
  4911.4  101.81  4947.2   99.71  4982.2   94.57  4982.7   94.07  4992.9   94.57
  5032.6   96.82  5038.9    99.4  5044.5   99.38  5061.9  103.78  5090.3  103.44
  5175.8  106.46  5296.8   114.3  5384.5  112.81  5474.5  114.03  5504.5  112.37
  5594.6  112.42  5654.6  114.31  5764.6   112.9  5934.7  117.29  5990.5  116.95
#Mann= 6 ,-1 , 0
  4348.9     .05       0  4402.5     .07       0    4513    .035       0
  4647.6     .12       0  4982.2     .05       0  4992.9     .12       0
Bank Sta=4982.2,4992.9
XS Rating Curve= 0 ,0
Exp/Cntr=0.3,0.1

Type RM Length L Ch R = 1 ,2734    ,355,355,355
BEGIN DESCRIPTION:
Mapping XS 585b18c2
END DESCRIPTION:
XS GIS Cut Line= 3
      2554064.32     13478663.84       2553691.1     13478837.43
      2553473.21     13479411.13
#Sta/Elev= 30
  4614.3  116.16  4756.9  112.17  4795.2  111.86  4846.5  109.94  4922.4  108.83
  4932.5  107.16  4939.1  103.19  4955.4   98.73  4960.9    96.1  4961.1   94.71
  4961.6   94.21  4971.4   94.21  4971.9   94.71  4983.8   96.84  4989.3   95.87
  5006.7   94.91  5034.2   96.84  5132.9   98.16  5215.9  101.42  5259.2   99.77
  5290.7    99.5  5322.8  101.29  5338.9   101.4    5369  104.21  5418.5  105.14
  5508.9  111.83  5526.1   111.6  5569.2  113.73  5611.6  113.74  5639.6  112.12
#Mann= 5 ,-1 , 0
  4614.3     .12       0  4939.1     .12       0  4961.1     .05       0
  4971.9     .12       0  5132.9     .12       0
Bank Sta=4961.1,4971.9
XS Rating Curve= 0 ,0
Exp/Cntr=0.3,0.1

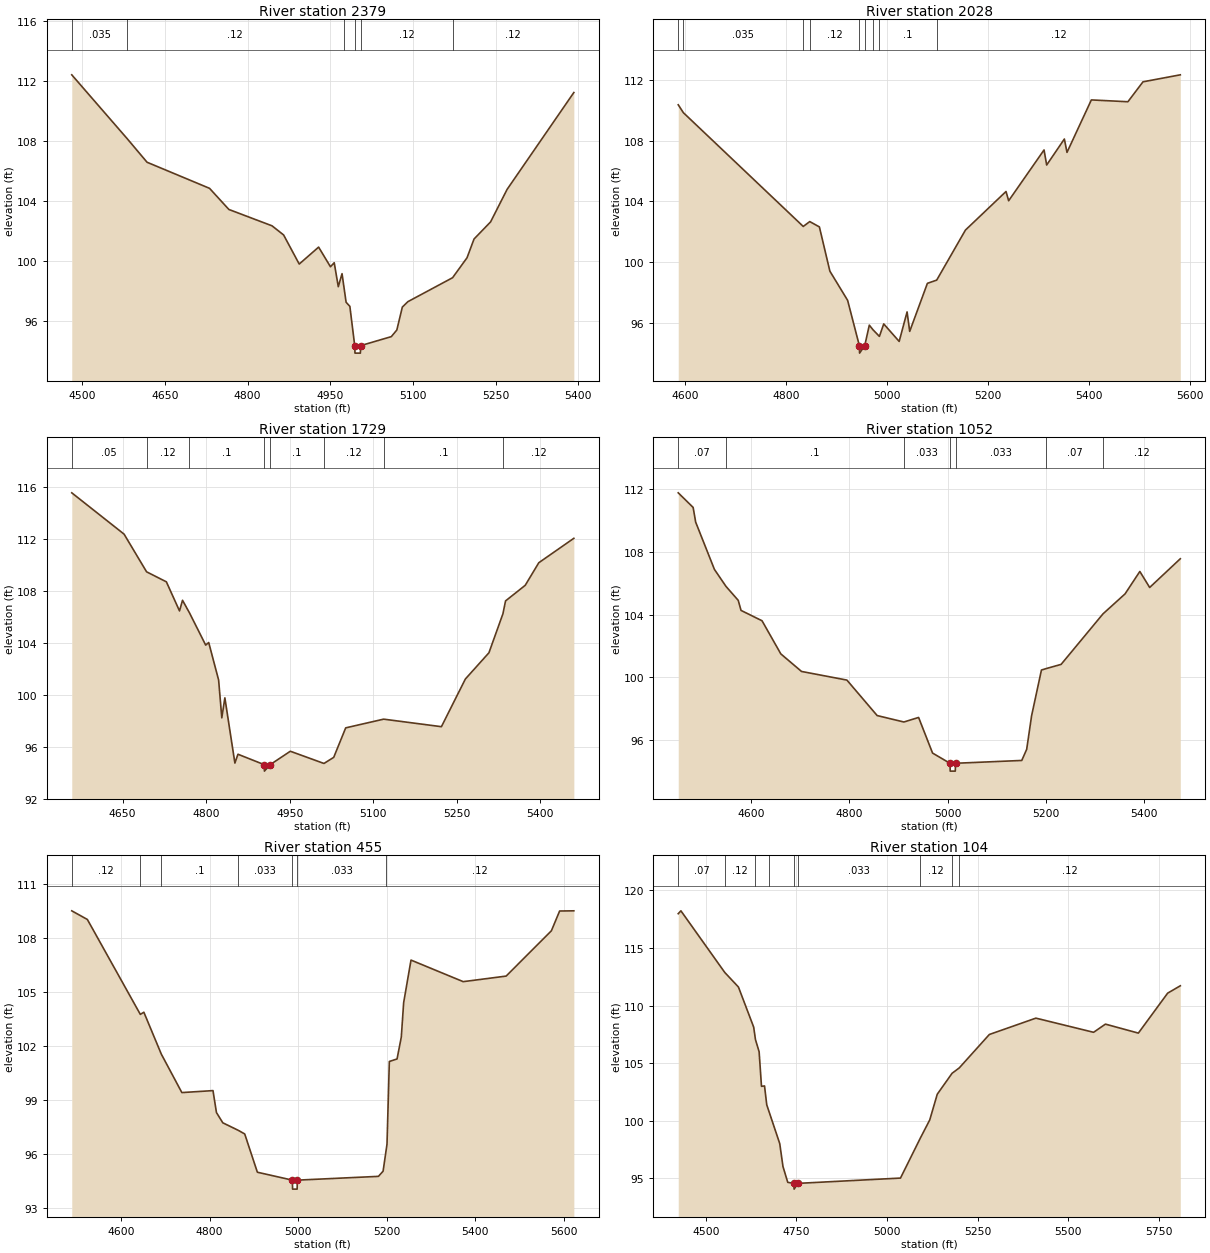
Type RM Length L Ch R = 1 ,2379    ,351,351,351
BEGIN DESCRIPTION:
Mapping XS bef3dc12
END DESCRIPTION:
XS GIS Cut Line= 3
       2553790.9     13478407.78      2553426.35     13478802.71
      2553413.32     13479176.02
#Sta/Elev= 30
  4481.1  112.44  4581.7  108.18  4617.7  106.61  4731.1  104.87  4766.2  103.46
  4844.5  102.37  4865.5  101.76  4893.8   99.82    4929  100.95  4950.5   99.64
  4957.3   99.91  4964.7   98.31  4971.5   99.18  4974.2   98.48  4978.9   97.27
  4985.7      97  4994.5   94.38    4995   93.88  5004.8   93.88  5005.3   94.38
  5060.9   94.98  5070.9   95.42  5080.9   96.95  5090.9   97.31  5172.1   98.91
  5198.3  100.24    5211  101.49    5241  102.63    5271   104.8  5392.1  111.26
#Mann= 6 ,-1 , 0
  4481.1    .035       0  4581.7     .12       0  4974.2     .12       0
  4994.5     .05       0  5005.3     .12       0  5172.1     .12       0
Bank Sta=4994.5,5005.3
XS Rating Curve= 0 ,0
Exp/Cntr=0.3,0.1

Type RM Length L Ch R = 1 ,2028    ,299,299,299
BEGIN DESCRIPTION:
Mapping XS 9f089751
END DESCRIPTION:
XS GIS Cut Line= 3
      2553452.36     13478268.89      2553174.61     13478603.06
      2553317.83     13479145.54
#Sta/Elev= 30
  4585.7  110.35  4595.9  109.83  4833.6  102.35  4846.5  102.67  4865.6  102.32
  4886.4   99.41  4921.6   97.49  4944.8   94.52  4945.3   94.02  4955.6   94.52
  4964.6   95.86  4971.8   95.56  4984.6   95.12  4993.2   95.94  5023.8   94.79
  5039.5   96.73  5044.7   95.45  5079.8   98.61  5098.2   98.82  5155.2  102.11
  5235.7  104.65  5240.9  104.04  5311.1  107.38  5316.3  106.39  5351.4   108.1
  5356.6  107.22  5404.9  110.67  5477.4  110.55  5507.3  111.86  5581.3  112.32
#Mann= 9 ,-1 , 0
  4585.7     .07       0  4595.9    .035       0  4833.6     .12       0
  4846.5     .12       0  4944.8     .05       0  4955.6     .12       0
  4971.8    .033       0  4984.6      .1       0  5098.2     .12       0
Bank Sta=4944.8,4955.6
XS Rating Curve= 0 ,0
Exp/Cntr=0.3,0.1

Type RM Length L Ch R = 1 ,1729    ,677,677,677
BEGIN DESCRIPTION:
Mapping XS 0ec08a97
END DESCRIPTION:
XS GIS Cut Line= 3
      2553126.85     13478143.02      2552948.92     13478555.31
      2553113.84     13478976.31
#Sta/Elev= 30
  4558.9  115.55  4652.8  112.37  4693.2  109.47  4728.7   108.7  4752.3  106.46
  4757.7  107.28  4770.2  106.31  4799.3  103.83  4804.7  104.03  4822.5  101.14
  4828.2   98.23  4833.7   99.77  4851.7   94.75  4857.2   95.43  4904.2   94.63
  4904.7   94.13  4915.1   94.63  4951.2   95.66  5011.6   94.72  5029.1   95.19
  5050.6   97.46  5118.7   98.13  5222.4   97.55  5265.4  101.22  5307.7  103.24
  5332.8  106.24  5337.5  107.23  5372.8  108.43  5397.2  110.17  5460.1  112.05
#Mann= 8 ,-1 , 0
  4558.9     .05       0  4693.2     .12       0  4770.2      .1       0
  4904.2    .033       0  4915.1      .1       0  5011.6     .12       0
  5118.7      .1       0  5332.8     .12       0
Bank Sta=4904.2,4915.1
XS Rating Curve= 0 ,0
Exp/Cntr=0.3,0.1

Type RM Length L Ch R = 1 ,1052    ,597,597,597
BEGIN DESCRIPTION:
Mapping XS 81e992fd
END DESCRIPTION:
XS GIS Cut Line= 3
      2552766.62     13478390.39      2552640.76     13478950.28
      2552632.08     13479397.33
#Sta/Elev= 30
  4452.3  111.76  4482.6  110.83  4487.8  109.89  4525.9  106.88  4549.4   105.8
  4574.3  104.91    4580  104.27  4622.7  103.61  4660.9   101.5    4703  100.38
  4795.3   99.83  4856.8   97.57  4911.2   97.16  4941.1   97.45  4969.5   95.18
  5004.9   94.53  5005.4   94.03  5015.7   94.03  5016.2   94.53  5150.9   94.71
  5160.9   95.42  5170.9   97.56  5190.9  100.47  5200.2  100.56  5230.9  100.83
  5316.1  104.05  5360.9  105.32    5391  106.75    5411  105.73  5473.3  107.56
#Mann= 7 ,-1 , 0
  4452.3     .07       0  4549.4      .1       0  4911.2    .033       0
  5004.9    .033       0  5016.2    .033       0  5200.2     .07       0
  5316.1     .12       0
Bank Sta=5004.9,5016.2
XS Rating Curve= 0 ,0
Exp/Cntr=0.3,0.1

Type RM Length L Ch R = 1 ,455     ,351,351,351
BEGIN DESCRIPTION:
Mapping XS 26ea83c4
END DESCRIPTION:
XS GIS Cut Line= 3
      2552610.39     13478390.37      2552280.51     13478785.35
      2552093.88     13479375.63
#Sta/Elev= 30
    4489  109.53  4524.2  109.05  4643.8  103.77  4651.8  103.89  4691.2  101.56
  4737.6   99.42  4807.9   99.53  4815.7   98.31    4830   97.74  4864.2   97.33
  4879.5   97.12  4908.1   94.99  4987.1   94.55  4987.6   94.05  4997.9   94.05
  4998.4   94.55  5181.5   94.76    5192   95.05  5197.7   96.02  5200.8   96.55
  5206.1  101.15  5223.5  101.29  5233.1  102.51  5238.4  104.42    5255  106.79
  5372.9  105.59  5469.8   105.9    5572  108.42  5590.6  109.52  5622.7  109.53
#Mann= 7 ,-1 , 0
    4489     .12       0  4643.8     .07       0  4691.2      .1       0
  4864.2    .033       0  4987.1    .033       0  4998.4    .033       0
  5197.7     .12       0
Bank Sta=4987.1,4998.4
XS Rating Curve= 0 ,0
Exp/Cntr=0.3,0.1

Type RM Length L Ch R = 1 ,104     ,0,0,0
BEGIN DESCRIPTION:
TRIB 7 TO COLETO CREEK RESERVOIR 1.0
END DESCRIPTION:
XS GIS Cut Line= 3
      2552524.97     13478225.02      2552048.31     13478548.39
      2551937.63     13479349.58
#Sta/Elev= 30
    4424  117.98  4431.4  118.23  4552.3  112.88  4590.1  111.61  4632.1  108.13
    4637  107.05  4647.1  105.99  4653.6  102.99    4662  103.02  4668.1  101.39
  4673.4  100.89    4704   98.01  4712.9   96.02  4726.1   94.65  4743.1   94.56
  4743.6   94.06  4754.5   94.56    5037   95.02  5091.9    98.5  5117.7  100.07
  5138.4   102.3  5179.3  104.12  5199.2  104.59  5282.1  107.49  5410.5  108.91
  5569.6  107.68  5602.3  108.39  5693.1  107.61  5773.9  111.08  5808.8  111.72
#Mann= 9 ,-1 , 0
    4424     .07       0  4552.3     .12       0    4637     .07       0
  4673.4    .033       0  4743.1    .033       0  4754.5    .033       0
  5091.9     .12       0  5179.3    .033       0  5199.2     .12       0
Bank Sta=4743.1,4754.5
XS Rating Curve= 0 ,0
Exp/Cntr=0.3,0.1

Chan Stop Cuts=-1
Use User Specified Reach Order=0
Composite Channel Slope=5