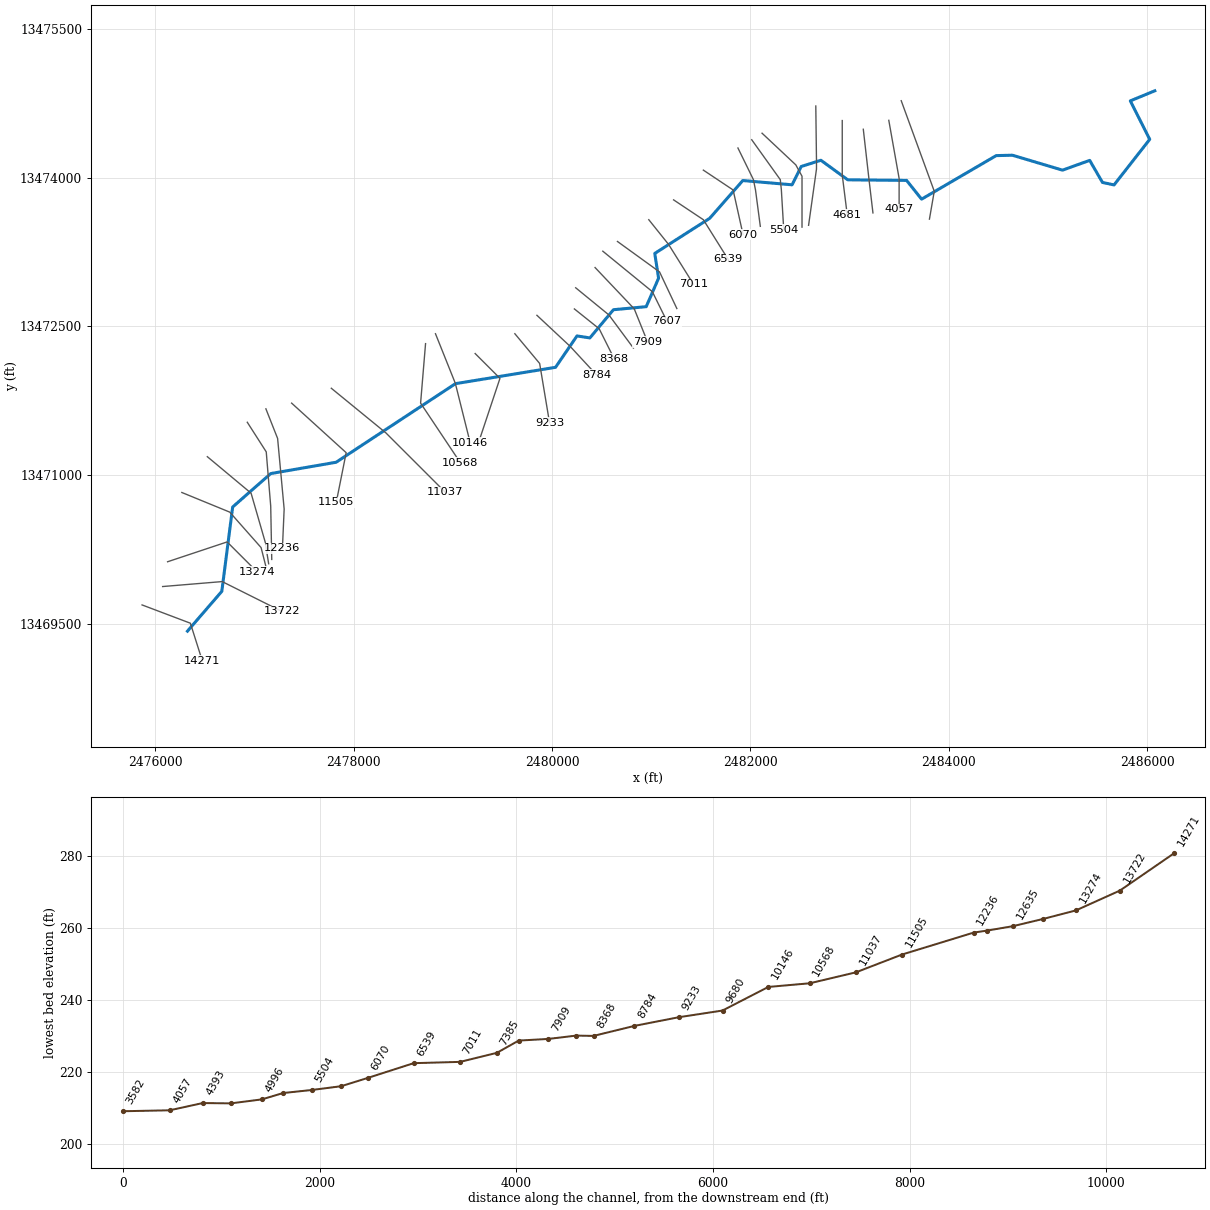
--- TRIB 7 TO PERDIDO CREEK.prj (project) ---

Proj Title=TRIB 7 TO PERDIDO CREEK Base Level Engineering
Current Plan=p01
Default Exp/Contr=0.3,0.1
English Units
Geom File=g01
Flow File=f01
Plan File=p01
Y Axis Title=Elevation
X Axis Title(PF)=Main Channel Distance
X Axis Title(XS)=Station
BEGIN DESCRIPTION:
TRIB 7 TO PERDIDO CREEK
END DESCRIPTION:
DSS Export Rating Curves= 0
DSS Export Rating Curve Sorted= 0
DSS Export Volume Flow Curves= 0
DXF OffsetX= 0
DXF OffsetY= 0
DXF ScaleX= 1
DXF ScaleY= 10

--- TRIB 7 TO PERDIDO CREEK.p01 (plan) ---

Plan Title=Multiple Run
Short Identifier=Multiple
Geom File=g01
Flow File=f01
Subcritical Flow
K Sum by GR= 0
Std Step Tol= 0.01
Critical Tol= 0.01
Num of Std Step Trials= 20
Max Error Tol= 0.3
Flow Tol Ratio= 0.001
Split Flow NTrial= 30
Split Flow Tol= 0.02
Split Flow Ratio= 0.02
Log Output Level= 0
Friction Slope Method= 1
Unsteady Friction Slope Method= 2
Unsteady Bridges Friction Slope Method= 1
Parabolic Critical Depth
Global Vel Dist=  1 , 1 , 1
Global Log Level= 0
CheckData=True
Encroach Param= -1, 0, 0, 0
BEGIN DESCRIPTION:
Multiple Run
END DESCRIPTION:

--- TRIB 7 TO PERDIDO CREEK.f01 (steady flow) ---

Flow Title=Multiple
Number of Profiles=7
Profile Names=10-year,25-year,50-year,1pct_min,100-year,1pct_plu,500-year
River Rch & RM= TRIB 7 TO PERDID,Reach-1,14271
     397     624     825     530    1057    2109    1713
River Rch & RM= TRIB 7 TO PERDID,Reach-1,10568
     826    1351    1832    1202    2399    4786    4067
River Rch & RM= TRIB 7 TO PERDID,Reach-1,5211
    1278    2151    2972    1984    3959    7899    6957
River Rch & RM= TRIB 7 TO PERDID,Reach-1,4681
    1499    2527    3493    2332    4652    9282    8171
Boundary for River Rch & Prof#=TRIB 7 TO PERDID,Reach-1,1
Up Type=0
Dn Type=3
Dn Slope=0.005
Boundary for River Rch & Prof#=TRIB 7 TO PERDID,Reach-1,2
Up Type=0
Dn Type=3
Dn Slope=0.005
Boundary for River Rch & Prof#=TRIB 7 TO PERDID,Reach-1,3
Up Type=0
Dn Type=3
Dn Slope=0.005
Boundary for River Rch & Prof#=TRIB 7 TO PERDID,Reach-1,4
Up Type=0
Dn Type=3
Dn Slope=0.005
Boundary for River Rch & Prof#=TRIB 7 TO PERDID,Reach-1,5
Up Type=0
Dn Type=3
Dn Slope=0.005
Boundary for River Rch & Prof#=TRIB 7 TO PERDID,Reach-1,6
Up Type=0
Dn Type=3
Dn Slope=0.005
Boundary for River Rch & Prof#=TRIB 7 TO PERDID,Reach-1,7
Up Type=0
Dn Type=3
Dn Slope=0.005

--- TRIB 7 TO PERDIDO CREEK.g01 (geometry) ---

Geom Title=Existing Conditions
Program Version=4.10

River Reach=TRIB 7 TO PERDID,Reach-1
Reach XY= 30
        2476325.       13469425.      2476671.39      13469826.5
      2476780.82     13470677.31      2477165.18     13471014.53
      2477823.53     13471128.54      2479026.55     13471921.25
      2480035.08     13472086.09      2480251.27      13472402.7
      2480381.05      13472382.5      2480618.79      13472667.2
      2480949.02     13472697.66      2481073.81      13472985.5
      2481035.18     13473234.71      2481588.24     13473588.61
      2481922.71     13473969.89      2482419.35     13473926.97
      2482511.37     13474111.55      2482709.73     13474174.63
      2482980.85     13473977.06      2483573.52     13473971.39
       2483724.7      13473782.2      2484476.47     13474221.45
      2484640.18     13474225.43      2485145.18     13474074.72
      2485418.98     13474173.39      2485547.67     13473950.96
      2485664.51     13473925.93      2486023.97     13474385.44
      2485828.45     13474773.51        2486075.       13474875.

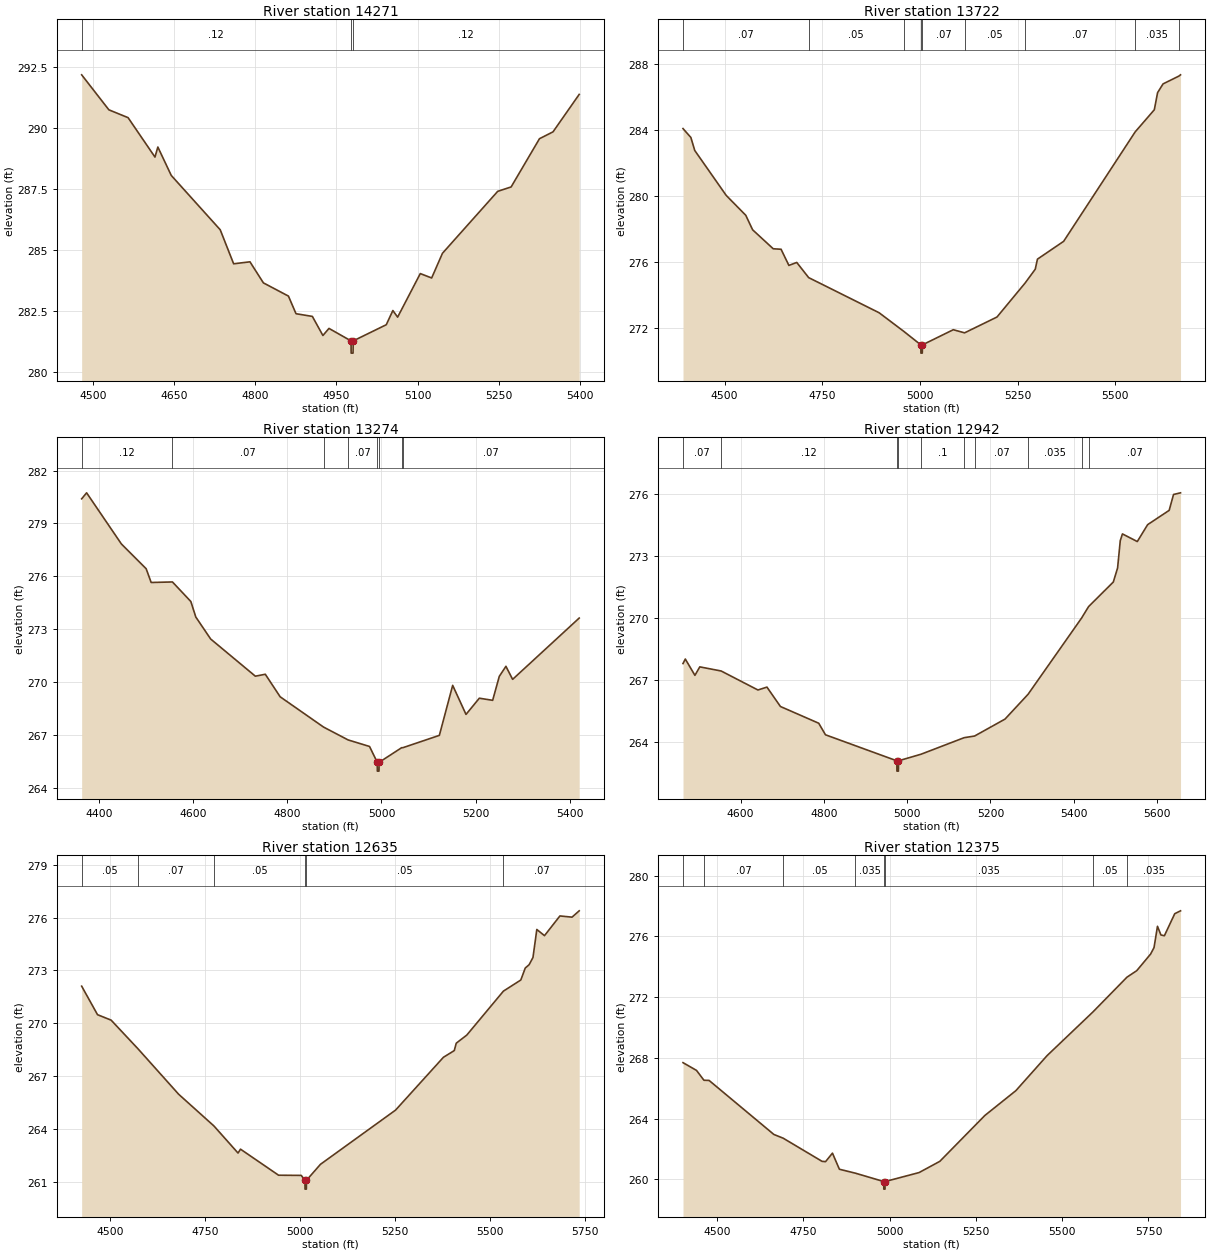
Type RM Length L Ch R = 1 ,14271   ,549,549,549
BEGIN DESCRIPTION:
TRIB 7 TO PERDIDO CREEK 30.0
END DESCRIPTION:
XS GIS Cut Line= 3
      2475867.53     13469689.57      2476354.68     13469505.13
      2476474.99     13469125.02
#Sta/Elev= 30
  4479.1  292.16  4529.4  290.73  4564.9  290.41  4614.6   288.8  4619.9  289.21
  4644.7  288.05  4735.2  285.83    4760  284.44  4790.2  284.52    4815  283.66
  4861.3  283.12  4875.3   282.4  4905.5  282.29    4925  281.51  4936.2   281.8
    4977  281.29  4977.2  280.79  4980.7  280.79    4981  281.29  5042.1  281.95
  5054.3  282.53  5063.1  282.26    5105  284.04    5126  283.86    5146  284.87
  5248.1   287.4  5272.9  287.58  5325.3  289.55  5350.3  289.83  5398.7  291.36
#Mann= 3 ,-1 , 0
  4479.1     .12       0    4977     .05       0    4981     .12       0
Bank Sta=4977,4981
XS Rating Curve= 0 ,0
Exp/Cntr=0.3,0.1

Type RM Length L Ch R = 1 ,13722   ,448,448,448
BEGIN DESCRIPTION:
TRIB 7 TO PERDIDO CREEK 29.0
END DESCRIPTION:
XS GIS Cut Line= 3
      2476074.99       13469875.        2476675.       13469925.
      2477274.99     13469625.01
#Sta/Elev= 30
  4393.7  284.08  4413.8  283.54  4423.8  282.75  4504.1  280.03  4554.3  278.82
  4571.8  277.94  4624.5  276.79  4644.6  276.76  4664.6  275.78  4684.7  275.96
  4715.2  275.04  4895.4  272.91    4958  271.79  5002.2  270.96  5002.4  270.46
  5005.9  270.46  5006.2  270.96  5085.2  271.88  5114.1  271.69    5197  272.65
  5268.9  274.71  5294.9  275.55  5300.5  276.16  5367.5  277.24  5550.6  283.88
  5599.5  285.22  5607.9  286.26  5621.9  286.79  5662.1  287.26  5666.6  287.34
#Mann= 9 ,-1 , 0
  4393.7     .07       0  4715.2     .05       0    4958     .07       0
  5002.2     .05       0  5006.2     .07       0  5114.1     .05       0
  5268.9     .07       0  5550.6    .035       0  5662.1     .07       0
Bank Sta=5002.2,5006.2
XS Rating Curve= 0 ,0
Exp/Cntr=0.3,0.1

Type RM Length L Ch R = 1 ,13274   ,332,332,332
BEGIN DESCRIPTION:
TRIB 7 TO PERDIDO CREEK 28.0
END DESCRIPTION:
XS GIS Cut Line= 3
      2476125.02     13470125.01        2476725.       13470325.
        2477025.       13470025.
#Sta/Elev= 30
  4363.2   280.4  4373.7  280.74  4447.5  277.84  4500.2  276.43  4510.8  275.65
    4556  275.68  4595.1  274.57  4605.6  273.69  4637.2  272.44  4732.1  270.33
  4753.2  270.44  4784.8  269.16    4877  267.44  4929.2  266.71  4974.6  266.34
    4991  265.44  4991.2  264.94  4994.7  264.94    4995  265.44  5042.8  266.27
  5045.4  266.27  5122.9  266.97  5151.2  269.81  5179.5  268.16  5207.8  269.08
  5236.1  268.96  5250.2  270.32  5264.3  270.89  5278.5  270.15  5419.9  273.63
#Mann= 8 ,-1 , 0
  4363.2     .12       0    4556     .07       0    4877     .12       0
  4929.2     .07       0    4991     .05       0    4995     .07       0
  5042.8      .1       0  5045.4     .07       0
Bank Sta=4991,4995
XS Rating Curve= 0 ,0
Exp/Cntr=0.3,0.1

Type RM Length L Ch R = 1 ,12942   ,307,307,307
BEGIN DESCRIPTION:
Mapping XS 0a2db5e5
END DESCRIPTION:
XS GIS Cut Line= 4
      2476268.55      13470823.6      2476751.17     13470625.69
      2477067.15     13470268.05      2477115.38     13470078.55
#Sta/Elev= 30
  4461.9  267.79  4467.4  268.01  4490.5  267.22  4502.2  267.63  4553.5  267.43
  4641.8  266.51  4663.4  266.65  4695.8  265.71  4787.7   264.9  4803.9  264.34
  4975.2  263.08  4975.5  262.58    4979  262.58  4979.2  263.08  5033.5   263.4
  5136.8   264.2  5161.9  264.28  5234.9   265.1  5290.2   266.3  5418.6  269.99
  5435.6  270.55  5494.9  271.74  5505.2  272.42  5511.6  273.74  5516.8  274.07
  5552.5   273.7  5577.4  274.52    5629  275.21  5639.5  275.98  5656.3  276.06
#Mann= 10 ,-1 , 0
  4461.9     .07       0  4553.5     .12       0  4975.2     .05       0
  4979.2     .12       0  5033.5      .1       0  5136.8    .035       0
  5161.9     .07       0  5290.2    .035       0  5418.6     .05       0
  5435.6     .07       0
Bank Sta=4975.2,4979.2
XS Rating Curve= 0 ,0
Exp/Cntr=0.3,0.1

Type RM Length L Ch R = 1 ,12635   ,260,260,260
BEGIN DESCRIPTION:
Mapping XS 8cbe373c
END DESCRIPTION:
XS GIS Cut Line= 4
       2476525.5      13471184.7      2476966.45     13470816.66
      2477108.81     13470323.61      2477143.53      13470104.9
#Sta/Elev= 30
  4425.3   272.1    4467  270.48  4502.8  270.17    4574  268.53  4680.5  265.96
  4773.2  264.16  4836.7  262.62  4843.2  262.84  4943.4  261.36  5003.1  261.35
  5012.7  261.07    5013  260.57  5016.5  260.57  5016.7  261.07  5053.6  261.98
  5251.2  265.06  5377.1  268.06  5405.6  268.44  5410.8  268.86  5438.5  269.32
    5535  271.82  5580.7  272.45  5592.4  273.13  5602.6  273.32  5612.7  273.73
  5622.8  275.32    5643  274.97  5683.6  276.09  5715.4  276.02  5734.3  276.38
#Mann= 6 ,-1 , 0
  4425.3     .05       0    4574     .07       0  4773.2     .05       0
  5012.7     .05       0  5016.7     .05       0    5535     .07       0
Bank Sta=5012.7,5016.7
XS Rating Curve= 0 ,0
Exp/Cntr=0.3,0.1

Type RM Length L Ch R = 1 ,12375   ,139,139,139
BEGIN DESCRIPTION:
Mapping XS 4304a781
END DESCRIPTION:
XS GIS Cut Line= 4
      2476928.26     13471531.94      2477119.23     13471233.33
      2477164.37     13470684.72      2477174.75     13470148.24
#Sta/Elev= 30
  4401.4  267.68  4440.5  267.17  4462.1  266.52  4476.9  266.51  4664.7  262.95
    4692   262.7  4804.3  261.18  4814.4  261.16  4834.4  261.72  4854.5  260.66
  4900.9   260.4    4983  259.85  4983.2  259.35  4986.7  259.35    4987  259.85
  5085.3  260.44  5145.5  261.18  5275.9   264.2    5366  265.84  5456.1  268.14
  5589.1  271.02  5687.7  273.31  5716.1  273.74  5756.1  274.83  5766.1  275.26
  5776.1  276.66  5786.1  276.09  5796.1  276.04  5826.1  277.49  5842.9  277.68
#Mann= 8 ,-1 , 0
  4401.4     .05       0  4462.1     .07       0    4692     .05       0
  4900.9    .035       0    4983    .035       0    4987    .035       0
  5589.1     .05       0  5687.7    .035       0
Bank Sta=4983,4987
XS Rating Curve= 0 ,0
Exp/Cntr=0.3,0.1

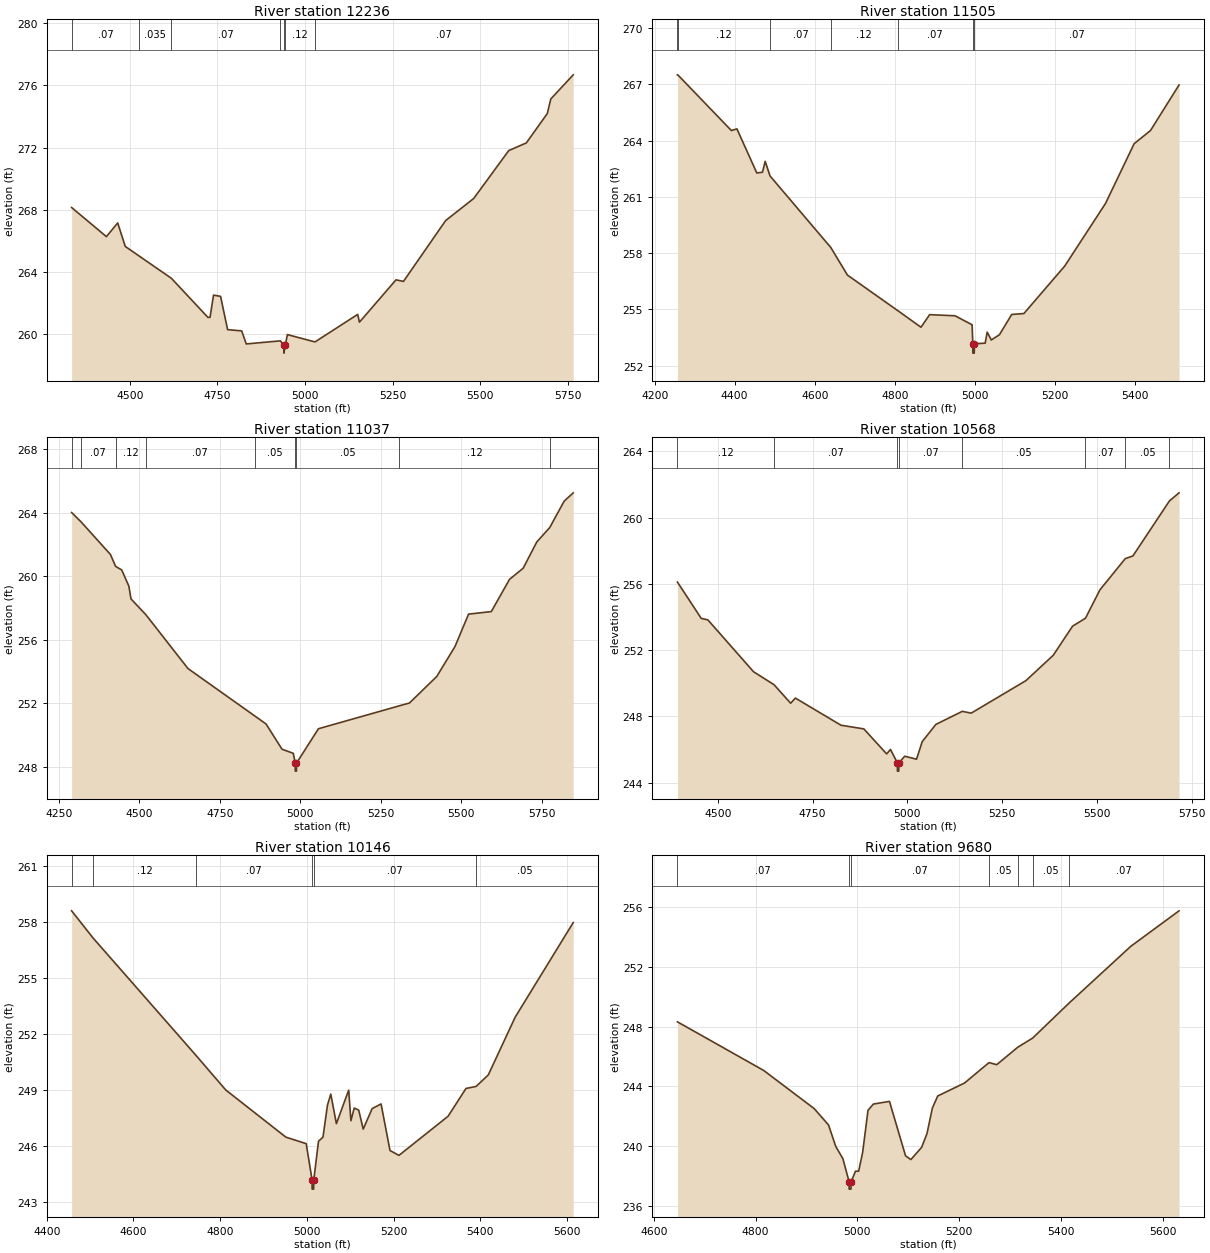
Type RM Length L Ch R = 1 ,12236   ,731,731,731
BEGIN DESCRIPTION:
Mapping XS a2fc841f
END DESCRIPTION:
XS GIS Cut Line= 4
      2477115.76     13471667.37      2477233.81     13471368.75
      2477299.79     13470656.94      2477282.42     13470261.09
#Sta/Elev= 30
  4333.8  268.15  4433.1  266.28  4465.4  267.16  4486.9  265.65  4527.4  265.02
  4618.7   263.6  4722.9  261.09    4729  261.09    4739  262.52  4759.1  262.44
  4779.2   260.3  4819.4  260.22  4832.4  259.38    4930  259.58  4939.8  259.29
    4940  258.79  4943.8  259.29  4949.9  259.98  5028.7  259.51  5150.6  261.28
  5155.6  260.78    5260   263.5  5281.3   263.4  5401.7  267.31  5481.8  268.73
  5581.9  271.81    5632   272.3    5692  274.19    5702  275.13    5766  276.68
#Mann= 7 ,-1 , 0
  4333.8     .07       0  4527.4    .035       0  4618.7     .07       0
    4930     .12       0  4939.8     .05       0  4943.8     .12       0
  5028.7     .07       0
Bank Sta=4939.8,4943.8
XS Rating Curve= 0 ,0
Exp/Cntr=0.3,0.1

Type RM Length L Ch R = 1 ,11505   ,468,468,468
BEGIN DESCRIPTION:
TRIB 7 TO PERDIDO CREEK 24.0
END DESCRIPTION:
XS GIS Cut Line= 3
      2477375.03     13471724.98        2477925.       13471225.
      2477824.99     13470724.97
#Sta/Elev= 30
    4257   267.5  4257.8   267.5  4391.8  264.53  4405.6  264.62  4455.3  262.27
  4469.5  262.31  4476.2  262.89  4488.4  262.11  4640.1   258.3  4681.7  256.83
  4807.1  254.94  4865.5  254.05  4887.1  254.72  4950.6  254.66  4993.2  254.18
  4994.9  253.17  4995.1  252.67  4998.6  252.67  4998.9  253.17  5025.8   253.2
  5030.9  253.79  5041.1  253.37  5061.5  253.65  5092.1  254.73  5122.6  254.78
  5224.6  257.31  5326.6  260.65    5398  263.83  5438.8  264.53  5510.2  266.96
#Mann= 7 ,-1 , 0
    4257     .07       0  4257.8     .12       0  4488.4     .07       0
  4640.1     .12       0  4807.1     .07       0  4994.9     .05       0
  4998.9     .07       0
Bank Sta=4994.9,4998.9
XS Rating Curve= 0 ,0
Exp/Cntr=0.3,0.1

Type RM Length L Ch R = 1 ,11037   ,469,469,469
BEGIN DESCRIPTION:
TRIB 7 TO PERDIDO CREEK 23.0
END DESCRIPTION:
XS GIS Cut Line= 3
      2477774.97     13471875.02        2478325.       13471425.
        2478925.       13470825.
#Sta/Elev= 30
  4289.1  264.02    4318  263.44  4409.7  261.38  4425.7  260.63  4444.9   260.4
  4467.1  259.38  4473.6  258.58    4520  257.58  4650.9  254.19  4858.1  251.21
  4893.5   250.7  4943.1  249.11  4978.2  248.85  4984.1  248.23  4984.4  247.73
  4987.9  247.73  4988.1  248.23  5056.3   250.4  5307.1  251.84  5339.2  252.02
    5424  253.69  5480.6  255.57    5523  257.62  5593.7  257.78  5650.3  259.81
  5692.7  260.51  5735.2  262.17  5775.2  263.07    5820  264.73  5848.3  265.26
#Mann= 9 ,-1 , 0
  4289.1     .12       0    4318     .07       0  4425.7     .12       0
    4520     .07       0  4858.1     .05       0  4984.1     .05       0
  4988.1     .05       0  5307.1     .12       0  5775.2     .07       0
Bank Sta=4984.1,4988.1
XS Rating Curve= 0 ,0
Exp/Cntr=0.3,0.1

Type RM Length L Ch R = 1 ,10568   ,422,422,422
BEGIN DESCRIPTION:
TRIB 7 TO PERDIDO CREEK 22.0
END DESCRIPTION:
XS GIS Cut Line= 3
        2478725.     13472325.04        2478675.       13471725.
      2479074.98     13471125.03
#Sta/Elev= 30
  4393.6   256.1  4456.4  253.91  4473.9  253.82  4594.3  250.69  4648.3  249.91
  4692.2  248.79  4704.7   249.1  4825.1  247.46  4885.3  247.24  4945.5  245.73
  4955.6     246  4973.7  245.19  4973.9  244.69  4977.4  244.69  4977.7  245.19
  4993.2  245.59  5024.3  245.41  5039.3  246.47  5075.3  247.51  5145.1   248.3
  5168.5  248.19  5312.7  250.15  5384.8  251.68  5435.9  253.44    5470  253.92
    5508  255.63    5575  257.52  5595.1  257.68  5691.4     261  5716.8  261.49
#Mann= 8 ,-1 , 0
  4393.6     .12       0  4648.3     .07       0  4973.7     .05       0
  4977.7     .07       0  5145.1     .05       0    5470     .07       0
    5575     .05       0  5691.4     .12       0
Bank Sta=4973.7,4977.7
XS Rating Curve= 0 ,0
Exp/Cntr=0.3,0.1

Type RM Length L Ch R = 1 ,10146   ,466,466,466
BEGIN DESCRIPTION:
TRIB 7 TO PERDIDO CREEK 21.0
END DESCRIPTION:
XS GIS Cut Line= 3
      2478824.99     13472425.03        2479025.       13471925.
        2479175.     13471325.02
#Sta/Elev= 30
  4457.3   258.6  4506.5  257.15    4744  250.85  4812.8  248.99  4951.4  246.46
  4998.4  246.11  5011.9  244.17  5012.1  243.67  5015.6  243.67  5015.9  244.17
  5026.8  246.24  5037.1  246.46  5047.4  248.17  5055.1  248.77    5068  247.18
  5096.4  248.98  5101.5  247.34  5109.2  248.02  5119.5  247.91  5129.9  246.89
  5150.5  247.99  5171.1  248.24  5191.7  245.74  5212.3  245.48  5325.7  247.58
  5366.9  249.07  5390.3  249.18  5418.5   249.8  5480.3  252.89  5614.3  257.97
#Mann= 6 ,-1 , 0
  4457.3     .07       0  4506.5     .12       0    4744     .07       0
  5011.9     .05       0  5015.9     .07       0  5390.3     .05       0
Bank Sta=5011.9,5015.9
XS Rating Curve= 0 ,0
Exp/Cntr=0.3,0.1

Type RM Length L Ch R = 1 ,9680    ,447,447,447
BEGIN DESCRIPTION:
TRIB 7 TO PERDIDO CREEK 20.0
END DESCRIPTION:
XS GIS Cut Line= 3
      2479225.02     13472224.98        2479475.       13471975.
      2479274.99     13471374.98
#Sta/Elev= 30
  4646.4  248.32  4816.1  245.06  4915.1  242.51  4943.4  241.41  4957.5  239.98
  4971.6  239.15  4983.8  237.61    4984  237.11  4987.5  237.11  4987.8  237.61
  4996.4  238.31  5002.6  238.31  5010.5  239.58    5021  242.39  5031.5  242.81
  5063.2  242.99  5094.8  239.34  5105.3  239.09  5126.4  239.91    5137  240.84
  5147.5  242.54    5158  243.35  5210.7  244.22  5258.9  245.59    5274  245.45
  5315.4  246.62  5344.6  247.23  5416.6  249.59  5537.5  253.38  5632.4  255.76
#Mann= 7 ,-1 , 0
  4646.4     .07       0  4983.8     .05       0  4987.8     .07       0
  5258.9     .05       0  5315.4     .07       0  5344.6     .05       0
  5416.6     .07       0
Bank Sta=4983.8,4987.8
XS Rating Curve= 0 ,0
Exp/Cntr=0.3,0.1

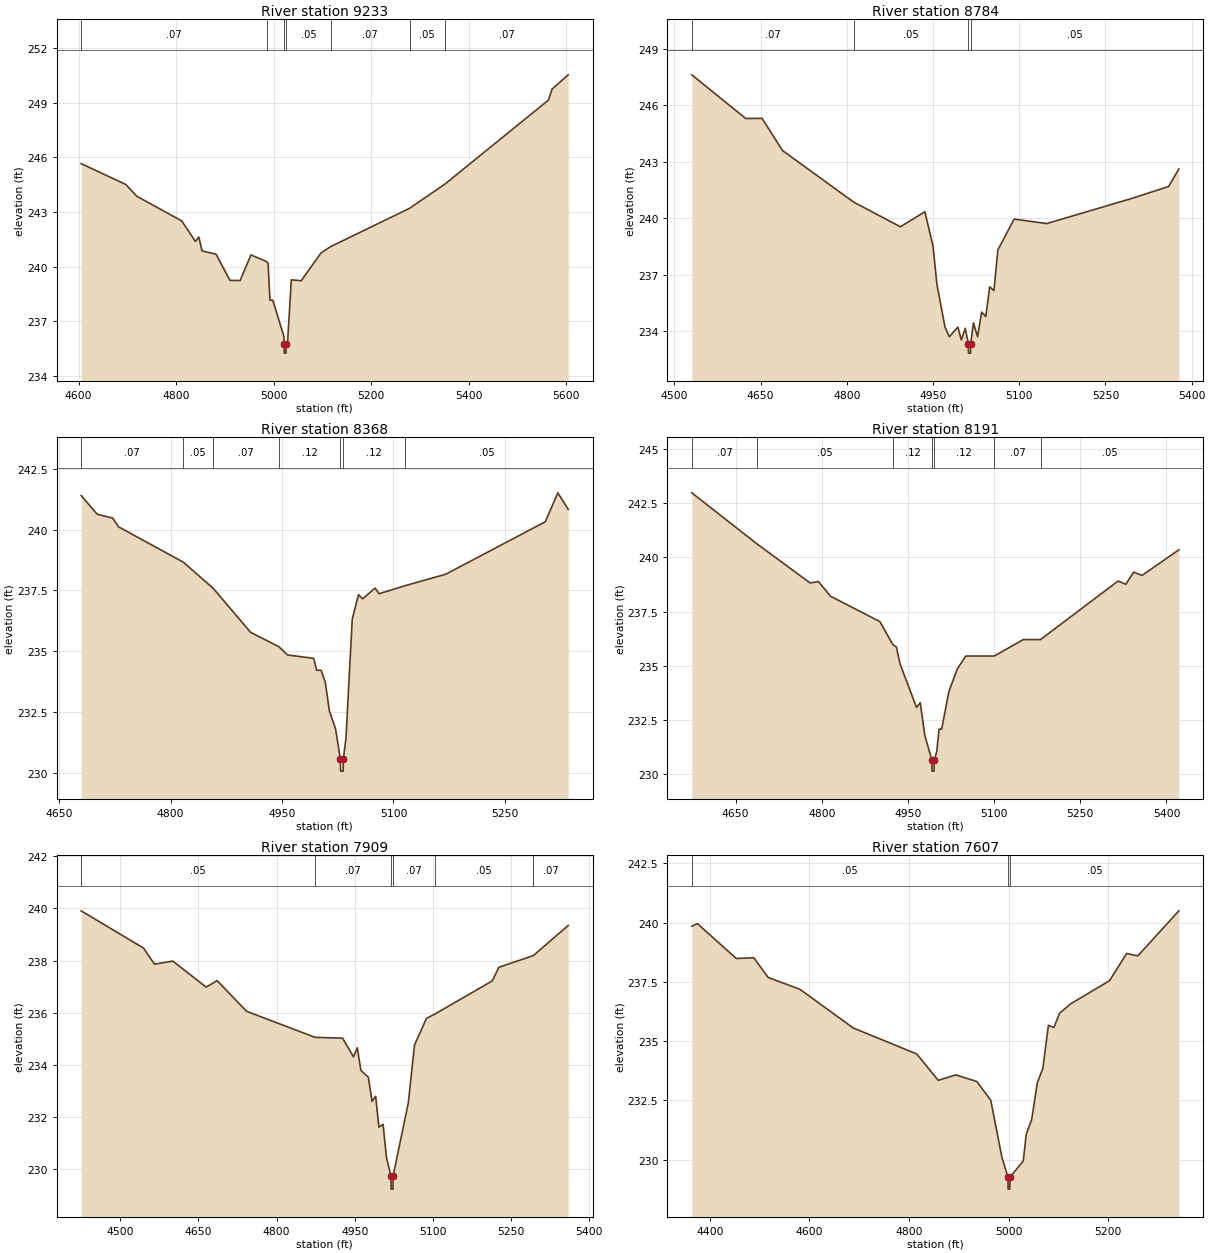
Type RM Length L Ch R = 1 ,9233    ,449,449,449
BEGIN DESCRIPTION:
TRIB 7 TO PERDIDO CREEK 19.0
END DESCRIPTION:
XS GIS Cut Line= 3
      2479625.02     13472424.97        2479875.       13472125.
      2479975.01     13471524.96
#Sta/Elev= 30
  4605.3  245.66    4697  244.51  4719.2  243.87  4811.6  242.51  4839.6  241.38
  4846.7  241.62  4853.2  240.86  4881.9  240.68  4910.5  239.24  4931.3  239.23
  4953.5  240.64  4985.7  240.27  4988.6  240.17  4992.5  238.15  4998.3  238.15
  5021.1  236.16  5021.7  235.74  5021.9  235.24  5025.4  235.24  5025.7  235.74
  5028.7  235.89  5036.3  239.27  5056.6  239.22  5097.2  240.75  5117.2   241.1
  5278.7   243.2  5351.6  244.54  5563.5  249.15  5571.1  249.76  5604.1  250.54
#Mann= 7 ,-1 , 0
  4605.3     .07       0  4985.7     .05       0  5021.7     .05       0
  5025.7     .05       0  5117.2     .07       0  5278.7     .05       0
  5351.6     .07       0
Bank Sta=5021.7,5025.7
XS Rating Curve= 0 ,0
Exp/Cntr=0.3,0.1

Type RM Length L Ch R = 1 ,8784    ,416,416,416
BEGIN DESCRIPTION:
Mapping XS 18e0d0fe
END DESCRIPTION:
XS GIS Cut Line= 3
      2479847.59     13472610.58      2480181.77      13472298.1
      2480446.54     13472011.63
#Sta/Elev= 30
  4530.2  247.62  4624.1   245.3  4652.4  245.31  4688.1   243.6  4811.9  240.86
  4893.3  239.55  4935.8  240.35  4949.9  238.53  4956.8  236.49  4970.9  234.21
  4978.3  233.71  4993.2  234.22  4999.3  233.54  5006.1  234.16  5011.5  233.34
  5011.7  232.84  5015.2  232.84  5015.5  233.34  5020.3  234.45  5027.6  233.71
  5034.5  235.02  5041.8  234.78  5048.6  236.36    5056  236.16  5062.8  238.32
  5091.2  239.96  5147.9  239.72  5296.4  241.06  5359.9  241.69  5377.8  242.62
#Mann= 4 ,-1 , 0
  4530.2     .07       0  4811.9     .05       0  5011.5     .05       0
  5015.5     .05       0
Bank Sta=5011.5,5015.5
XS Rating Curve= 0 ,0
Exp/Cntr=0.3,0.1

Type RM Length L Ch R = 1 ,8368    ,177,177,177
BEGIN DESCRIPTION:
TRIB 7 TO PERDIDO CREEK 17.0
END DESCRIPTION:
XS GIS Cut Line= 3
      2480224.99     13472675.01        2480475.       13472475.
      2480625.01     13472174.98
#Sta/Elev= 30
  4679.6   241.4  4701.2  240.63    4722  240.47    4730  240.11    4817  238.66
  4857.4  237.58  4907.7  235.77  4945.8  235.18  4957.3  234.84  4992.6   234.7
  4996.6  234.21  5002.6  234.21  5008.2  233.72  5013.7  232.54  5022.1  231.79
  5028.5  230.56  5028.8  230.06  5032.3  230.06  5032.5  230.56  5036.1  231.43
  5044.5  236.31  5052.9  237.32  5058.5  237.15  5075.2  237.59  5080.8  237.36
  5115.7  237.69  5170.3  238.16  5304.4  240.32  5321.2  241.51  5335.2  240.83
#Mann= 7 ,-1 , 0
  4679.6     .07       0    4817     .05       0  4857.4     .07       0
  4945.8     .12       0  5028.5     .05       0  5032.5     .12       0
  5115.7     .05       0
Bank Sta=5028.5,5032.5
XS Rating Curve= 0 ,0
Exp/Cntr=0.3,0.1

Type RM Length L Ch R = 1 ,8191    ,282,282,282
BEGIN DESCRIPTION:
Mapping XS 0c453c08
END DESCRIPTION:
XS GIS Cut Line= 3
      2480238.15     13472888.41      2480572.39     13472614.94
      2480819.81     13472280.71
#Sta/Elev= 30
  4573.9  242.98  4687.1  240.63  4779.9  238.82  4794.2  238.89  4815.3  238.21
  4901.2  237.04    4924  235.97  4929.9  235.87  4936.3  235.09    4965  233.08
  4971.5   233.3  4979.4  231.79  4991.8  230.64    4992  230.14  4995.5  230.14
  4995.8  230.64  5000.2  231.04  5004.2  232.08  5008.8  232.08  5021.4  233.82
  5036.1  234.86  5050.7  235.45  5100.2  235.45  5150.9  236.21  5180.8  236.21
  5315.8  238.91  5329.2  238.76  5342.9  239.32  5357.5  239.17  5421.6  240.35
#Mann= 7 ,-1 , 0
  4573.9     .07       0  4687.1     .05       0    4924     .12       0
  4991.8     .05       0  4995.8     .12       0  5100.2     .07       0
  5180.8     .05       0
Bank Sta=4991.8,4995.8
XS Rating Curve= 0 ,0
Exp/Cntr=0.3,0.1

Type RM Length L Ch R = 1 ,7909    ,302,302,302
BEGIN DESCRIPTION:
Mapping XS 2a69a3c5
END DESCRIPTION:
XS GIS Cut Line= 3
       2480433.5     13473092.38      2480828.47     13472675.71
      2480963.02      13472341.5
#Sta/Elev= 30
    4425  239.91  4544.6  238.48  4565.7  237.86  4600.9  237.98  4664.8  236.98
  4685.8  237.23  4742.4  236.05    4874  235.05  4926.5  235.02  4947.5   234.3
  4954.8  234.65  4961.7  233.78  4975.9  233.52  4983.1  232.59    4990  232.79
  4996.2   231.6  5004.2  231.71  5010.7  230.44  5019.4  229.72  5019.7  229.22
  5023.2  229.22  5023.4  229.72  5052.6  232.53  5064.6  234.76  5087.5  235.78
  5104.1  235.95  5213.8  237.22  5226.3  237.74  5292.5  238.19  5359.4  239.35
#Mann= 6 ,-1 , 0
    4425     .05       0    4874     .07       0  5019.4     .05       0
  5023.4     .07       0  5104.1     .05       0  5292.5     .07       0
Bank Sta=5019.4,5023.4
XS Rating Curve= 0 ,0
Exp/Cntr=0.3,0.1

Type RM Length L Ch R = 1 ,7607    ,222,222,222
BEGIN DESCRIPTION:
Mapping XS e20f196c
END DESCRIPTION:
XS GIS Cut Line= 3
      2480511.61     13473257.32      2481010.76     13472849.32
      2481158.31     13472549.88
#Sta/Elev= 30
  4363.7  239.85  4374.9  239.96  4453.1  238.49  4488.3  238.52    4517  237.69
  4580.9  237.19  4687.9  235.56  4815.7  234.46  4858.8  233.35  4893.9  233.58
  4936.4   233.3  4964.3  232.51  4986.5  230.12  4998.9  229.26  4999.1  228.76
  5002.6  228.76  5002.9  229.26  5029.6  229.95  5035.5  231.07  5046.5  231.69
  5057.8  233.24  5068.9  233.85  5080.1  235.67  5091.2  235.58  5102.6  236.18
    5125  236.58  5202.7  237.55  5237.3   238.7  5259.8   238.6  5342.2   240.5
#Mann= 3 ,-1 , 0
  4363.7     .05       0  4998.9     .05       0  5002.9     .05       0
Bank Sta=4998.9,5002.9
XS Rating Curve= 0 ,0
Exp/Cntr=0.3,0.1

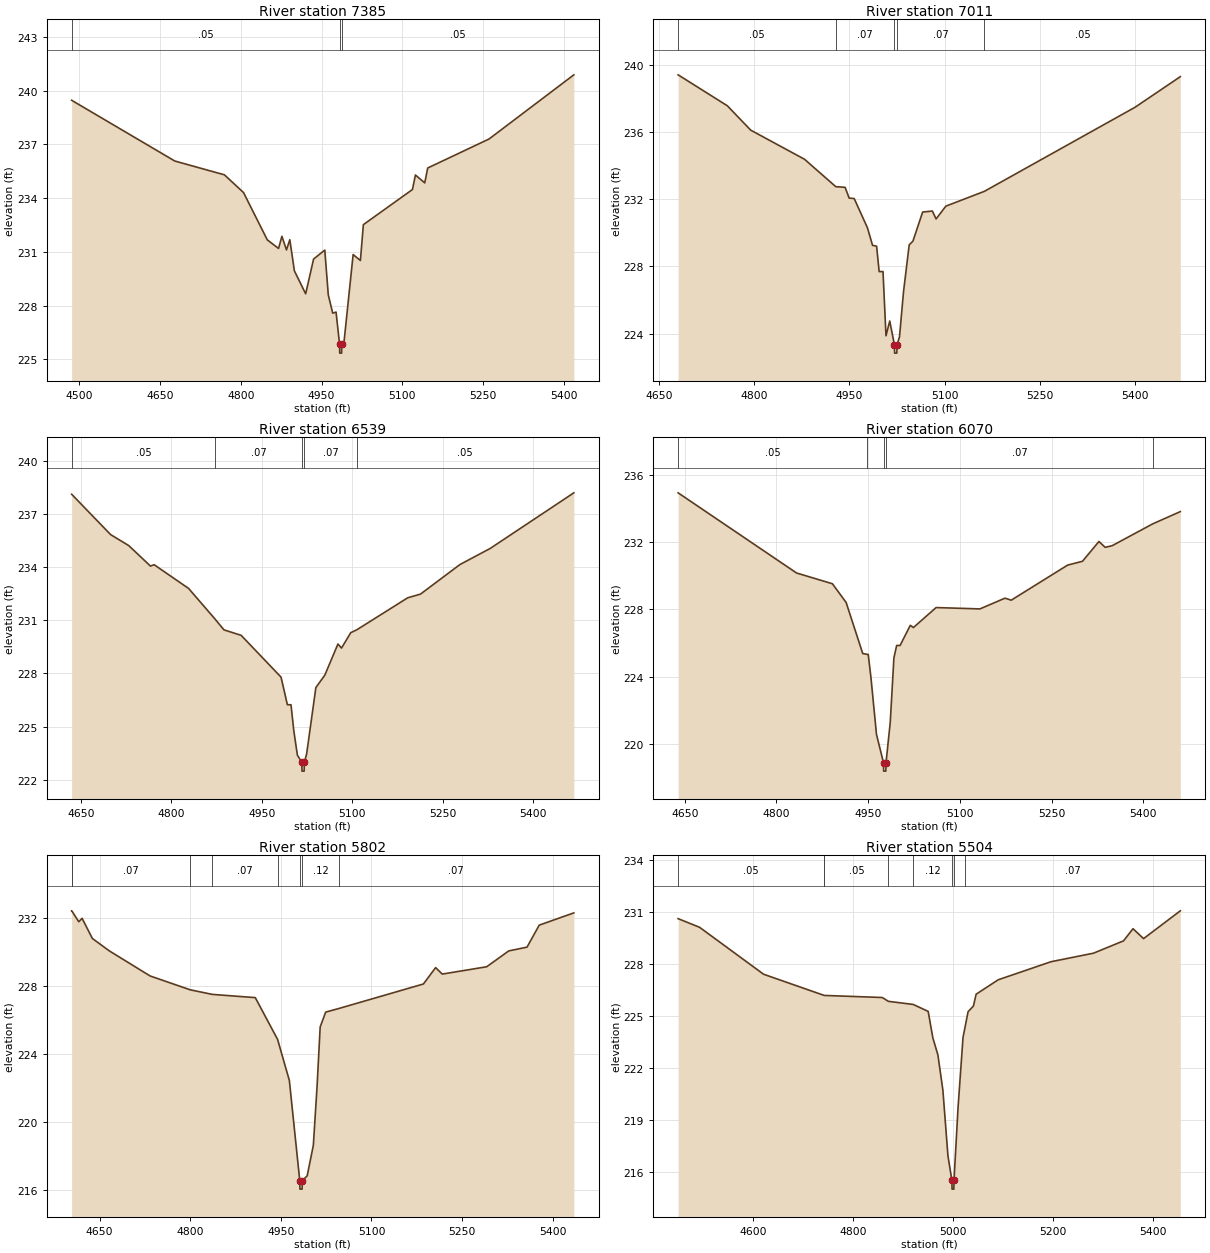
Type RM Length L Ch R = 1 ,7385    ,374,374,374
BEGIN DESCRIPTION:
Mapping XS df17a141
END DESCRIPTION:
XS GIS Cut Line= 3
      2480659.22     13473355.37      2481083.67      13473048.1
      2481257.78     13472679.11
#Sta/Elev= 30
  4486.2  239.46  4677.6  236.07  4769.7   235.3  4805.2  234.31  4849.3  231.67
  4870.2  231.19  4876.4  231.87  4884.9  231.11  4891.1  231.68  4899.6  229.94
  4920.5  228.66  4935.2   230.6    4956   231.1  4962.5   228.6  4970.7  227.58
  4976.9  227.64  4983.4  225.85  4983.7  225.35  4987.2  225.35  4987.4  225.85
  4991.6  225.95  5008.6  230.85  5022.1  230.52  5027.6  232.52  5118.7  234.48
  5124.2  235.29  5141.5  234.85    5147  235.68  5260.9   237.3  5418.2  240.88
#Mann= 3 ,-1 , 0
  4486.2     .05       0  4983.4     .05       0  4987.4     .05       0
Bank Sta=4983.4,4987.4
XS Rating Curve= 0 ,0
Exp/Cntr=0.3,0.1

Type RM Length L Ch R = 1 ,7011    ,472,472,472
BEGIN DESCRIPTION:
TRIB 7 TO PERDIDO CREEK 14.0
END DESCRIPTION:
XS GIS Cut Line= 3
      2480974.99     13473575.01        2481175.       13473325.
      2481425.02     13472924.97
#Sta/Elev= 30
  4679.8  239.39  4757.4  237.55  4794.3   236.1  4879.1  234.37  4928.4  232.74
  4943.1   232.7  4949.5  232.06  4957.5  232.03  4978.4  230.29  4986.4  229.25
  4992.8   229.2  4996.8  227.69  5002.9  227.69  5007.6  223.87  5013.5  224.75
  5020.9  223.34  5021.2  222.84  5024.7  222.84    5025  223.34  5028.9  223.81
  5035.3  226.51  5044.2  229.28  5050.1   229.5  5065.4  231.23  5080.7  231.29
  5086.6  230.82    5102  231.58  5162.7  232.46  5400.3  237.46  5471.7  239.28
#Mann= 5 ,-1 , 0
  4679.8     .05       0  4928.4     .07       0  5020.9     .05       0
    5025     .07       0  5162.7     .05       0
Bank Sta=5020.9,5025
XS Rating Curve= 0 ,0
Exp/Cntr=0.3,0.1

Type RM Length L Ch R = 1 ,6539    ,469,469,469
BEGIN DESCRIPTION:
TRIB 7 TO PERDIDO CREEK 13.0
END DESCRIPTION:
XS GIS Cut Line= 3
      2481225.03     13473774.98        2481525.       13473575.
      2481774.99     13473175.01
#Sta/Elev= 30
  4634.8  238.12  4699.4  235.84  4729.4  235.22  4765.5  234.06  4771.5  234.14
  4828.6   232.8  4872.4  231.07  4887.2  230.46  4915.7  230.15  4981.8  227.79
  4992.3  226.23  4998.3  226.23    5003  224.75  5008.9  223.38  5016.3  222.98
  5016.5  222.48  5020.1  222.48  5020.4  222.98  5024.2  223.45  5039.5   227.2
  5054.3   227.9  5076.1  229.66    5082  229.43  5097.3   230.3  5107.2  230.46
  5191.7  232.27  5212.9  232.48  5278.3  234.15  5328.5  235.06    5467   238.2
#Mann= 5 ,-1 , 0
  4634.8     .05       0  4872.4     .07       0  5016.3     .05       0
  5020.4     .07       0  5107.2     .05       0
Bank Sta=5016.3,5020.4
XS Rating Curve= 0 ,0
Exp/Cntr=0.3,0.1

Type RM Length L Ch R = 1 ,6070    ,268,268,268
BEGIN DESCRIPTION:
TRIB 7 TO PERDIDO CREEK 12.0
END DESCRIPTION:
XS GIS Cut Line= 3
        2481525.       13474075.        2481825.       13473875.
      2481924.99     13473425.03
#Sta/Elev= 30
  4639.2  234.95    4833  230.17  4891.6  229.53  4914.1  228.41  4941.2  225.37
  4948.9  225.32  4950.2  225.31  4954.7  223.92  4963.7  220.55  4975.2  218.86
  4975.4  218.36    4979  218.36  4979.3  218.86  4986.2  221.26  4992.2  225.11
  4996.7  225.85  5002.3  225.85    5019  227.05  5024.1  226.92  5061.2  228.11
  5132.9  228.03  5173.9  228.67  5184.1  228.55  5276.3  230.64  5300.7  230.87
  5327.6  232.05  5337.8   231.7  5349.3   231.8  5415.6   233.1  5460.7  233.83
#Mann= 5 ,-1 , 0
  4639.2     .05       0  4948.9     .07       0  4975.2     .05       0
  4979.3     .07       0  5415.6     .05       0
Bank Sta=4975.2,4979.3
XS Rating Curve= 0 ,0
Exp/Cntr=0.3,0.1

Type RM Length L Ch R = 1 ,5802    ,298,298,298
BEGIN DESCRIPTION:
Mapping XS 14fcc476
END DESCRIPTION:
XS GIS Cut Line= 4
      2481873.61     13474298.09      2482029.86     13473978.66
      2482050.69     13473874.49      2482099.07     13473508.19
#Sta/Elev= 30
  4603.7   232.4  4603.9   232.4  4615.5  231.76    4621  231.96    4638  230.78
  4666.1  230.05  4733.6  228.58  4799.8  227.77  4836.4   227.5  4907.7  227.31
  4944.6  224.86  4964.1  222.45  4981.3  216.58  4981.6  216.08  4985.2  216.08
  4985.5  216.58  4993.6  216.86  5003.8  218.65    5010  222.13  5015.1  225.59
  5024.2  226.46  5045.8  226.67    5186  228.11  5206.2  229.07  5217.2  228.69
  5290.7  229.12  5327.3  230.05  5357.5  230.27  5377.7  231.56    5435  232.28
#Mann= 8 ,-1 , 0
  4603.7     .05       0  4603.9     .07       0  4799.8     .05       0
  4836.4     .07       0  4944.6     .12       0  4981.3     .05       0
  4985.5     .12       0  5045.8     .07       0
Bank Sta=4981.3,4985.5
XS Rating Curve= 0 ,0
Exp/Cntr=0.3,0.1

Type RM Length L Ch R = 1 ,5504    ,293,293,293
BEGIN DESCRIPTION:
Mapping XS 8eb3c179
END DESCRIPTION:
XS GIS Cut Line= 4
      2482012.47     13474381.46      2482300.69     13473978.66
      2482311.11     13473877.96      2482335.41     13473471.72
#Sta/Elev= 30
  4450.7   230.6  4493.7   230.1  4621.5   227.4  4741.6  226.19  4742.8  226.18
  4858.6  226.06  4870.9  225.84  4920.6  225.66  4950.4  225.26  4959.7  223.74
  4969.8  222.76  4979.8  220.72  4989.9  216.95  4997.8  215.53  4998.1  215.03
  5001.7  215.03    5002  215.53    5010  219.69    5020  223.76  5023.7   224.3
  5030.1  225.24  5040.8  225.57  5046.2  226.25  5090.3  227.08  5195.8  228.12
  5280.6  228.61  5340.7  229.32  5359.7  230.02  5380.8  229.45  5454.2  231.05
#Mann= 8 ,-1 , 0
  4450.7     .05       0  4741.6     .07       0  4742.8     .05       0
  4870.9     .07       0  4920.6     .12       0  4997.8     .05       0
    5002     .12       0  5023.7     .07       0
Bank Sta=4997.8,5002
XS Rating Curve= 0 ,0
Exp/Cntr=0.3,0.1

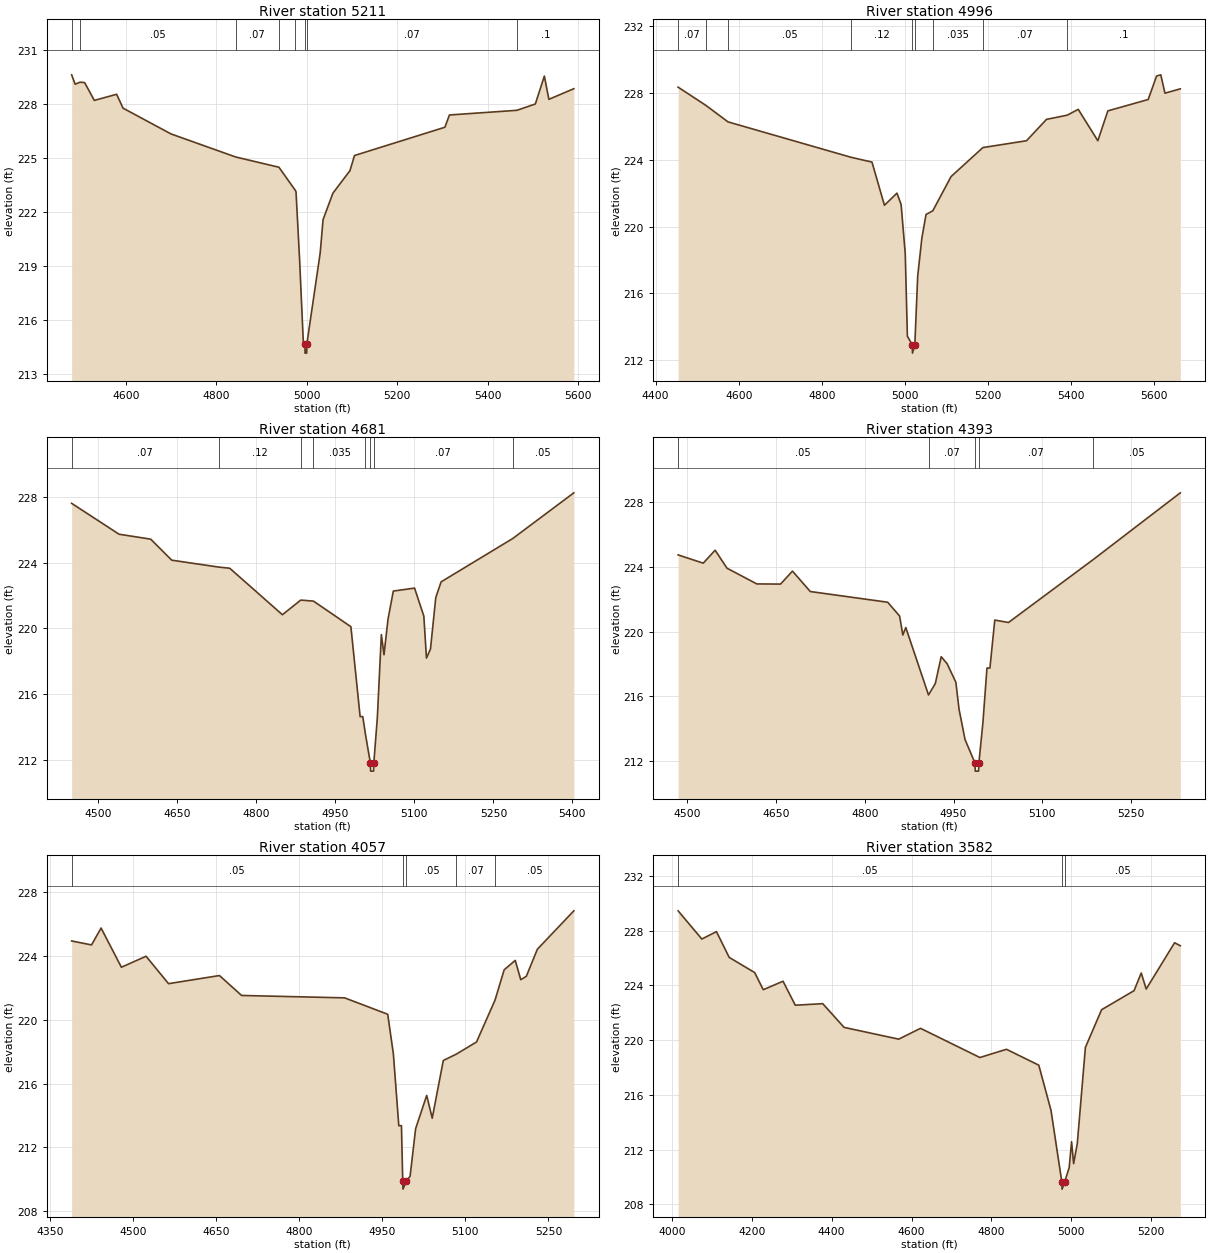
Type RM Length L Ch R = 1 ,5211    ,215,215,215
BEGIN DESCRIPTION:
Mapping XS 0216612e
END DESCRIPTION:
XS GIS Cut Line= 4
      2482116.69     13474447.38      2482456.94     13474127.96
      2482519.44     13474013.38      2482519.44     13473499.79
#Sta/Elev= 30
  4479.9  229.63  4487.6  229.11  4498.4  229.22  4508.6   229.2  4530.1  228.21
  4579.4  228.55  4593.6  227.78  4699.6  226.35  4842.5  225.07  4938.4   224.5
  4974.8  223.21  4976.2  223.13  4984.1  219.37  4992.3  214.81  4995.9  214.68
  4996.1  214.18  4999.8  214.18  5000.1  214.68  5029.7  219.75    5036  221.59
  5057.8  223.06  5095.5  224.31  5105.5  225.15  5305.5  226.72  5315.5   227.4
  5464.7  227.66  5505.5  228.01  5525.5  229.56  5535.5  228.27  5590.7  228.86
#Mann= 8 ,-1 , 0
  4479.9     .07       0  4498.4     .05       0  4842.5     .07       0
  4938.4    .035       0  4974.8     .07       0  4995.9     .05       0
  5000.1     .07       0  5464.7      .1       0
Bank Sta=4995.9,5000.1
XS Rating Curve= 0 ,0
Exp/Cntr=0.3,0.1

Type RM Length L Ch R = 1 ,4996    ,315,315,315
BEGIN DESCRIPTION:
Mapping XS 5a21501e
END DESCRIPTION:
XS GIS Cut Line= 4
      2482658.33     13474721.71      2482665.27     13474169.63
      2482665.27      13474086.3      2482585.63     13473518.41
#Sta/Elev= 30
    4454  228.36  4520.8  227.27  4574.1  226.28  4869.9  224.16  4920.7  223.87
  4950.7  221.28  4980.8  222.01  4990.8  221.33  5000.8  218.38  5005.9  213.43
  5017.7  212.92  5018.2  212.42  5023.8  212.92  5030.8  217.05  5040.8  219.32
  5050.8  220.73  5067.1  220.95    5111     223  5187.7  224.74  5292.7  225.15
  5340.8  226.43  5390.5  226.68  5417.2  227.03  5464.4  225.15  5488.5  226.94
  5585.6  227.62  5605.8  229.03  5615.9   229.1    5626     228  5662.9  228.26
#Mann= 9 ,-1 , 0
    4454     .07       0  4520.8     .12       0  4574.1     .05       0
  4869.9     .12       0  5017.7     .05       0  5023.8     .12       0
  5067.1    .035       0  5187.7     .07       0  5390.5      .1       0
Bank Sta=5017.7,5023.8
XS Rating Curve= 0 ,0
Exp/Cntr=0.3,0.1

Type RM Length L Ch R = 1 ,4681    ,288,288,288
BEGIN DESCRIPTION:
TRIB 7 TO PERDIDO CREEK 9.0
END DESCRIPTION:
XS GIS Cut Line= 3
        2482925.       13474575.        2482925.       13474025.
        2482975.     13473625.01
#Sta/Elev= 30
  4449.6  227.61  4539.6  225.73  4599.6  225.43  4639.6  224.15  4728.6  223.73
  4749.6  223.66  4849.6  220.83  4884.4  221.72  4908.5  221.66  4979.6   220.1
  4997.1  214.63  5002.1  214.63  5007.2  213.56  5016.5  211.81    5017  211.31
  5022.6  211.31  5023.1  211.81  5029.8  214.58  5037.4  219.62  5042.4  218.39
    5050  220.55  5060.1  222.27  5100.4  222.45    5118  220.75    5123  218.19
  5130.6  218.74  5140.7  221.88  5150.8  222.83  5286.8  225.47  5402.7  228.25
#Mann= 8 ,-1 , 0
  4449.6     .07       0  4728.6     .12       0  4884.4     .07       0
  4908.5    .035       0  5007.2     .07       0  5016.5    .035       0
  5023.1     .07       0  5286.8     .05       0
Bank Sta=5016.5,5023.1
XS Rating Curve= 0 ,0
Exp/Cntr=0.3,0.1

Type RM Length L Ch R = 1 ,4393    ,336,336,336
BEGIN DESCRIPTION:
Mapping XS a90c2d77
END DESCRIPTION:
XS GIS Cut Line= 3
      2483137.14     13474487.21      2483196.17     13473966.33
      2483234.37     13473643.39
#Sta/Elev= 30
  4484.2  224.73  4526.7  224.22  4546.8  225.02  4566.9  223.91  4617.3  222.94
  4657.5  222.93  4677.6  223.73  4707.8  222.47  4838.7  221.81  4858.8  220.96
  4864.3  219.79  4869.3  220.25  4907.7  216.09  4919.2  216.79  4929.2  218.45
  4939.3  218.01    4954  216.87  4959.4   215.2  4969.5  213.34  4986.3  211.89
  4986.8  211.39  4992.4  211.39  4992.9  211.89  4999.7  214.37  5006.6  217.75
  5011.6  217.75  5019.8  220.71    5043  220.56  5186.2  224.44  5333.6  228.56
#Mann= 5 ,-1 , 0
  4484.2     .05       0  4907.7     .07       0  4986.3     .05       0
  4992.9     .07       0  5186.2     .05       0
Bank Sta=4986.3,4992.9
XS Rating Curve= 0 ,0
Exp/Cntr=0.3,0.1

Type RM Length L Ch R = 1 ,4057    ,475,475,475
BEGIN DESCRIPTION:
Mapping XS f79b310f
END DESCRIPTION:
XS GIS Cut Line= 3
       2483394.1     13474577.42      2483498.26     13473990.64
      2483498.26      13473679.1
#Sta/Elev= 30
  4388.5  224.95  4424.4   224.7  4441.7  225.76  4478.4   223.3    4523  223.99
  4563.6  222.27  4655.6  222.78  4695.6  221.53  4881.8  221.38  4959.7  220.35
  4969.9  217.86  4979.7  213.36  4984.5  213.36  4986.8  209.88  4987.3  209.38
  4993.4  209.88  5000.1  210.19  5010.1  213.17  5030.1  215.26  5040.1  213.83
  5060.1  217.45  5083.7  217.85  5120.1  218.61  5153.5  221.23  5170.1  223.14
  5190.1  223.73  5200.1  222.52  5210.1  222.73  5230.1  224.43    5296  226.84
#Mann= 5 ,-1 , 0
  4388.5     .05       0  4986.8     .05       0  4993.4     .05       0
  5083.7     .07       0  5153.5     .05       0
Bank Sta=4986.8,4993.4
XS Rating Curve= 0 ,0
Exp/Cntr=0.3,0.1

Type RM Length L Ch R = 1 ,3582    ,268,268,268
BEGIN DESCRIPTION:
Mapping XS b24831a8
END DESCRIPTION:
XS GIS Cut Line= 3
      2483519.39     13474775.18      2483852.42     13473862.16
      2483803.81     13473580.89
#Sta/Elev= 30
  4015.6  229.44    4075  227.38  4111.6  227.92  4143.5  226.04  4207.4  224.93
  4228.7  223.68  4278.3   224.3  4308.9  222.55  4377.7  222.66  4431.1  220.93
  4567.9  220.07  4622.5  220.86  4771.2  218.73  4837.6  219.33  4918.6  218.17
  4949.2  214.87  4976.4  209.62  4976.9  209.12  4983.1  209.62  4994.7  210.69
  5000.7  212.58  5005.8  210.98    5015  212.44  5035.3  219.47  5075.9  222.22
  5157.1  223.61  5175.1   224.9  5187.5  223.73  5258.6  227.11  5272.9  226.89
#Mann= 3 ,-1 , 0
  4015.6     .05       0  4976.4     .05       0  4983.1     .05       0
Bank Sta=4976.4,4983.1
XS Rating Curve= 0 ,0
Exp/Cntr=0.3,0.1