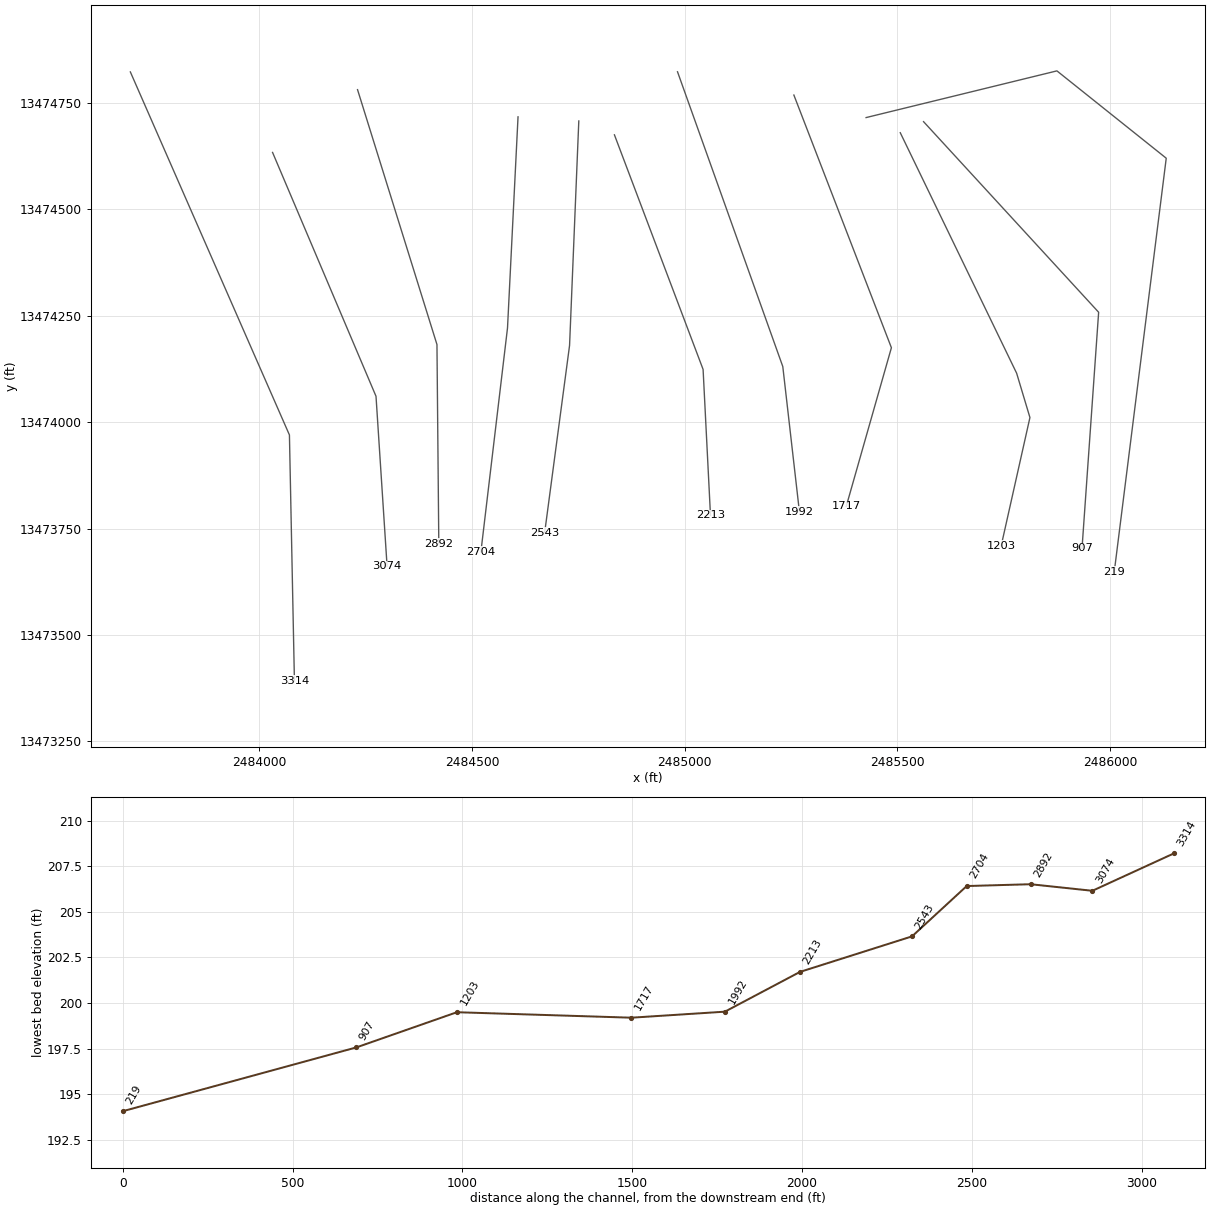
HEC-RAS study TRIB 7 TO PERDIDO CREEK.prj: TRIB 7 TO PERDIDO CREEK Base Level Engineering

--- TRIB 7 TO PERDIDO CREEK.g01 (geometry) --- (continued)

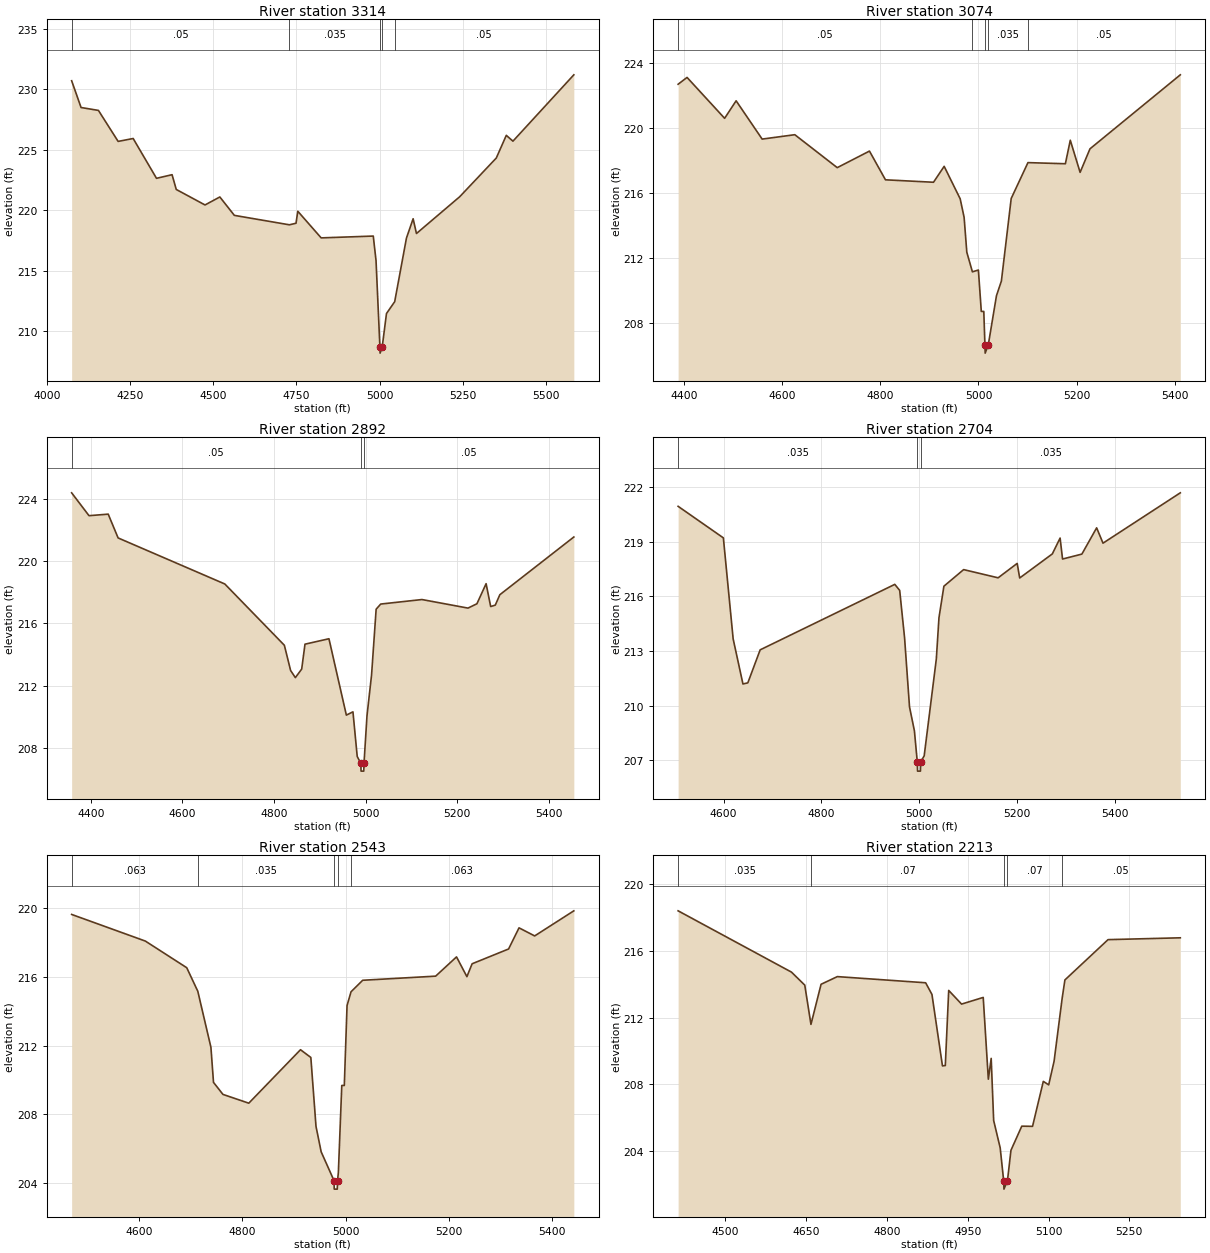
Type RM Length L Ch R = 1 ,3314    ,240,240,240
BEGIN DESCRIPTION:
Mapping XS e1b5bdc1
END DESCRIPTION:
XS GIS Cut Line= 3
      2483697.34     13474822.92      2484071.17      13473969.8
       2484082.9     13473392.05
#Sta/Elev= 30
  4074.3   230.7  4102.6  228.49  4154.8  228.25    4214  225.69  4259.2  225.93
  4329.3  222.64  4376.1  222.94  4388.7  221.72  4475.1  220.44  4519.7   221.1
  4563.3  219.58  4728.8   218.8  4748.6  218.93    4754  219.92  4824.2  217.72
  4980.8  217.87  4989.1  215.85  5000.8   208.7  5001.3   208.2  5007.6   208.7
  5020.5  211.47  5045.2  212.45  5080.5   217.7  5100.6   219.3  5110.6  218.08
  5240.6  221.12  5350.6  224.32  5380.6  226.19  5400.6  225.71  5583.6  231.19
#Mann= 5 ,-1 , 0
  4074.3     .05       0  4728.8    .035       0  5000.8    .035       0
  5007.6    .035       0  5045.2     .05       0
Bank Sta=5000.8,5007.6
XS Rating Curve= 0 ,0
Exp/Cntr=0.3,0.1

Type RM Length L Ch R = 1 ,3074    ,182,182,182
BEGIN DESCRIPTION:
Mapping XS ea9970b5
END DESCRIPTION:
XS GIS Cut Line= 3
      2484031.55     13474633.69      2484274.61     13474060.76
      2484300.65     13473661.46
#Sta/Elev= 30
  4388.4  222.72  4406.6  223.14  4483.1  220.62  4506.5   221.7  4559.5  219.34
    4626  219.61  4712.4  217.58    4778   218.6  4810.6  216.83  4908.4  216.68
  4930.1  217.66  4962.7  215.66  4970.7  214.52  4976.2  212.37  4987.6  211.16
  4999.8  211.27  5005.7  208.72  5010.8  208.72  5013.1  206.65  5013.6  206.15
  5019.9  206.65  5036.6  209.69  5046.6  210.59  5066.6  215.68  5100.7  217.89
  5176.9  217.82  5186.9  219.27  5206.9  217.29    5227  218.74  5410.9   223.3
#Mann= 5 ,-1 , 0
  4388.4     .05       0  4987.6    .035       0  5013.1    .035       0
  5019.9    .035       0  5100.7     .05       0
Bank Sta=5013.1,5019.9
XS Rating Curve= 0 ,0
Exp/Cntr=0.3,0.1

Type RM Length L Ch R = 1 ,2892    ,188,188,188
BEGIN DESCRIPTION:
Mapping XS d22fd848
END DESCRIPTION:
XS GIS Cut Line= 3
      2484231.22     13474781.22      2484417.84     13474182.29
      2484422.18     13473713.54
#Sta/Elev= 30
  4358.2   224.4  4396.1  222.93    4438  223.03  4459.6   221.5  4692.5  218.54
  4822.5   214.6  4836.1  212.98  4846.5  212.52  4860.3  213.07  4867.5  214.67
  4919.8  215.02  4957.8  210.11  4972.2  210.32  4981.5  207.45  4989.4  207.01
  4989.9  206.51  4995.8  206.51  4996.3  207.01  5002.8  210.06  5012.8  212.69
  5022.8  216.92  5032.8  217.25  5122.8  217.54  5223.3  216.99  5242.8  217.27
  5262.8  218.56  5272.8  217.09  5282.8  217.18  5292.8  217.85  5454.3  221.56
#Mann= 3 ,-1 , 0
  4358.2     .05       0  4989.4     .05       0  4996.3     .05       0
Bank Sta=4989.4,4996.3
XS Rating Curve= 0 ,0
Exp/Cntr=0.3,0.1

Type RM Length L Ch R = 1 ,2704    ,161,161,161
BEGIN DESCRIPTION:
Mapping XS b65d34c1
END DESCRIPTION:
XS GIS Cut Line= 3
      2484608.36     13474717.36      2484583.62     13474221.25
      2484521.11     13473695.18
#Sta/Elev= 30
  4507.2  220.93  4599.7   219.2  4619.7  213.66  4639.7  211.19  4649.7  211.25
  4674.9  213.06  4950.1  216.65  4960.1  216.32  4970.1  213.72  4980.2  209.93
  4990.2  208.62  4996.1  206.91  4996.6  206.41  5002.5  206.41    5003  206.91
  5010.2  207.25    5035  212.56  5040.4  214.82  5050.5  216.55  5090.8  217.46
  5161.3  217.01  5200.3   217.8  5205.4     217  5272.1  218.32    5288  219.19
    5293  218.04  5332.5  218.31  5362.7  219.75  5375.7  218.91  5533.7  221.67
#Mann= 3 ,-1 , 0
  4507.2    .035       0  4996.1    .035       0    5003    .035       0
Bank Sta=4996.1,5003
XS Rating Curve= 0 ,0
Exp/Cntr=0.3,0.1

Type RM Length L Ch R = 1 ,2543    ,330,330,330
BEGIN DESCRIPTION:
Mapping XS 27b340fb
END DESCRIPTION:
XS GIS Cut Line= 3
      2484751.15     13474707.62      2484729.45     13474180.23
      2484670.88     13473739.85
#Sta/Elev= 30
  4469.8  219.63  4612.5  218.08  4692.6  216.53    4714  215.16  4739.4   211.9
  4744.4  209.86  4762.7  209.16  4812.7  208.65  4912.8  211.76  4932.8  211.31
  4942.8   207.3  4952.8  205.82  4977.6  204.15  4978.1  203.65    4984  203.65
  4984.5  204.15  4986.1  204.62  4992.7  209.68  4997.6  209.68  5002.9  214.33
  5010.6  215.13  5033.2   215.8  5174.4  216.04  5214.8  217.16  5234.9  216.01
    5245  216.76  5315.6  217.62  5335.8  218.85  5366.1  218.38  5441.9  219.84
#Mann= 5 ,-1 , 0
  4469.8    .063       0    4714    .035       0  4977.6    .035       0
  4984.5    .035       0  5010.6    .063       0
Bank Sta=4977.6,4984.5
XS Rating Curve= 0 ,0
Exp/Cntr=0.3,0.1

Type RM Length L Ch R = 1 ,2213    ,221,221,221
BEGIN DESCRIPTION:
Mapping XS f011a978
END DESCRIPTION:
XS GIS Cut Line= 3
      2484834.88     13474675.03      2485043.22     13474123.81
      2485060.58     13473780.93
#Sta/Elev= 30
  4412.1  218.41  4622.6  214.73  4647.3  213.95  4658.8  211.59  4677.6     214
  4707.8  214.46  4871.8  214.09  4883.5  213.39    4903   209.1  4908.3  209.12
  4914.6  213.63  4938.5  212.81  4978.7  213.21  4988.2   208.3  4993.5  209.55
  4998.1  205.82  5010.2  204.18  5016.7   202.2  5017.2   201.7  5023.7   202.2
  5030.2  204.03  5050.3  205.48  5070.3  205.47  5090.3  208.17  5100.3  207.96
  5110.3  209.38  5125.3  213.16  5130.4  214.26  5210.5  216.68  5344.7  216.79
#Mann= 5 ,-1 , 0
  4412.1    .035       0  4658.8     .07       0  5016.7     .05       0
  5023.7     .07       0  5125.3     .05       0
Bank Sta=5016.7,5023.7
XS Rating Curve= 0 ,0
Exp/Cntr=0.3,0.1

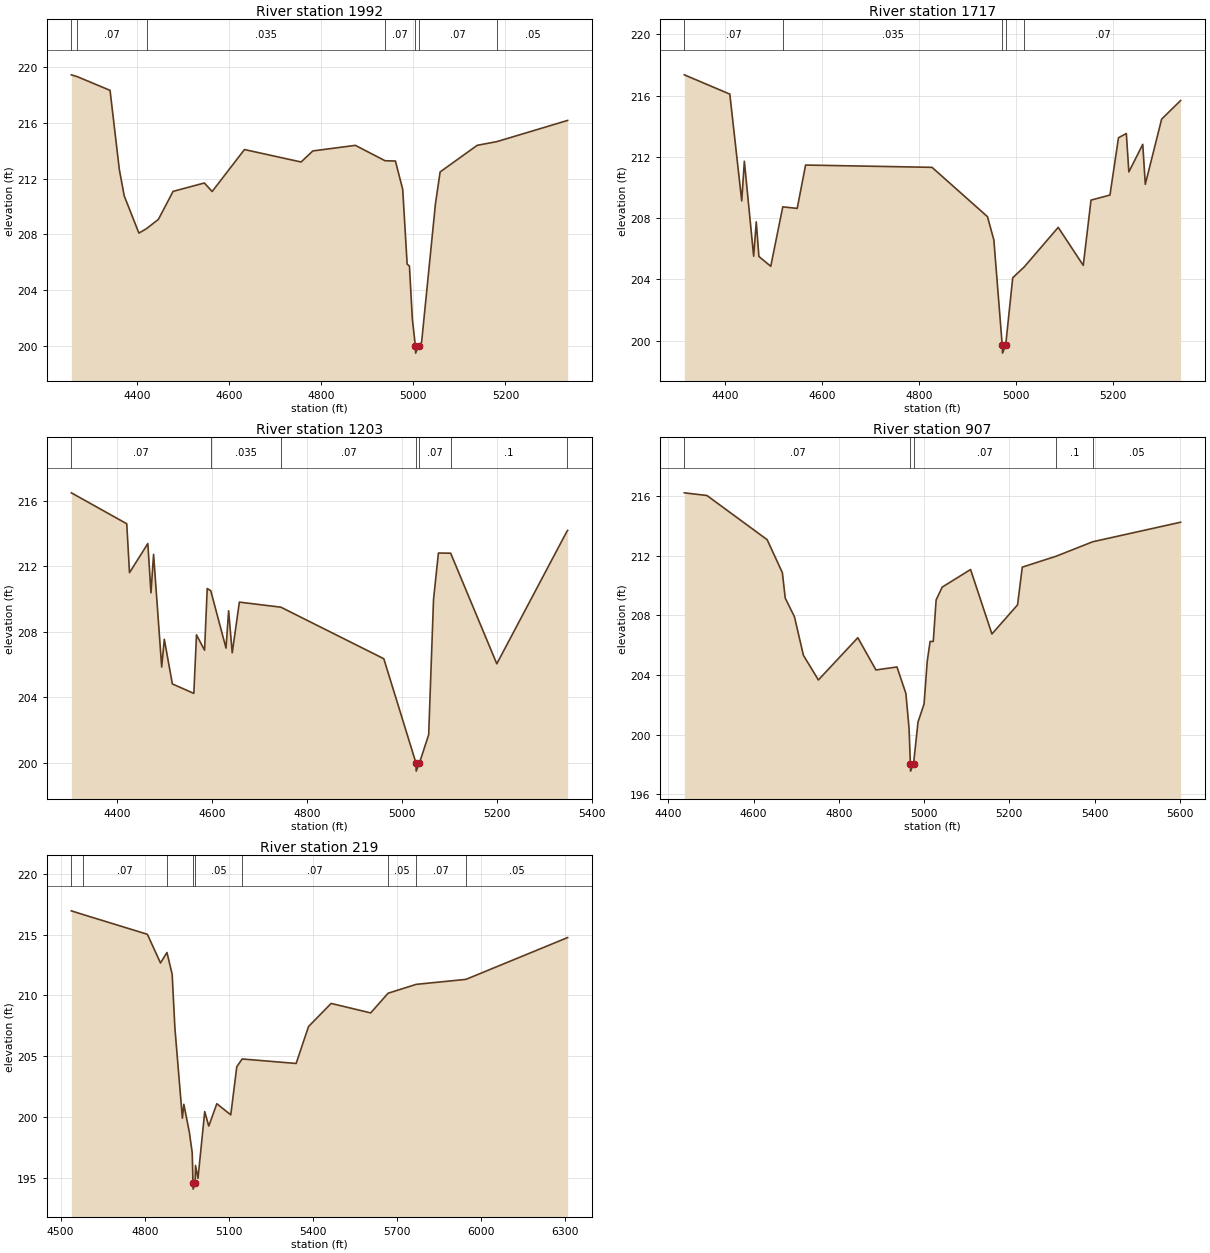
Type RM Length L Ch R = 1 ,1992    ,275,275,275
BEGIN DESCRIPTION:
Mapping XS 9e46e42f
END DESCRIPTION:
XS GIS Cut Line= 3
      2484983.11     13474823.22       2485230.5     13474130.54
      2485269.53     13473789.69
#Sta/Elev= 30
  4256.6  219.41  4269.4  219.28  4340.7   218.3  4360.9  212.64  4371.5  210.76
  4403.4   208.1  4420.1  208.42  4445.8  209.08  4477.7  211.08  4545.7  211.68
  4562.6  211.07  4632.8  214.07  4755.9  213.18  4781.4  213.97  4873.8  214.37
  4938.4  213.27  4960.9  213.25  4976.8  211.22  4986.4  205.88  4991.4  205.74
  4997.7  201.97  5004.3  200.02  5004.8  199.52  5011.3  200.02  5017.8  200.29
    5048  210.22  5058.1  212.47  5138.6  214.37  5181.7  214.64  5335.2  216.15
#Mann= 7 ,-1 , 0
  4256.6    .035       0  4269.4     .07       0  4420.1    .035       0
  4938.4     .07       0  5004.3     .05       0  5011.3     .07       0
  5181.7     .05       0
Bank Sta=5004.3,5011.3
XS Rating Curve= 0 ,0
Exp/Cntr=0.3,0.1

Type RM Length L Ch R = 1 ,1717    ,514,514,514
BEGIN DESCRIPTION:
Mapping XS d649fe07
END DESCRIPTION:
XS GIS Cut Line= 3
      2485256.55     13474768.53      2485485.71     13474174.81
      2485379.49     13473801.75
#Sta/Elev= 30
  4315.2  217.36  4409.1   216.1  4433.7  209.13  4439.1  211.72  4458.3  205.52
  4463.7  207.76  4469.1   205.5  4493.6  204.86  4518.4  208.74  4548.2  208.64
  4565.5  211.47  4826.4  211.32  4940.9   208.1  4954.1  206.57  4971.4  199.69
  4971.9  199.19  4978.4  199.69    4993  204.11  5016.8  204.82  5086.9   207.4
  5138.6  204.92  5154.6  209.18  5193.7  209.51  5211.3  213.25  5227.5  213.53
  5232.7  211.02  5261.4  212.82  5266.6  210.21  5300.4  214.47  5339.5  215.68
#Mann= 5 ,-1 , 0
  4315.2     .07       0  4518.4    .035       0  4971.4    .035       0
  4978.4    .035       0  5016.8     .07       0
Bank Sta=4971.4,4978.4
XS Rating Curve= 0 ,0
Exp/Cntr=0.3,0.1

Type RM Length L Ch R = 1 ,1203    ,296,296,296
BEGIN DESCRIPTION:
Mapping XS b78cac1c
END DESCRIPTION:
XS GIS Cut Line= 4
      2485506.54     13474680.03      2485779.98     13474114.91
      2485811.23     13474010.75      2485743.68     13473709.37
#Sta/Elev= 30
  4303.9   216.5  4420.6  214.61  4426.4  211.62    4465   213.4  4471.6  210.39
  4477.1  212.74  4494.2  205.85  4499.7  207.55  4516.7  204.82  4561.9  204.24
  4567.5  207.82  4584.5  206.88  4590.1  210.65  4597.5  210.52  4629.7  207.01
  4635.2  209.29  4642.8  206.72  4657.8  209.82  4745.3  209.51  4962.1  206.36
  5029.8  199.99  5030.3  199.49  5037.2  199.99  5056.6  201.72  5066.8  209.97
  5077.1  212.82  5102.9  212.81  5200.1  206.05  5347.9  214.15  5349.3   214.2
#Mann= 7 ,-1 , 0
  4303.9     .07       0  4597.5    .035       0  4745.3     .07       0
  5029.8     .05       0  5037.2     .07       0  5102.9      .1       0
  5347.9     .05       0
Bank Sta=5029.8,5037.2
XS Rating Curve= 0 ,0
Exp/Cntr=0.3,0.1

Type RM Length L Ch R = 1 ,907     ,688,688,688
BEGIN DESCRIPTION:
Mapping XS d834a86c
END DESCRIPTION:
XS GIS Cut Line= 3
      2485561.26     13474706.02      2485972.69     13474258.14
      2485933.63     13473703.48
#Sta/Elev= 30
  4437.6  216.21  4490.7  216.03  4631.9  213.07  4667.6  210.86  4674.4  209.15
    4696   207.9    4717  205.32  4752.1  203.67  4844.6   206.5  4887.1  204.34
  4936.5  204.54  4957.4  202.76  4964.8  200.42  4967.9  198.06  4968.4  197.56
  4975.4  198.06  4985.8  200.85    5000  202.06  5007.4  204.91  5014.2  206.25
  5021.6  206.25  5028.3  209.03  5042.5  209.89  5109.1  211.07  5159.2  206.75
  5219.3   208.7  5230.4  211.23  5309.7  211.96  5395.6  212.93  5601.8  214.24
#Mann= 5 ,-1 , 0
  4437.6     .07       0  4967.9     .05       0  4975.4     .07       0
  5309.7      .1       0  5395.6     .05       0
Bank Sta=4967.9,4975.4
XS Rating Curve= 0 ,0
Exp/Cntr=0.3,0.1

Type RM Length L Ch R = 1 ,219     ,0,0,0
BEGIN DESCRIPTION:
Mapping XS 1c5471ed
END DESCRIPTION:
XS GIS Cut Line= 4
      2485426.28     13474715.62      2485874.65     13474825.34
      2486131.54     13474620.12      2486009.38     13473648.07
#Sta/Elev= 30
  4538.4  216.96  4579.3  216.66  4809.6  215.03  4856.3  212.67  4879.4  213.53
    4898  211.73  4907.7  207.32  4934.4   199.9  4939.6  201.04  4959.2  198.75
  4969.5  197.06  4972.3  194.56  4972.8  194.06  4979.8  194.56  4981.2  196.01
  4990.1  194.95  5014.1  200.44  5028.5  199.25  5057.3  201.09    5107  200.17
  5128.4  204.13  5147.6  204.77  5340.1   204.4  5384.4  207.44    5465  209.34
  5606.1  208.56  5668.1  210.18  5768.5  210.91  5945.9  211.32  6308.5  214.76
#Mann= 9 ,-1 , 0
  4538.4     .05       0  4579.3     .07       0  4879.4     .05       0
  4972.3     .05       0  4979.8     .05       0  5147.6     .07       0
  5668.1     .05       0  5768.5     .07       0  5945.9     .05       0
Bank Sta=4972.3,4979.8
XS Rating Curve= 0 ,0
Exp/Cntr=0.3,0.1

Chan Stop Cuts=-1
Use User Specified Reach Order=0
Composite Channel Slope=5