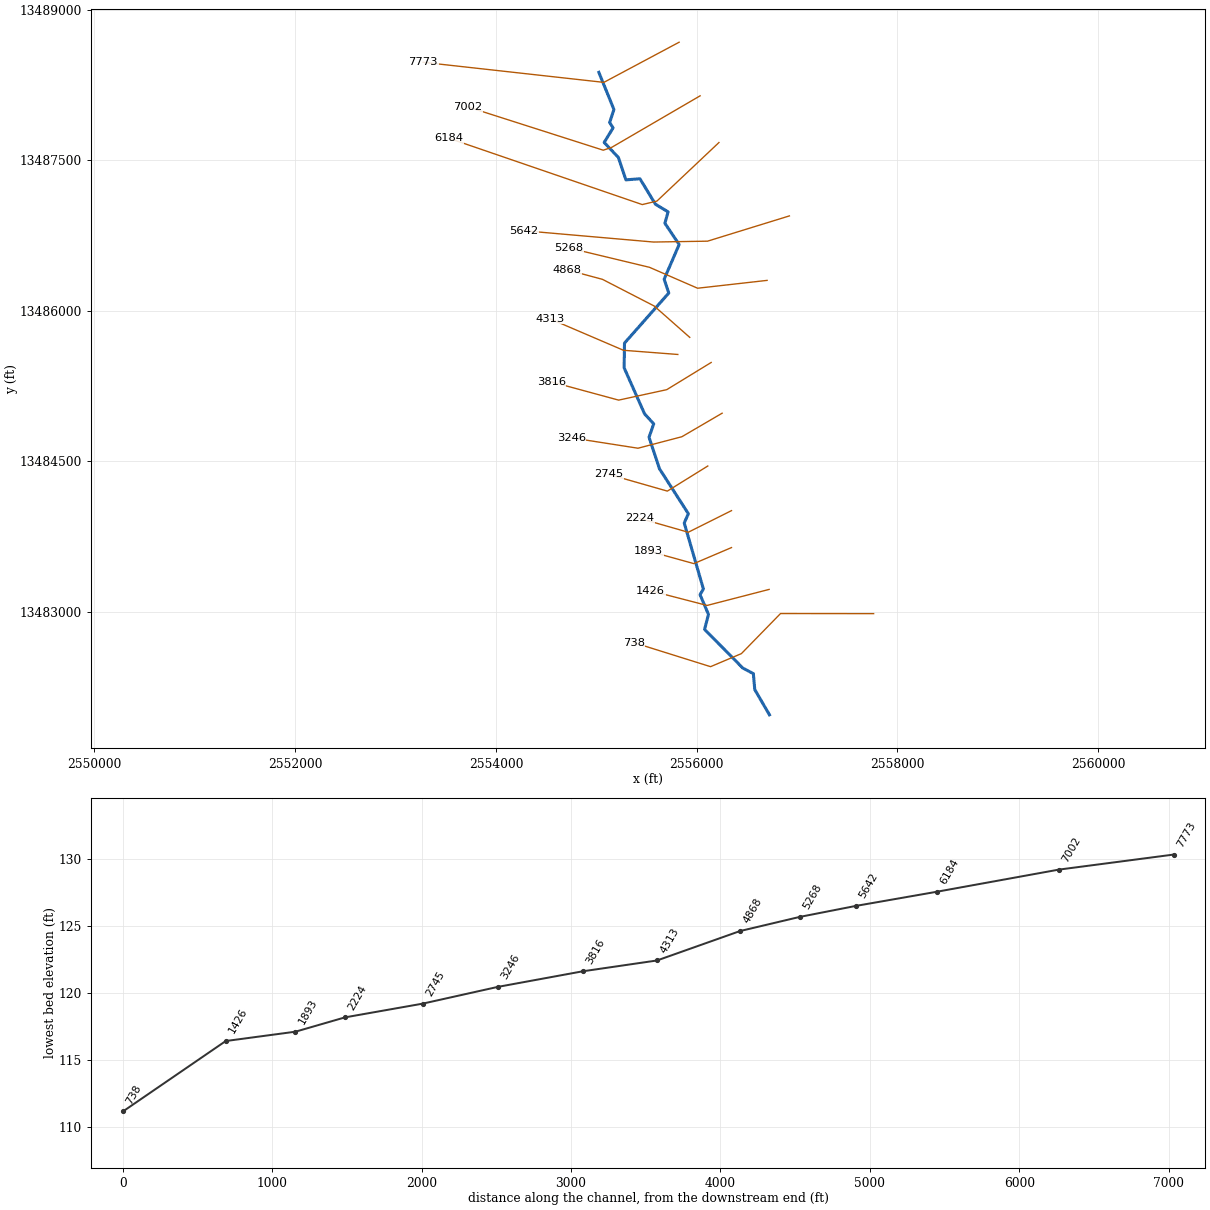
--- TRIB 7_1 TO COLETO CREEK RSVR.prj (project) ---

Proj Title=TRIB 7_1 TO COLETO CREEK RSVR Base Level Engineering
Current Plan=p01
Default Exp/Contr=0.3,0.1
English Units
Geom File=g01
Flow File=f01
Plan File=p01
Y Axis Title=Elevation
X Axis Title(PF)=Main Channel Distance
X Axis Title(XS)=Station
BEGIN DESCRIPTION:
TRIB 7_1 TO COLETO CREEK RSVR
END DESCRIPTION:
DSS Export Rating Curves= 0
DSS Export Rating Curve Sorted= 0
DSS Export Volume Flow Curves= 0
DXF OffsetX= 0
DXF OffsetY= 0
DXF ScaleX= 1
DXF ScaleY= 10

--- TRIB 7_1 TO COLETO CREEK RSVR.p01 (plan) ---

Plan Title=Multiple Run
Short Identifier=Multiple
Geom File=g01
Flow File=f01
Subcritical Flow
K Sum by GR= 0
Std Step Tol= 0.01
Critical Tol= 0.01
Num of Std Step Trials= 20
Max Error Tol= 0.3
Flow Tol Ratio= 0.001
Split Flow NTrial= 30
Split Flow Tol= 0.02
Split Flow Ratio= 0.02
Log Output Level= 0
Friction Slope Method= 1
Unsteady Friction Slope Method= 2
Unsteady Bridges Friction Slope Method= 1
Parabolic Critical Depth
Global Vel Dist=  1 , 1 , 1
Global Log Level= 0
CheckData=True
Encroach Param= -1, 0, 0, 0
BEGIN DESCRIPTION:
Multiple Run
END DESCRIPTION:

--- TRIB 7_1 TO COLETO CREEK RSVR.f01 (steady flow) ---

Flow Title=Multiple
Program Version=4.10
Number of Profiles= 7
Profile Names=10-year,25-year,50-year,1pct_min,100-year,1pct_plu,500-year
River Rch & RM=TRIB 7_1 TO COLE,Reach-1         ,7773
     804    1286    1717    1108    2212    4413    3628
River Rch & RM=TRIB 7_1 TO COLE,Reach-1         ,7002
    1028    1659    2230    1447    2888    5762    4788
Boundary for River Rch & Prof#=TRIB 7_1 TO COLE,Reach-1         , 1
Up Type= 0
Dn Type= 3
Dn Slope=0.008
Boundary for River Rch & Prof#=TRIB 7_1 TO COLE,Reach-1         , 2
Up Type= 0
Dn Type= 3
Dn Slope=0.008
Boundary for River Rch & Prof#=TRIB 7_1 TO COLE,Reach-1         , 3
Up Type= 0
Dn Type= 3
Dn Slope=0.008
Boundary for River Rch & Prof#=TRIB 7_1 TO COLE,Reach-1         , 4
Up Type= 0
Dn Type= 3
Dn Slope=0.008
Boundary for River Rch & Prof#=TRIB 7_1 TO COLE,Reach-1         , 5
Up Type= 0
Dn Type= 3
Dn Slope=0.008
Boundary for River Rch & Prof#=TRIB 7_1 TO COLE,Reach-1         , 6
Up Type= 0
Dn Type= 3
Dn Slope=0.008
Boundary for River Rch & Prof#=TRIB 7_1 TO COLE,Reach-1         , 7
Up Type= 0
Dn Type= 3
Dn Slope=0.008
DSS Import GetInterval= 0
DSS Import GetPeak= 0
DSS Import FillOption= 0

--- TRIB 7_1 TO COLETO CREEK RSVR.g01 (geometry) ---

Geom Title=Existing Conditions
Program Version=4.10

River Reach=TRIB 7_1 TO COLE,Reach-1
Reach XY= 30
        2555025.       13488375.       2555175.1      13488004.9
      2555132.81      13487874.9      2555166.99     13487821.67
       2555078.1     13487676.65      2555219.48     13487527.43
      2555294.77     13487303.97       2555434.7      13487314.8
      2555588.48     13487061.44      2555714.93     13486984.99
      2555683.07     13486871.69      2555825.04     13486659.66
      2555675.75     13486314.31      2555721.87     13486176.63
      2555280.46     13485677.45      2555277.24     13485430.93
      2555480.85     13484972.71      2555571.86     13484873.36
       2555525.1      13484740.4      2555628.83     13484426.58
      2555916.93     13483978.31      2555875.82     13483885.71
      2556066.72     13483228.22      2556033.28     13483171.78
      2556117.44       13482975.      2556078.46     13482826.49
      2556458.34     13482441.66      2556564.65     13482385.12
      2556578.55     13482226.47        2556725.       13481975.

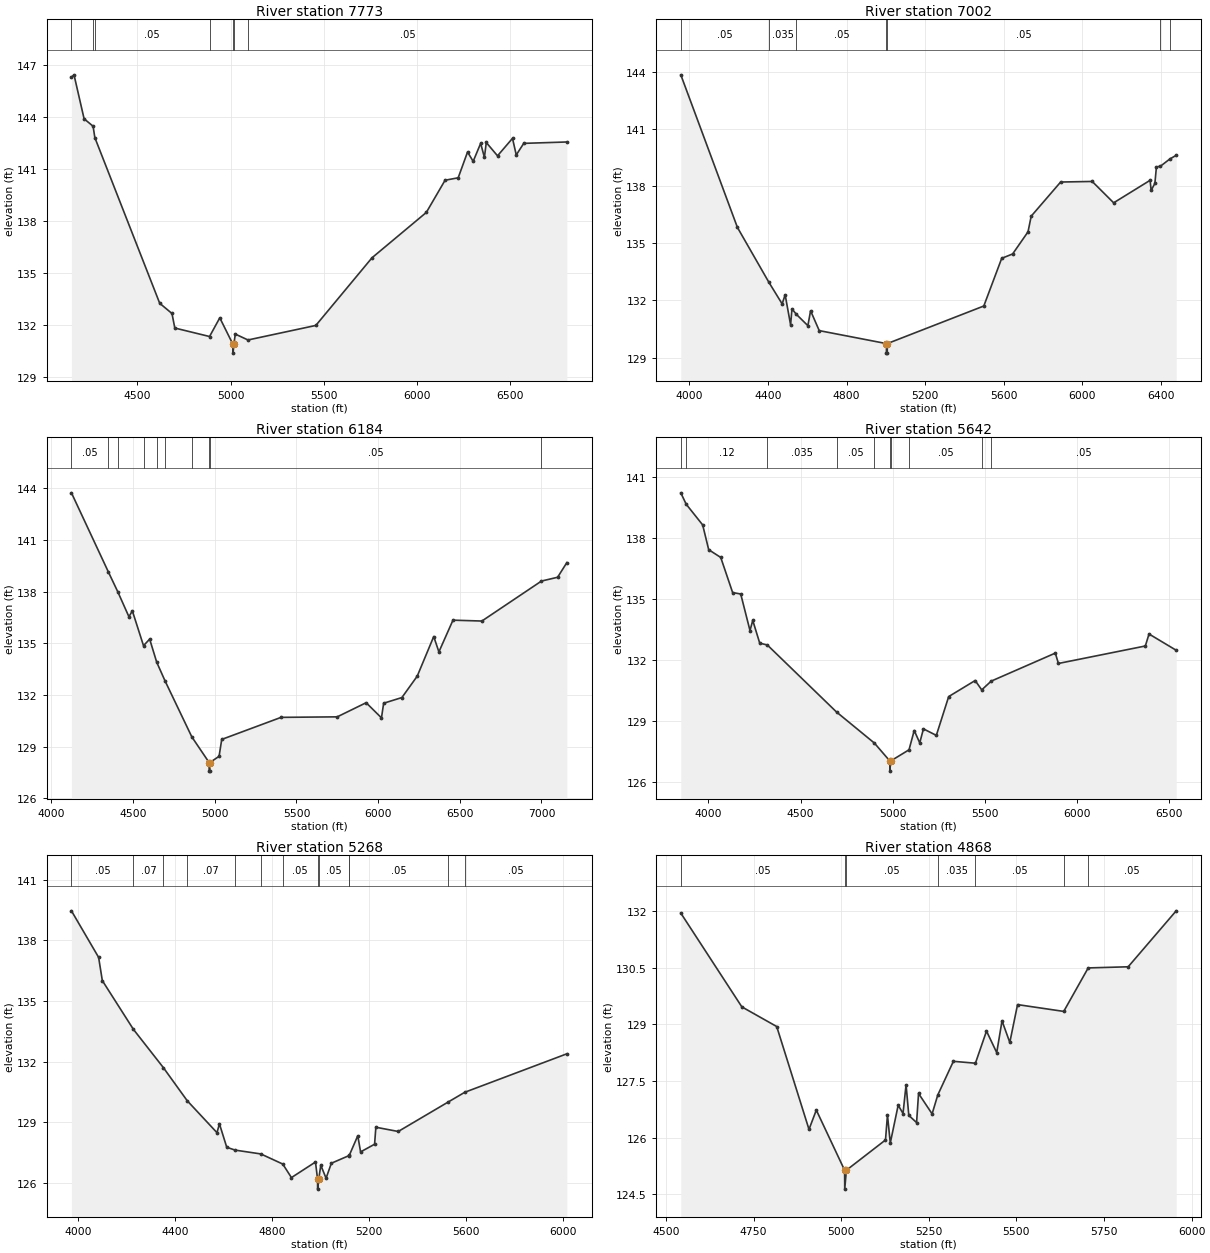
Type RM Length L Ch R = 1 ,7773    ,771,771,771
BEGIN DESCRIPTION:
TRIB 7 TO COLETO CREEK RESERVOIR 26.0
END DESCRIPTION:
XS GIS Cut Line= 3
      2555824.99     13488674.99        2555075.       13488275.
      2553274.96       13488475.
#Sta/Elev= 30
  4145.3  146.31  4159.1  146.45  4213.3  143.91  4261.6  143.48  4271.1  142.82
  4619.5  133.25  4685.4  132.66  4700.6  131.82  4887.2  131.33  4942.2  132.41
  5013.2  130.87  5013.5  130.37  5017.6  130.87  5025.5  131.47  5093.7  131.13
  5458.1  131.97    5760  135.88  6051.7   138.5  6152.4  140.36  6222.8   140.5
  6273.1  141.99  6303.3  141.45  6343.5  142.49  6363.7  141.68  6373.7  142.54
  6434.1  141.77  6514.6  142.78  6534.7  141.82  6574.9  142.49  6806.4  142.57
#Mann= 7 ,-1 , 0
  4145.3     .05       0  4261.6    .035       0  4271.1     .05       0
  4887.2    .035       0  5013.2    .035       0  5017.6    .035       0
  5093.7     .05       0
Bank Sta=5013.2,5017.6
XS Rating Curve= 0 ,0
Exp/Cntr=0.3,0.1

Type RM Length L Ch R = 1 ,7002    ,818,818,818
BEGIN DESCRIPTION:
Mapping XS d65615fd
END DESCRIPTION:
XS GIS Cut Line= 4
      2556034.12     13488141.01      2555152.16     13487627.11
      2555068.82     13487599.33      2553721.65     13488029.87
#Sta/Elev= 30
  3955.9  143.83  4244.2  135.83  4404.1  132.96  4472.1  131.82  4487.3   132.3
  4515.1  130.72    4522  131.56  4544.8  131.27    4603  130.68  4616.9  131.46
  4660.9  130.42    5003  129.74  5003.3  129.24  5007.2  129.24  5007.5  129.74
    5499  131.71  5590.2  134.21  5645.9  134.44  5724.2   135.6  5740.4  136.42
  5890.3  138.21  6051.1  138.24  6160.3  137.12  6345.9   138.3  6351.2  137.77
  6370.3  138.14  6378.1     139  6398.8  139.04  6446.7  139.42  6478.8  139.61
#Mann= 7 ,-1 , 0
  3955.9     .05       0  4404.1    .035       0  4544.8     .05       0
    5003     .05       0  5007.5     .05       0  6398.8     .07       0
  6446.7     .05       0
Bank Sta=5003,5007.5
XS Rating Curve= 0 ,0
Exp/Cntr=0.3,0.1

Type RM Length L Ch R = 1 ,6184    ,542,542,542
BEGIN DESCRIPTION:
Mapping XS 64036dcc
END DESCRIPTION:
XS GIS Cut Line= 4
      2556221.61     13487675.72      2555603.55     13487092.39
      2555457.71     13487057.66      2553534.08     13487717.39
#Sta/Elev= 30
  4122.2  143.73  4348.3  139.14  4405.9  137.99  4474.2  136.54  4495.2  136.88
  4563.5  134.86  4601.2  135.24  4644.4   133.9  4695.2  132.82  4859.2  129.57
  4965.2  128.08  4965.6  127.58  4969.7  127.58    4970  128.08  5026.3  128.44
  5042.5  129.42  5405.8   130.7  5749.8  130.73  5926.8  131.55  6020.6  130.67
    6034  131.52  6145.7  131.85  6239.5  133.09  6340.6  135.39  6372.3   134.5
  6458.4  136.34  6635.5  136.29  7000.3  138.61  7099.2  138.83  7155.6  139.68
#Mann= 10 ,-1 , 0
  4122.2     .05       0  4348.3     .07       0  4405.9    .035       0
  4563.5     .07       0  4644.4     .05       0  4695.2     .07       0
  4859.2     .05       0  4965.2     .05       0    4970     .05       0
  7000.3     .07       0
Bank Sta=4965.2,4970
XS Rating Curve= 0 ,0
Exp/Cntr=0.3,0.1

Type RM Length L Ch R = 1 ,5642    ,374,374,374
BEGIN DESCRIPTION:
Mapping XS 5967efaa
END DESCRIPTION:
XS GIS Cut Line= 4
       2556923.8      13486944.9       2556107.8     13486693.16
      2555569.61     13486684.48      2554278.13     13486797.15
#Sta/Elev= 30
  3849.9  140.22  3879.1  139.66  3968.6  138.64  4001.3  137.42  4066.6  137.04
  4131.2  135.31  4175.1  135.24  4225.4  133.44  4240.4  133.94  4278.3  132.82
  4319.5  132.73  4695.1  129.43  4900.7   127.9  4984.3  127.02  4984.6  126.52
  4989.1  127.02  5088.5  127.57  5116.7  128.52  5146.7  127.91  5166.7   128.6
  5236.7  128.28  5303.8  130.19  5447.5  130.98  5483.1  130.52  5534.4  130.95
  5882.5  132.33  5899.2  131.82    6371  132.68  6391.1  133.27  6538.5  132.47
#Mann= 10 ,-1 , 0
  3849.9     .07       0  3879.1     .12       0  4319.5    .035       0
  4695.1     .05       0  4900.7    .035       0  4984.3    .035       0
  4989.1    .035       0  5088.5     .05       0  5483.1    .035       0
  5534.4     .05       0
Bank Sta=4984.3,4989.1
XS Rating Curve= 0 ,0
Exp/Cntr=0.3,0.1

Type RM Length L Ch R = 1 ,5268    ,400,400,400
BEGIN DESCRIPTION:
Mapping XS 5f066ec1
END DESCRIPTION:
XS GIS Cut Line= 4
      2556701.58     13486302.54      2556008.84     13486224.41
      2555529.68     13486432.74       2554728.8     13486625.16
#Sta/Elev= 30
  3972.3  139.46  4084.4  137.16  4099.7  136.01  4227.9   133.6  4351.3  131.71
  4449.9  130.07  4572.7  128.49  4582.7  128.93  4612.9  127.77  4647.2  127.63
  4753.4  127.44  4843.9  126.94  4879.7  126.27  4978.9  127.04  4987.4   126.2
  4987.8   125.7  4992.4   126.2  5000.8  126.88  5022.6  126.24  5044.4  126.98
  5115.8  127.35  5118.3  127.37  5153.4  128.34  5164.9  127.54  5222.7  127.92
  5227.9  128.76  5320.2  128.55  5525.3     130  5594.9  130.49  6015.6  132.39
#Mann= 13 ,-1 , 0
  3972.3     .05       0  4227.9     .07       0  4351.3     .12       0
  4449.9     .07       0  4647.2    .035       0  4753.4     .07       0
  4843.9     .05       0  4987.4     .05       0  4992.4     .05       0
  5115.8    .035       0  5118.3     .05       0  5525.3    .035       0
  5594.9     .05       0
Bank Sta=4987.4,4992.4
XS Rating Curve= 0 ,0
Exp/Cntr=0.3,0.1

Type RM Length L Ch R = 1 ,4868    ,555,555,555
BEGIN DESCRIPTION:
Mapping XS b77a1541
END DESCRIPTION:
XS GIS Cut Line= 4
      2555930.69     13485734.85      2555576.55     13486047.32
      2555060.93     13486312.95      2554712.01     13486406.69
#Sta/Elev= 30
  4542.3  131.94  4716.5  129.46    4816  128.94  4908.1  126.22    4929  126.73
  5009.7  125.14  5010.1  124.64  5014.8  125.14  5126.4  125.94    5132   126.6
  5140.1  125.86  5162.6  126.86  5176.4  126.64  5185.1   127.4  5192.9  126.59
  5215.1   126.4  5220.7  127.17  5259.4  126.63  5275.6  127.13  5320.1  128.02
    5383  127.97  5414.6  128.82  5443.8  128.25  5458.9  129.09  5481.1  128.52
  5503.2  129.52    5635  129.34  5704.8  130.49  5818.9  130.52  5955.9     132
#Mann= 7 ,-1 , 0
  4542.3     .05       0  5009.7     .05       0  5014.8     .05       0
  5275.6    .035       0    5383     .05       0    5635    .035       0
  5704.8     .05       0
Bank Sta=5009.7,5014.8
XS Rating Curve= 0 ,0
Exp/Cntr=0.3,0.1

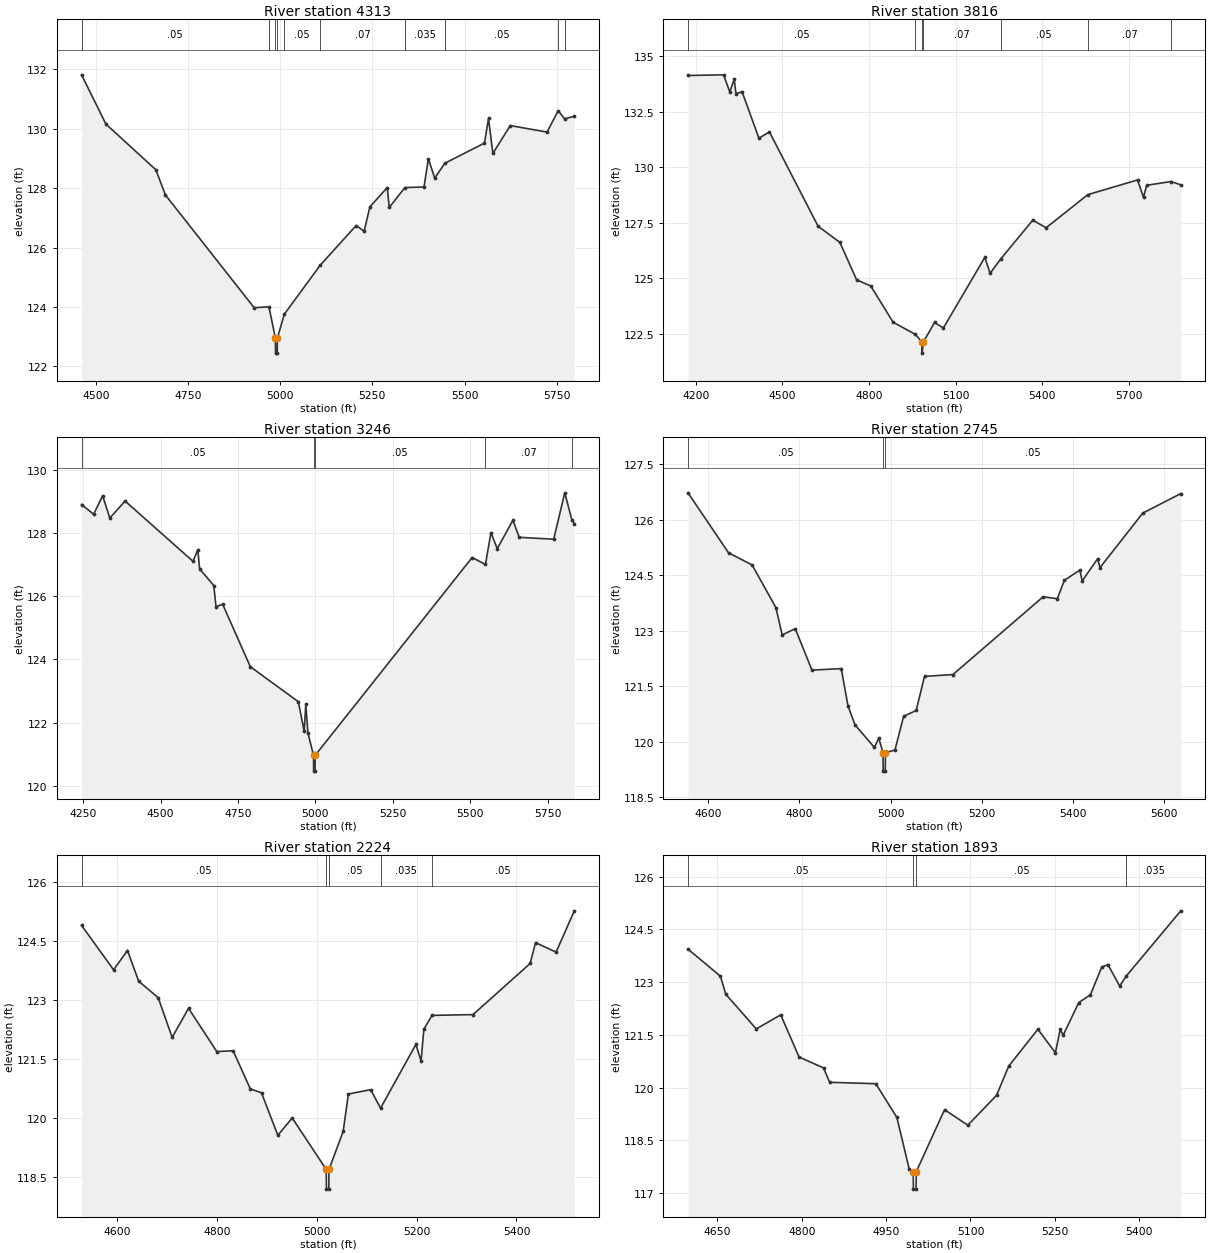
Type RM Length L Ch R = 1 ,4313    ,497,497,497
BEGIN DESCRIPTION:
Mapping XS a4d32fef
END DESCRIPTION:
XS GIS Cut Line= 3
      2555811.84     13485564.61      2555270.21     13485606.27
      2554541.08     13485918.76
#Sta/Elev= 30
  4461.3  131.82  4527.4  130.16  4662.8  128.62  4688.8  127.77  4929.5  123.97
  4969.6     124  4987.1  122.94  4987.5  122.44  4991.9  122.44  4992.3  122.94
  5011.2  123.75  5108.4   125.4    5206  126.74  5227.8  126.55  5243.3  127.37
  5290.4  128.02  5295.9  127.35  5338.4  128.02  5390.2  128.04  5401.9  128.99
  5419.2  128.34  5446.7  128.84  5554.2  129.52  5565.1  130.35  5576.9  129.17
  5624.1  130.11  5723.8  129.89    5754  130.61  5771.4  130.34  5797.8  130.42
#Mann= 10 ,-1 , 0
  4461.3     .05       0  4969.6     .07       0  4987.1     .05       0
  4992.3     .07       0  5011.2     .05       0  5108.4     .07       0
  5338.4    .035       0  5446.7     .05       0    5754    .035       0
  5771.4     .05       0
Bank Sta=4987.1,4992.3
XS Rating Curve= 0 ,0
Exp/Cntr=0.3,0.1

Type RM Length L Ch R = 1 ,3816    ,570,570,570
BEGIN DESCRIPTION:
Mapping XS 94b0b89f
END DESCRIPTION:
XS GIS Cut Line= 4
      2556144.23     13485484.81      2555701.55     13485213.99
      2555222.38     13485109.82      2554550.48     13485292.12
#Sta/Elev= 30
  4173.6  134.12  4296.8  134.15  4318.1  133.38  4333.5  133.95  4339.4   133.3
  4360.7  133.39  4418.9   131.3  4455.5  131.58  4623.8  127.34  4699.3  126.61
    4757  124.93  4806.1  124.65  4883.5  123.02  4960.8  122.47  4983.2  122.13
  4983.6  121.63  4988.4  122.13  5026.7  123.01  5057.4  122.76  5200.9  125.94
  5219.1  125.22  5256.1  125.87  5366.7  127.61    5413  127.27  5557.4  128.76
  5729.4  129.42  5750.1  128.64    5761  129.18  5845.6  129.35  5879.1   129.2
#Mann= 7 ,-1 , 0
  4173.6     .05       0  4960.8     .07       0  4983.2     .05       0
  4988.4     .07       0  5256.1     .05       0  5557.4     .07       0
  5845.6     .05       0
Bank Sta=4983.2,4988.4
XS Rating Curve= 0 ,0
Exp/Cntr=0.3,0.1

Type RM Length L Ch R = 1 ,3246    ,501,501,501
BEGIN DESCRIPTION:
Mapping XS 61fdbd71
END DESCRIPTION:
XS GIS Cut Line= 4
      2556253.67     13484979.63      2555852.59     13484745.24
      2555415.09     13484630.66      2554749.17     13484734.71
#Sta/Elev= 30
  4245.1  128.91  4284.1   128.6  4313.1  129.19  4336.2  128.48  4385.7  129.02
  4604.8  127.11  4620.5  127.48  4626.3  126.87  4672.1  126.34  4679.1  125.67
  4700.6  125.75  4789.9  123.77  4944.9  122.66  4963.8  121.72    4969  122.58
  4975.9  121.67    4994  120.96  4994.4  120.46  4998.9  120.46  4999.3  120.96
  5506.1  127.23    5549  127.01  5566.8  128.02  5587.1  127.51  5637.7  128.41
  5657.9  127.87  5769.3  127.81  5805.1  129.28  5827.8  128.43  5835.9   128.3
#Mann= 5 ,-1 , 0
  4245.1     .05       0    4994     .05       0  4999.3     .05       0
    5549     .07       0  5827.8     .05       0
Bank Sta=4994,4999.3
XS Rating Curve= 0 ,0
Exp/Cntr=0.3,0.1

Type RM Length L Ch R = 1 ,2745    ,521,521,521
BEGIN DESCRIPTION:
Mapping XS 8e009b81
END DESCRIPTION:
XS GIS Cut Line= 3
      2556110.49      13484453.5      2555707.71      13484203.5
       2555124.7     13484370.07
#Sta/Elev= 30
  4555.7  126.73  4644.5  125.11  4696.3  124.78  4748.3  123.63  4762.2  122.89
  4790.8  123.06  4827.4  121.94  4891.7  121.98  4906.5  120.97  4921.9  120.46
  4964.4  119.85  4973.9   120.1  4983.2  119.71  4983.6  119.21  4988.1  119.21
  4988.5  119.71  5009.4  119.78  5028.4  120.69    5056  120.85  5074.2  121.77
  5136.6  121.82  5334.2  123.92  5365.4  123.87    5381  124.37  5414.8  124.64
    5420  124.35  5453.8  124.95    5459  124.71  5552.6  126.18  5636.1  126.71
#Mann= 3 ,-1 , 0
  4555.7     .05       0  4983.2     .05       0  4988.5     .05       0
Bank Sta=4983.2,4988.5
XS Rating Curve= 0 ,0
Exp/Cntr=0.3,0.1

Type RM Length L Ch R = 1 ,2224    ,331,331,331
BEGIN DESCRIPTION:
Mapping XS 14cbac1e
END DESCRIPTION:
XS GIS Cut Line= 3
      2556346.57     13484009.04      2555916.05     13483793.77
      2555429.94     13483932.66
#Sta/Elev= 30
  4528.9  124.89    4593  123.76  4620.9  124.25  4643.3  123.47  4682.4  123.05
  4710.4  122.04  4743.1  122.78  4799.8  121.68  4832.5   121.7  4866.9  120.73
  4889.3  120.63    4922  119.55  4950.8  119.99    5019  118.68  5019.4  118.18
    5024  118.18  5024.5  118.68  5052.9  119.65  5063.3   120.6  5107.9  120.71
  5127.7  120.24  5198.5  121.86  5208.9  121.44  5214.5  122.25  5230.8   122.6
  5312.9  122.62  5427.3  123.92  5438.1  124.45  5479.3  124.21  5515.8  125.26
#Mann= 5 ,-1 , 0
  4528.9     .05       0    5019     .05       0  5024.5     .05       0
  5127.7    .035       0  5230.8     .05       0
Bank Sta=5019,5024.5
XS Rating Curve= 0 ,0
Exp/Cntr=0.3,0.1

Type RM Length L Ch R = 1 ,1893    ,467,467,467
BEGIN DESCRIPTION:
Mapping XS 4b15ad74
END DESCRIPTION:
XS GIS Cut Line= 3
      2556346.64     13483641.01       2555971.6     13483481.27
      2555520.23     13483606.27
#Sta/Elev= 30
  4597.9  123.94  4655.5  123.17  4664.9  122.66  4719.2  121.67  4762.7  122.07
  4795.3  120.87  4838.8  120.56  4849.7  120.15  4931.7  120.11  4969.2  119.15
    4991  117.69  4998.2  117.61  4998.6  117.11  5003.3  117.11  5003.8  117.61
  5053.9  119.37  5095.4  118.93  5146.4  119.78    5168  120.61  5219.9  121.66
    5251  120.99  5259.6  121.66  5264.8  121.49  5292.6  122.42  5313.3  122.64
  5333.4  123.43  5344.4   123.5  5365.2  122.89  5377.3  123.18  5473.9  125.03
#Mann= 4 ,-1 , 0
  4597.9     .05       0  4998.2     .05       0  5003.8     .05       0
  5377.3    .035       0
Bank Sta=4998.2,5003.8
XS Rating Curve= 0 ,0
Exp/Cntr=0.3,0.1

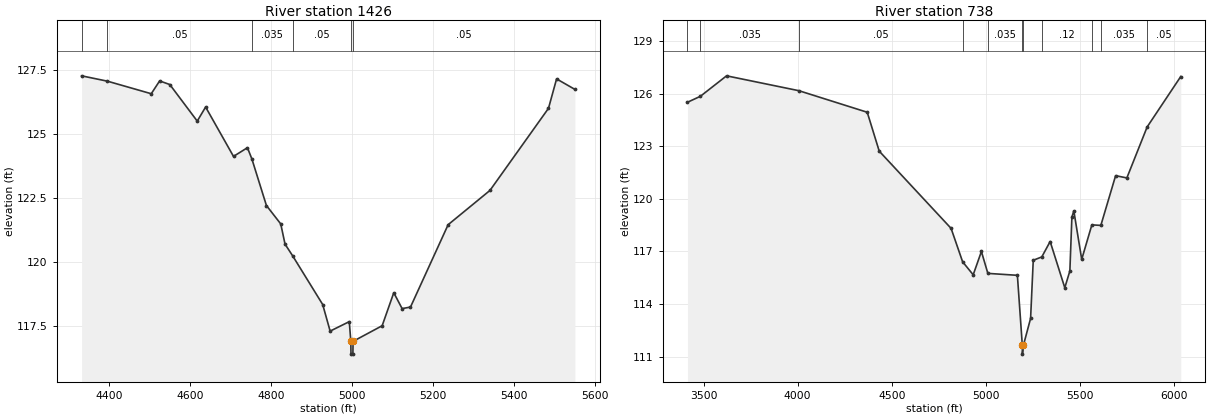
Type RM Length L Ch R = 1 ,1426    ,688,688,688
BEGIN DESCRIPTION:
Mapping XS 10d218fd
END DESCRIPTION:
XS GIS Cut Line= 3
      2556721.63     13483224.34      2556103.55     13483064.61
       2555541.9     13483210.22
#Sta/Elev= 30
  4332.1  127.29  4396.1  127.08  4504.2  126.59  4524.9  127.09    4550  126.95
  4617.8  125.52  4638.5  126.07  4707.4  124.14  4741.8  124.48  4752.8  124.04
  4788.7  122.22  4824.1   121.5  4834.7  120.71  4853.6  120.25  4927.7  118.35
  4946.1  117.31  4993.4  117.68  4997.2  116.91  4997.6  116.41  5002.3  116.41
  5002.8  116.91  5074.6  117.52  5103.3  118.81  5123.9  118.19  5144.6  118.25
  5237.6  121.47  5340.9  122.81  5485.5  126.02  5505.5  127.17  5550.7  126.76
#Mann= 6 ,-1 , 0
  4332.1    .035       0  4396.1     .05       0  4752.8    .035       0
  4853.6     .05       0  4997.2     .05       0  5002.8     .05       0
Bank Sta=4997.2,5002.8
XS Rating Curve= 0 ,0
Exp/Cntr=0.3,0.1

Type RM Length L Ch R = 1 ,738     ,0,0,0
BEGIN DESCRIPTION:
Mapping XS d0ad70b1
END DESCRIPTION:
XS GIS Cut Line= 5
      2557762.93       13482983.      2556835.01     13482983.91
      2556445.63     13482584.91      2556138.33      13482454.7
      2555372.72     13482694.28
#Sta/Elev= 30
  3414.6  125.52  3483.2  125.86  3622.5  127.03  4007.1  126.18    4370  124.95
  4433.7  122.73  4815.6  118.32  4876.9  116.41  4933.1  115.67  4976.7     117
    5011  115.75  5167.9  115.64  5194.1  111.64  5194.6  111.14  5199.8  111.64
  5238.1  113.18  5252.2   116.5  5297.6  116.69    5342  117.57  5419.8  114.93
  5446.8  115.89  5457.5  118.96  5467.8  119.32  5509.7  116.55  5563.6  118.52
  5611.4  118.49  5689.9  121.33  5749.6   121.2  5857.4  124.11    6036  126.99
#Mann= 11 ,-1 , 0
  3414.6     .05       0  3483.2    .035       0  4007.1     .05       0
  4876.9     .12       0    5011    .035       0  5194.1   .0335       0
  5199.8    .035       0  5297.6     .12       0  5563.6     .05       0
  5611.4    .035       0  5857.4     .05       0
Bank Sta=5194.1,5199.8
XS Rating Curve= 0 ,0
Exp/Cntr=0.3,0.1

Chan Stop Cuts=-1
Use User Specified Reach Order=0
Composite Channel Slope=5