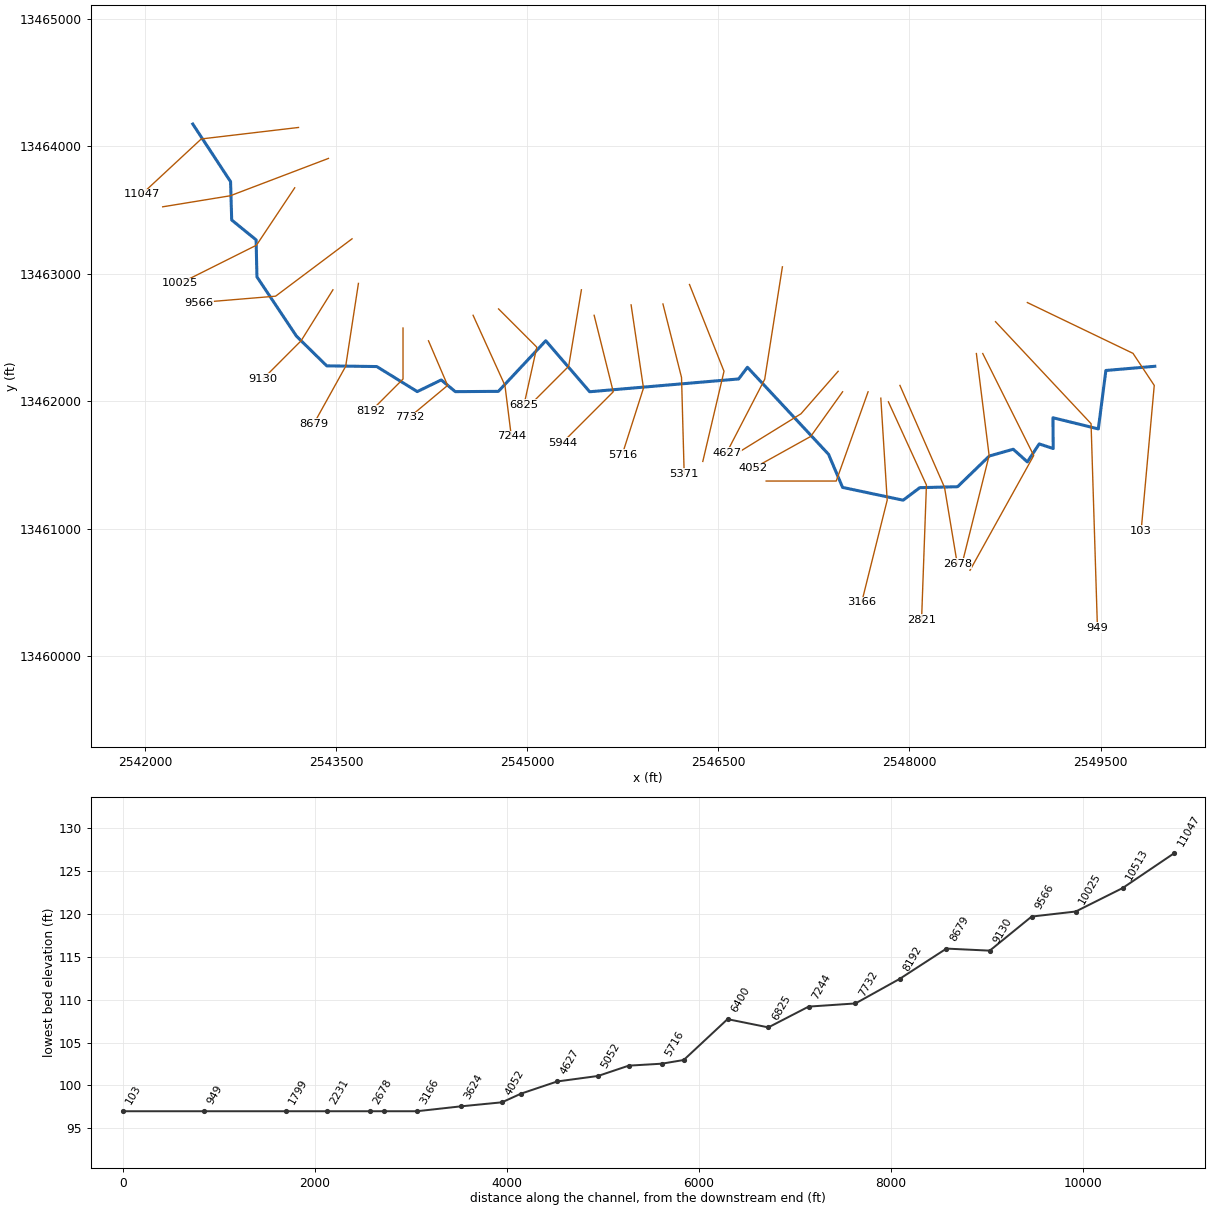
--- TRIB A TO TURKEY CREEK.prj (project) ---

Proj Title=TRIB A TO TURKEY CREEK Base Level Engineering
Current Plan=p01
Default Exp/Contr=0.3,0.1
English Units
Geom File=g01
Flow File=f01
Plan File=p01
Y Axis Title=Elevation
X Axis Title(PF)=Main Channel Distance
X Axis Title(XS)=Station
BEGIN DESCRIPTION:
TRIB A TO TURKEY CREEK
END DESCRIPTION:
DSS Export Rating Curves= 0
DSS Export Rating Curve Sorted= 0
DSS Export Volume Flow Curves= 0
DXF OffsetX= 0
DXF OffsetY= 0
DXF ScaleX= 1
DXF ScaleY= 10

--- TRIB A TO TURKEY CREEK.p01 (plan) ---

Plan Title=Multiple Run
Short Identifier=Multiple
Geom File=g01
Flow File=f01
Subcritical Flow
K Sum by GR= 0
Std Step Tol= 0.01
Critical Tol= 0.01
Num of Std Step Trials= 20
Max Error Tol= 0.3
Flow Tol Ratio= 0.001
Split Flow NTrial= 30
Split Flow Tol= 0.02
Split Flow Ratio= 0.02
Log Output Level= 0
Friction Slope Method= 1
Unsteady Friction Slope Method= 2
Unsteady Bridges Friction Slope Method= 1
Parabolic Critical Depth
Global Vel Dist=  1 , 1 , 1
Global Log Level= 0
CheckData=True
Encroach Param= -1, 0, 0, 0
BEGIN DESCRIPTION:
Multiple Run
END DESCRIPTION:

--- TRIB A TO TURKEY CREEK.f01 (steady flow) ---

Flow Title=Multiple
Program Version=4.10
Number of Profiles= 7
Profile Names=10-year,25-year,50-year,1pct_min,100-year,1pct_plu,500-year
River Rch & RM=TRIB A TO TURKEY,Reach-1         ,11047
     303     452     577     357     712    1420    1068
River Rch & RM=TRIB A TO TURKEY,Reach-1         ,8192
     584     910    1194     758    1512    3017    2394
River Rch & RM=TRIB A TO TURKEY,Reach-1         ,3166
     821    1300    1724    1103    2201    4391    3548
Boundary for River Rch & Prof#=TRIB A TO TURKEY,Reach-1         , 1
Up Type= 0
Dn Type= 3
Dn Slope=0.00025
Boundary for River Rch & Prof#=TRIB A TO TURKEY,Reach-1         , 2
Up Type= 0
Dn Type= 3
Dn Slope=0.00025
Boundary for River Rch & Prof#=TRIB A TO TURKEY,Reach-1         , 3
Up Type= 0
Dn Type= 3
Dn Slope=0.00025
Boundary for River Rch & Prof#=TRIB A TO TURKEY,Reach-1         , 4
Up Type= 0
Dn Type= 3
Dn Slope=0.00025
Boundary for River Rch & Prof#=TRIB A TO TURKEY,Reach-1         , 5
Up Type= 0
Dn Type= 3
Dn Slope=0.00025
Boundary for River Rch & Prof#=TRIB A TO TURKEY,Reach-1         , 6
Up Type= 0
Dn Type= 3
Dn Slope=0.00025
Boundary for River Rch & Prof#=TRIB A TO TURKEY,Reach-1         , 7
Up Type= 0
Dn Type= 3
Dn Slope=0.00025
DSS Import GetInterval= 0
DSS Import GetPeak= 0
DSS Import FillOption= 0

--- TRIB A TO TURKEY CREEK.g01 (geometry) ---

Geom Title=Existing Conditions
Program Version=4.10

River Reach=TRIB A TO TURKEY,Reach-1
Reach XY= 30
        2542375.       13464175.      2542671.45     13463723.53
      2542680.46     13463422.55      2542871.93      13463266.7
      2542878.54     13462976.46      2543188.55     13462511.65
      2543426.25     13462278.45      2543819.14     13462272.93
      2544136.88     13462076.53        2544325.      13462167.9
      2544435.43     13462076.06      2544773.53     13462078.55
      2545145.23     13462475.29      2545490.15     13462075.38
      2546659.17     13462175.69      2546728.16     13462267.46
      2547364.52      13461584.8        2547475.       13461325.
      2547950.12     13461224.71      2548080.86     13461322.93
      2548377.45     13461330.46       2548626.5     13461571.39
      2548814.38     13461624.45        2548925.       13461525.
      2549017.99     13461665.99      2549127.85     13461630.11
      2549125.99     13461871.47        2549482.     13461783.82
      2549541.24     13462242.23        2549925.       13462275.

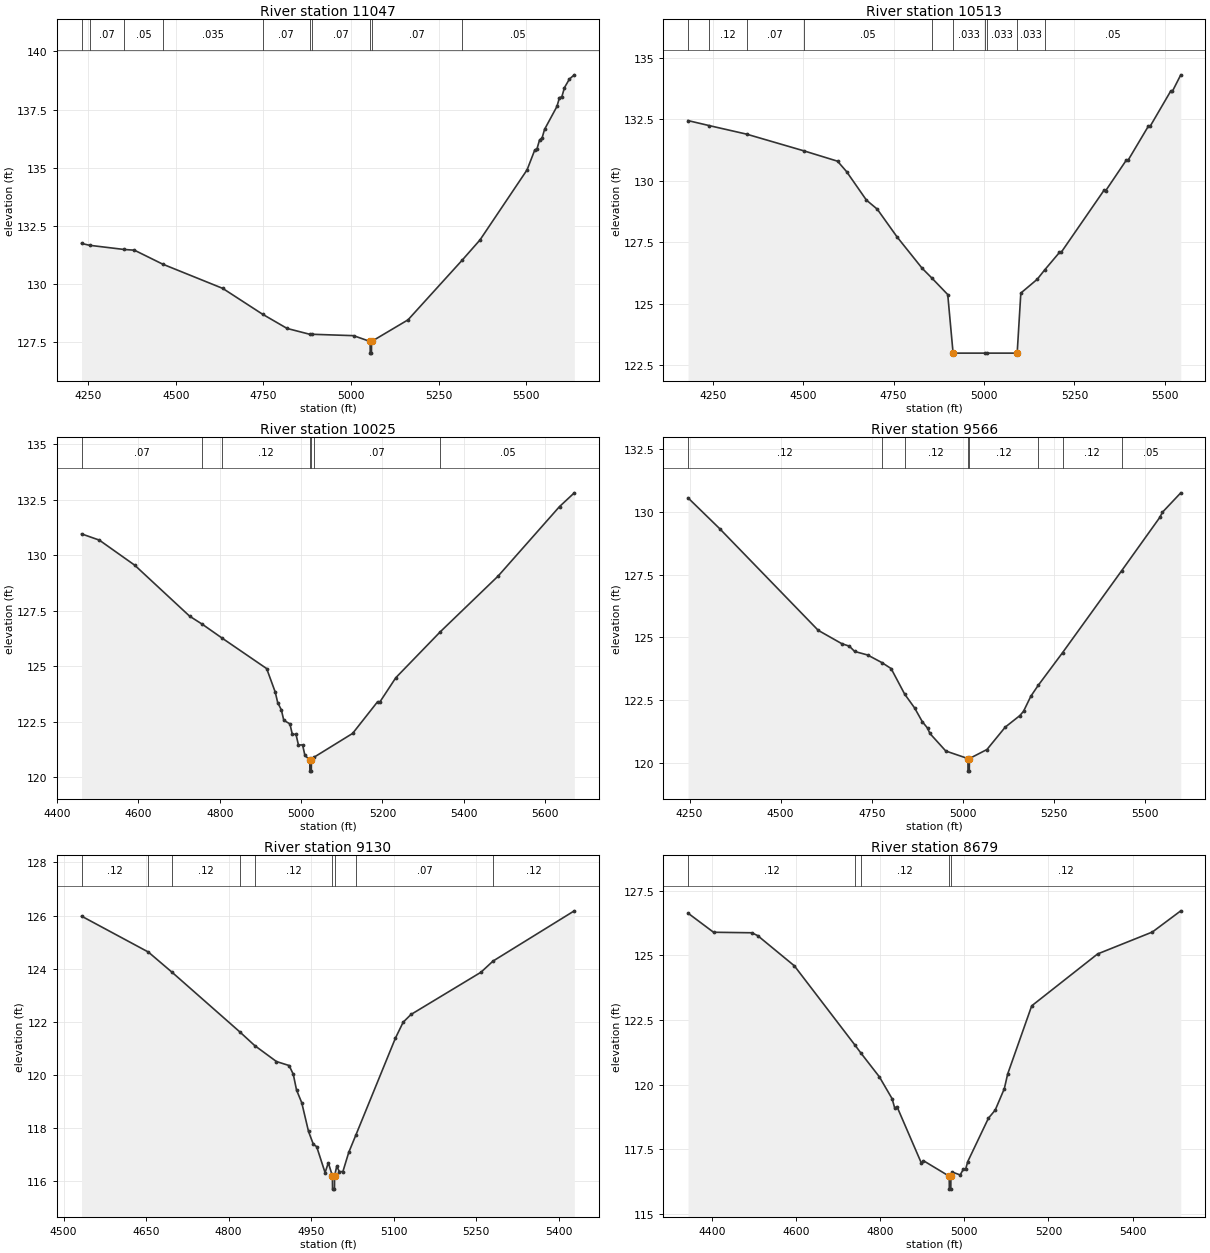
Type RM Length L Ch R = 1 ,11047   ,534,534,534
BEGIN DESCRIPTION:
TRIB A TO TURKEY CREEK 23.0
END DESCRIPTION:
XS GIS Cut Line= 3
       2543204.8      13464148.4       2542441.6     13464058.31
      2541974.97     13463624.98
#Sta/Elev= 30
  4231.5  131.75  4254.5  131.67  4353.2  131.49  4382.3  131.46    4463  130.86
  4634.1  129.82  4747.8  128.71  4817.7   128.1  4882.1  127.85  4888.5  127.85
  5007.2  127.79  5054.5  127.54  5054.8  127.04  5058.3  127.04  5058.5  127.54
  5162.6  128.47  5316.9  131.03  5367.8   131.9  5502.1  134.91  5523.7  135.75
  5530.5  135.82  5537.8   136.2  5544.7  136.27    5552  136.65  5587.2  137.63
  5594.5  138.01  5601.3  138.05  5608.7  138.44  5622.9  138.81  5636.8  138.99
#Mann= 10 ,-1 , 0
  4231.5     .12       0  4254.5     .07       0  4353.2     .05       0
    4463    .035       0  4747.8     .07       0  4882.1    .033       0
  4888.5     .07       0  5054.5     .05       0  5058.5     .07       0
  5316.9     .05       0
Bank Sta=5054.5,5058.5
XS Rating Curve= 0 ,0
Exp/Cntr=0.3,0.1

Type RM Length L Ch R = 1 ,10513   ,488,488,488
BEGIN DESCRIPTION:
Mapping XS adba1d44
END DESCRIPTION:
XS GIS Cut Line= 3
      2543439.64     13463905.57      2542669.21     13463612.59
      2542138.79     13463525.99
#Sta/Elev= 30
    4182  132.45  4239.6  132.25  4343.7   131.9  4502.3  131.22  4595.2   130.8
    4620  130.38  4674.9  129.22    4705  128.85  4759.8  127.72  4828.9  126.45
  4856.6  126.04  4899.7  125.38  4914.5     123  5003.8     123  5007.8     123
  5091.6     123  5101.7  125.44  5146.9     126  5167.5  126.38  5208.3  127.09
  5213.4   127.1  5331.2  129.61  5336.2   129.6  5392.6  130.83  5397.7  130.83
    5454  132.22  5459.1  132.22  5515.5  133.64  5520.5  133.64  5543.7  134.31
#Mann= 10 ,-1 , 0
    4182     .07       0  4239.6     .12       0  4343.7     .07       0
  4502.3     .05       0  4856.6    .033       0  4914.5    .033       0
  5003.8    .033       0  5007.8    .033       0  5091.6    .033       0
  5167.5     .05       0
Bank Sta=4914.5,5091.6
XS Rating Curve= 0 ,0
Exp/Cntr=0.3,0.1

Type RM Length L Ch R = 1 ,10025   ,459,459,459
BEGIN DESCRIPTION:
TRIB A TO TURKEY CREEK 21.0
END DESCRIPTION:
XS GIS Cut Line= 3
      2543175.01     13463675.02        2542875.       13463225.
      2542274.98     13462924.99
#Sta/Elev= 30
  4460.2  130.96  4503.8  130.68  4590.9  129.55  4726.1  127.25    4757  126.89
  4805.3  126.27  4915.4  124.89  4936.5  123.83  4942.5  123.36  4951.5  123.03
  4957.5  122.56  4972.5   122.4  4978.5  121.93  4987.5  121.93  4993.5  121.45
  5003.8  121.45  5009.4  120.98  5021.4  120.77  5021.7  120.27  5025.2  120.27
  5025.4  120.77  5031.3  120.89  5126.8  121.97  5188.3   123.4  5193.9  123.39
    5233  124.48  5342.4  126.55  5484.6  129.06  5635.5  132.19  5671.9  132.81
#Mann= 7 ,-1 , 0
  4460.2     .07       0    4757     .05       0  4805.3     .12       0
  5021.4     .05       0  5025.4     .12       0  5031.3     .07       0
  5342.4     .05       0
Bank Sta=5021.4,5025.4
XS Rating Curve= 0 ,0
Exp/Cntr=0.3,0.1

Type RM Length L Ch R = 1 ,9566    ,436,436,436
BEGIN DESCRIPTION:
TRIB A TO TURKEY CREEK 20.0
END DESCRIPTION:
XS GIS Cut Line= 3
      2543625.01     13463275.01        2543025.       13462825.
      2542424.99       13462775.
#Sta/Elev= 30
  4245.8  130.55  4332.3  129.33  4603.1  125.28  4667.7  124.75  4688.5  124.65
  4703.1  124.44  4738.5   124.3  4777.4     124  4803.1  123.76  4840.4  122.74
  4867.7  122.19  4888.5  121.65  4903.1  121.39  4909.4  121.18  4953.1  120.48
  5013.9  120.18  5014.1  119.68  5017.6  119.68  5017.9  120.18  5066.1  120.54
  5116.2  121.43  5156.4  121.89  5166.4  122.06  5186.5  122.66  5206.6  123.09
  5273.4  124.39  5436.1  127.66  5540.2  129.77  5547.7  129.98  5597.9  130.75
#Mann= 8 ,-1 , 0
  4245.8     .12       0  4777.4     .07       0  4840.4     .12       0
  5013.9     .05       0  5017.9     .12       0  5206.6     .07       0
  5273.4     .12       0  5436.1     .05       0
Bank Sta=5013.9,5017.9
XS Rating Curve= 0 ,0
Exp/Cntr=0.3,0.1

Type RM Length L Ch R = 1 ,9130    ,451,451,451
BEGIN DESCRIPTION:
TRIB A TO TURKEY CREEK 19.0
END DESCRIPTION:
XS GIS Cut Line= 3
        2543475.       13462875.        2543225.       13462475.
      2542924.97     13462174.97
#Sta/Elev= 30
  4532.6  125.98    4654  124.63  4697.1  123.87  4820.1  121.63  4847.5  121.11
    4887  120.51    4910  120.36  4917.6  120.03  4923.5  119.44    4933  118.96
  4945.3  117.88  4954.2  117.39  4960.1  117.31  4975.4  116.33  4981.3   116.7
  4988.7  116.21    4989  115.71  4992.5  115.71  4992.7  116.21  4996.6  116.57
  5001.4  116.37  5007.8  116.37  5018.4  117.09  5031.5  117.75  5103.3  121.39
  5117.4  121.99  5131.6  122.28  5258.9  123.87  5280.8  124.29  5428.6  126.18
#Mann= 9 ,-1 , 0
  4532.6     .12       0    4654     .07       0  4697.1     .12       0
  4820.1     .07       0  4847.5     .12       0  4988.7     .05       0
  4992.7     .12       0  5031.5     .07       0  5280.8     .12       0
Bank Sta=4988.7,4992.7
XS Rating Curve= 0 ,0
Exp/Cntr=0.3,0.1

Type RM Length L Ch R = 1 ,8679    ,487,487,487
BEGIN DESCRIPTION:
TRIB A TO TURKEY CREEK 18.0
END DESCRIPTION:
XS GIS Cut Line= 3
        2543675.     13462925.03        2543575.       13462275.
      2543324.98     13461824.96
#Sta/Elev= 30
  4342.3  126.64    4403   125.9  4494.1  125.88    4508  125.77  4595.3   124.6
  4739.5  121.53  4754.2  121.21  4797.6   120.3    4828  119.45  4834.3  119.08
  4839.4  119.15  4897.5  116.96  4902.6  117.05  4963.8  116.45  4964.1  115.95
  4967.6  115.95  4967.8  116.45  4970.9  116.61  4989.9   116.5  4997.4  116.72
  5002.8  116.72    5008  117.02  5057.2   118.7  5073.2  119.01  5094.9  119.84
  5102.9  120.41  5160.1  123.05  5316.9  125.06  5447.3  125.91  5514.8  126.73
#Mann= 5 ,-1 , 0
  4342.3     .12       0  4739.5     .07       0  4754.2     .12       0
  4963.8     .05       0  4967.8     .12       0
Bank Sta=4963.8,4967.8
XS Rating Curve= 0 ,0
Exp/Cntr=0.3,0.1

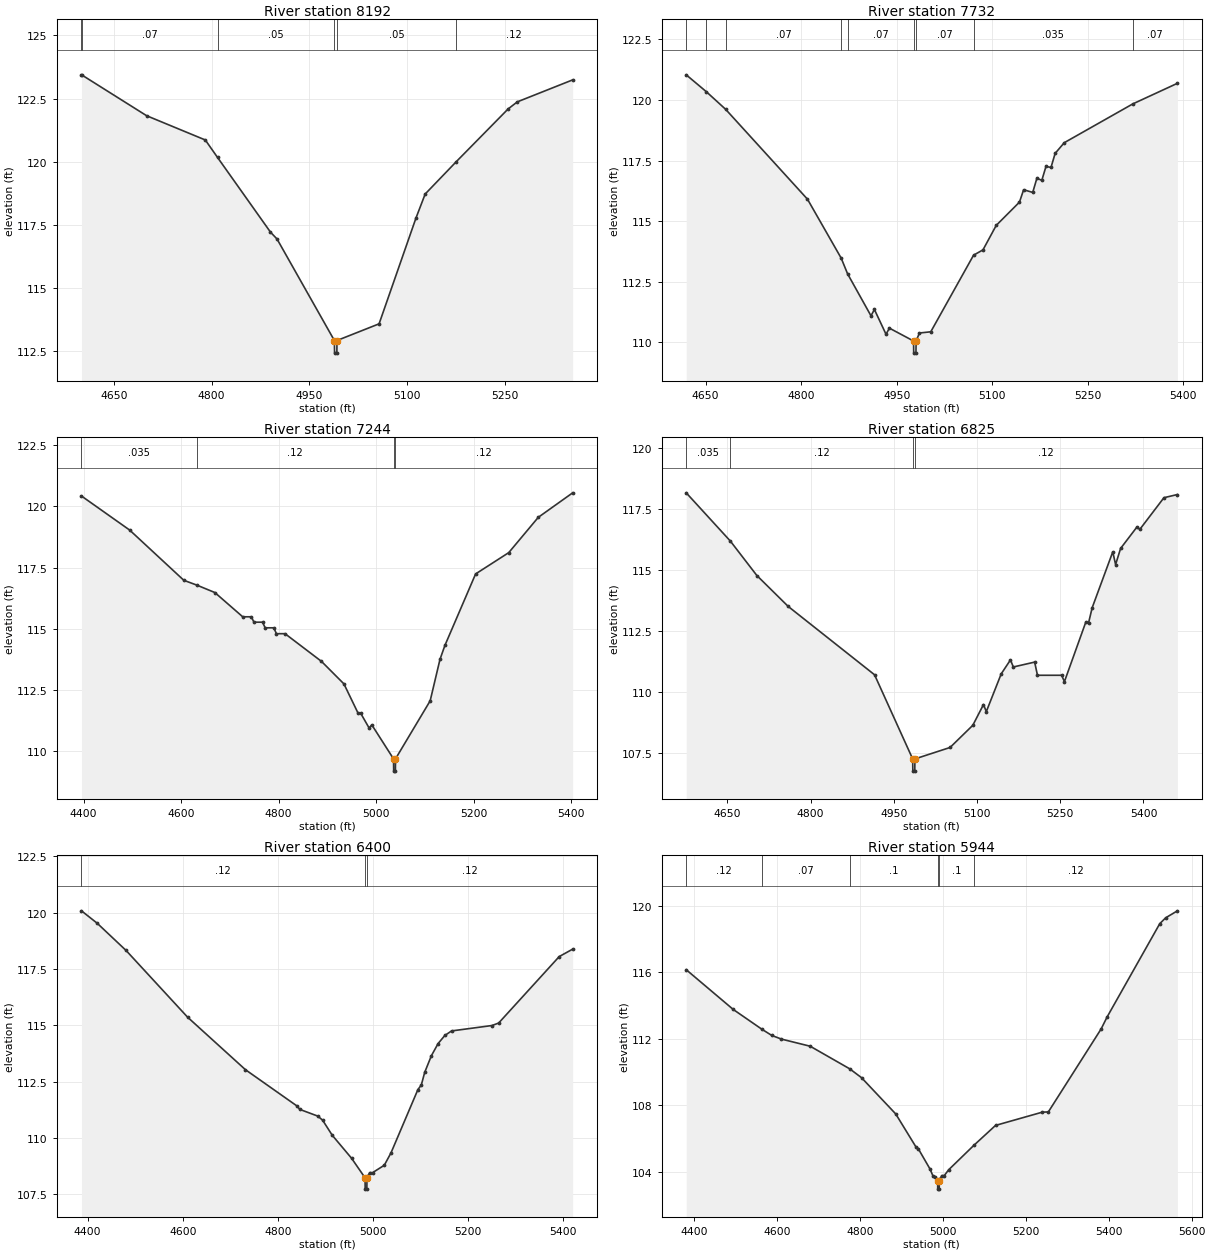
Type RM Length L Ch R = 1 ,8192    ,460,460,460
BEGIN DESCRIPTION:
TRIB A TO TURKEY CREEK 17.0
END DESCRIPTION:
XS GIS Cut Line= 3
        2544025.     13462575.03        2544025.       13462175.
      2543774.99     13461924.99
#Sta/Elev= 18
  4600.3  123.44  4600.5  123.44  4700.3  121.82  4790.3  120.86    4809  120.17
  4890.3  117.21  4900.3  116.94  4988.3  112.92  4988.6  112.42  4992.1  112.42
  4992.3  112.92  5056.9  113.58  5113.5  117.77  5127.6  118.72  5174.9  119.99
  5254.9  122.09    5269  122.37  5353.9  123.24
#Mann= 6 ,-1 , 0
  4600.3    .035       0  4600.5     .07       0    4809     .05       0
  4988.3     .05       0  4992.3     .05       0  5174.9     .12       0
Bank Sta=4988.3,4992.3
XS Rating Curve= 0 ,0
Exp/Cntr=0.3,0.1

Type RM Length L Ch R = 1 ,7732    ,488,488,488
BEGIN DESCRIPTION:
TRIB A TO TURKEY CREEK 16.0
END DESCRIPTION:
XS GIS Cut Line= 3
      2544225.01     13462474.97        2544375.       13462125.
      2544074.97     13461874.98
#Sta/Elev= 30
  4619.5  121.04  4650.8  120.35  4681.3  119.62  4809.9  115.91  4862.8  113.48
  4872.9  112.83  4909.6   111.1    4915  111.36  4933.2  110.34  4938.6  110.59
  4976.5  110.06  4976.7  109.56  4980.2  109.56  4980.5  110.06  4985.7  110.39
  5003.5  110.44  5070.7   113.6  5085.5  113.82  5106.3  114.83  5142.8  115.79
  5149.3   116.3  5163.6  116.19  5170.1  116.77  5177.9  116.69  5184.4  117.26
  5192.3  117.22  5198.8   117.8  5213.1  118.24  5320.7  119.84  5390.8  120.69
#Mann= 9 ,-1 , 0
  4619.5     .07       0  4650.8    .035       0  4681.3     .07       0
  4862.8     .12       0  4872.9     .07       0  4976.5     .05       0
  4980.5     .07       0  5070.7    .035       0  5320.7     .07       0
Bank Sta=4976.5,4980.5
XS Rating Curve= 0 ,0
Exp/Cntr=0.3,0.1

Type RM Length L Ch R = 1 ,7244    ,419,419,419
BEGIN DESCRIPTION:
TRIB A TO TURKEY CREEK 15.0
END DESCRIPTION:
XS GIS Cut Line= 3
      2544575.01     13462674.97        2544825.       13462125.
        2544875.     13461725.03
#Sta/Elev= 30
  4395.8  120.42  4494.6  119.03  4605.6  116.98  4632.7  116.78  4669.3  116.48
  4726.4  115.49    4744  115.49  4749.5  115.27    4767  115.27  4772.5  115.04
  4790.1  115.04  4795.6   114.8  4813.2   114.8  4887.9  113.67    4934  112.75
  4962.6  111.57  4968.1  111.56  4985.6  110.95  4991.1  111.08  5035.7  109.69
    5036  109.19  5039.5  109.19  5039.7  109.69  5110.8  112.06  5130.9  113.75
    5141  114.32    5204  117.24    5272  118.11  5332.5  119.55    5403  120.55
#Mann= 4 ,-1 , 0
  4395.8    .035       0  4632.7     .12       0  5035.7     .05       0
  5039.7     .12       0
Bank Sta=5035.7,5039.7
XS Rating Curve= 0 ,0
Exp/Cntr=0.3,0.1

Type RM Length L Ch R = 1 ,6825    ,425,425,425
BEGIN DESCRIPTION:
TRIB A TO TURKEY CREEK 14.0
END DESCRIPTION:
XS GIS Cut Line= 3
        2544775.       13462725.        2545075.       13462425.
      2544975.01     13461975.04
#Sta/Elev= 30
    4576  118.18  4655.6   116.2  4703.3  114.79  4759.9  113.52  4915.4  110.72
  4984.1  107.27  4984.4  106.77  4987.9  106.77  4988.1  107.27  5051.5  107.74
  5092.5  108.65  5111.7   109.5  5116.8  109.21  5143.7  110.76  5160.3  111.33
  5165.5  111.04  5203.9  111.24    5209   110.7  5252.5   110.7  5257.6  110.44
  5296.1  112.88  5301.2  112.86  5307.6  113.47  5344.7  115.76  5349.8  115.24
  5358.8   115.9  5388.3  116.78  5393.4  116.68  5436.9  117.98  5461.2  118.11
#Mann= 4 ,-1 , 0
    4576    .035       0  4655.6     .12       0  4984.1     .05       0
  4988.1     .12       0
Bank Sta=4984.1,4988.1
XS Rating Curve= 0 ,0
Exp/Cntr=0.3,0.1

Type RM Length L Ch R = 1 ,6400    ,456,456,456
BEGIN DESCRIPTION:
TRIB A TO TURKEY CREEK 13.0
END DESCRIPTION:
XS GIS Cut Line= 3
      2545425.01     13462875.04        2545325.       13462275.
      2545024.99     13461974.99
#Sta/Elev= 30
    4387  120.08    4420  119.53  4480.8  118.32  4610.1  115.36  4731.7  113.03
  4840.7  111.41  4845.8  111.27  4883.8  110.97  4893.9  110.79  4914.2  110.12
  4954.8   109.1  4983.2  108.23  4983.4  107.73  4986.9  107.73  4987.2  108.23
  4992.8  108.46  4998.9  108.46  5023.6  108.79  5037.7  109.34  5094.3  112.15
  5101.4  112.35  5108.5  112.91  5122.6  113.65  5136.7  114.19  5150.9  114.55
    5165  114.75  5249.9  114.99    5264   115.1  5391.3  118.05  5419.6  118.38
#Mann= 3 ,-1 , 0
    4387     .12       0  4983.2     .05       0  4987.2     .12       0
Bank Sta=4983.2,4987.2
XS Rating Curve= 0 ,0
Exp/Cntr=0.3,0.1

Type RM Length L Ch R = 1 ,5944    ,228,228,228
BEGIN DESCRIPTION:
TRIB A TO TURKEY CREEK 12.0
END DESCRIPTION:
XS GIS Cut Line= 3
        2545525.       13462675.        2545675.       13462075.
      2545274.97     13461674.97
#Sta/Elev= 30
  4381.5  116.16  4494.9  113.77    4564  112.58  4587.7  112.21  4610.9  111.99
  4680.4  111.56  4775.8   110.2  4804.1  109.67  4886.6  107.49  4935.5   105.5
  4940.7  105.41    4969  104.19  4976.8  103.74  4981.9  103.72  4987.7  103.47
  4987.9  102.97  4991.4  102.97  4991.7  103.47  4997.4  103.78  5003.5  103.78
  5014.1  104.13  5075.7  105.62  5127.2   106.8  5240.4   107.6  5254.5  107.61
  5381.8   112.6    5396  113.31  5523.2  118.93  5537.4  119.28  5565.7   119.7
#Mann= 6 ,-1 , 0
  4381.5     .12       0    4564     .07       0  4775.8      .1       0
  4987.7     .05       0  4991.7      .1       0  5075.7     .12       0
Bank Sta=4987.7,4991.7
XS Rating Curve= 0 ,0
Exp/Cntr=0.3,0.1

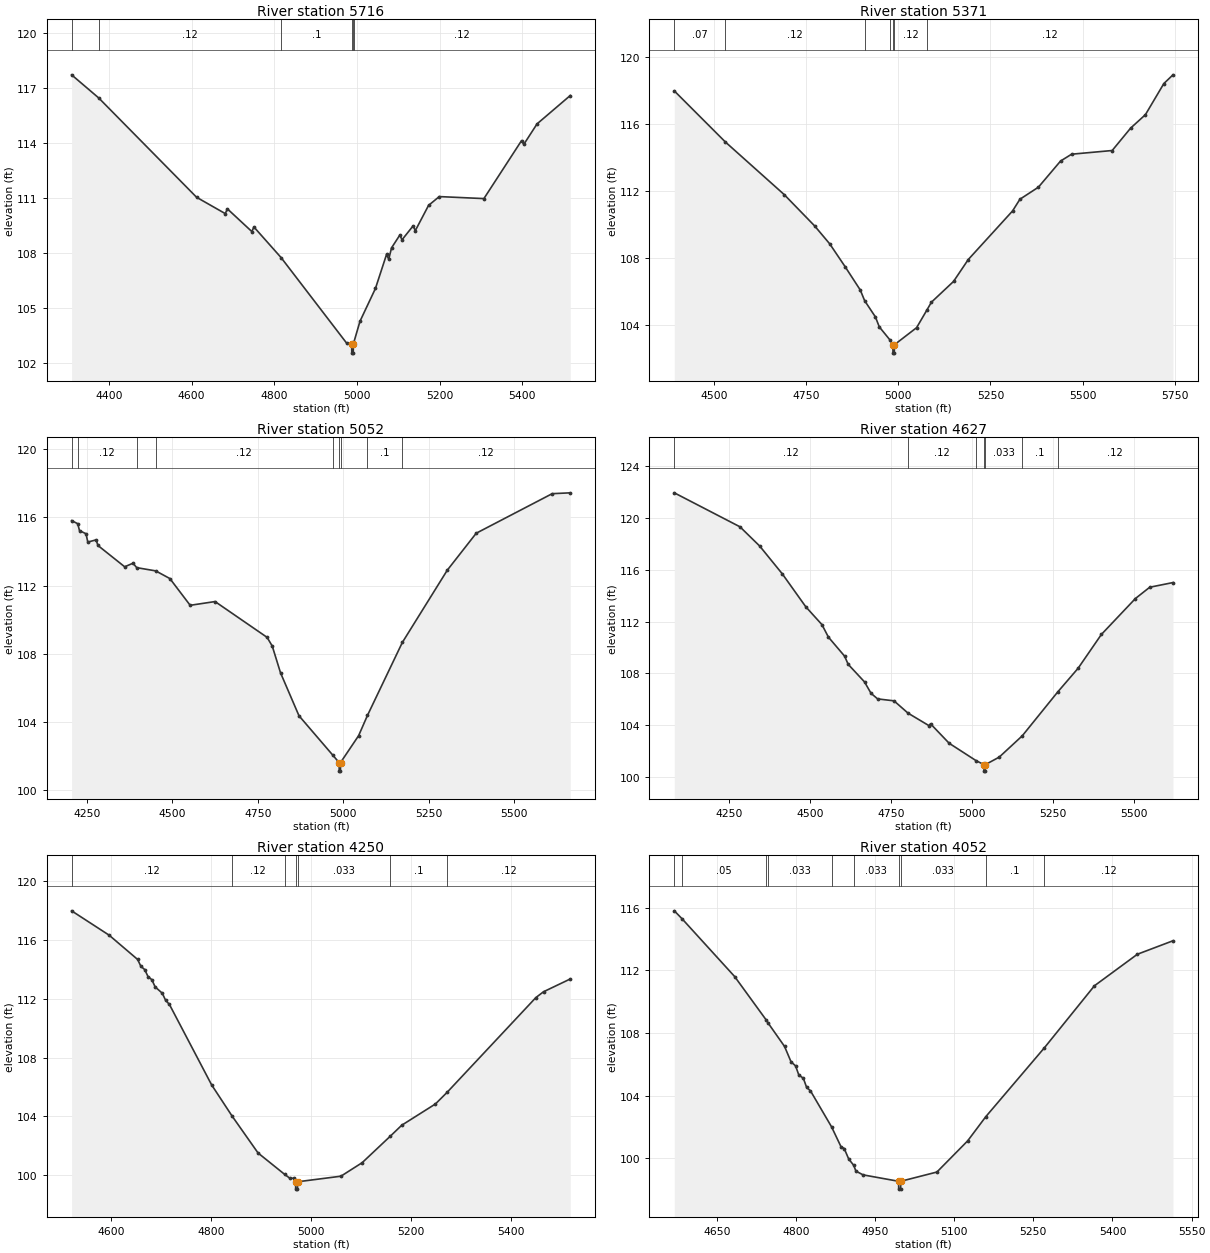
Type RM Length L Ch R = 1 ,5716    ,345,345,345
BEGIN DESCRIPTION:
Mapping XS 10fbe456
END DESCRIPTION:
XS GIS Cut Line= 3
      2545815.04      13462756.7      2545912.27     13462103.91
      2545745.61     13461583.12
#Sta/Elev= 30
  4309.4  117.74  4374.9  116.48    4612  111.05  4681.3  110.16  4686.4  110.42
  4745.6  109.18  4750.6  109.43  4816.3  107.76  4975.2  103.08  4987.2  103.04
  4987.5  102.54    4991  102.54  4991.2  103.04  4992.2  103.11  5007.3  104.28
  5044.7  106.07  5071.6  107.93  5076.9  107.67  5083.7  108.29  5103.8  108.99
    5109  108.73  5135.9  109.49  5141.2  109.23  5173.3  110.61  5199.2  111.09
  5307.2  110.98  5398.4  114.15  5403.7  113.94  5435.8  115.06  5516.2  116.61
#Mann= 6 ,-1 , 0
  4309.4     .07       0  4374.9     .12       0  4816.3      .1       0
  4987.2     .05       0  4991.2      .1       0  4992.2     .12       0
Bank Sta=4987.2,4991.2
XS Rating Curve= 0 ,0
Exp/Cntr=0.3,0.1

Type RM Length L Ch R = 1 ,5371    ,319,319,319
BEGIN DESCRIPTION:
Mapping XS 01e45490
END DESCRIPTION:
XS GIS Cut Line= 3
      2546065.04     13462763.66      2546210.88     13462187.25
      2546231.71     13461430.31
#Sta/Elev= 30
  4393.2  117.97  4531.6  114.92    4691  111.78  4773.5  109.91  4814.7  108.83
    4856  107.48  4897.3  106.08  4909.2  105.44  4938.4  104.47  4948.8  103.88
  4978.4  103.08  4985.8  102.81    4986  102.31  4989.5  102.31  4989.8  102.81
    5050  103.83  5077.3  104.86  5090.1  105.35  5150.1  106.59  5190.1   107.9
  5310.1   110.8  5330.1   111.5  5380.2  112.22  5440.2  113.78  5470.2  114.19
  5580.2  114.41  5630.3  115.75  5670.3  116.55  5720.3  118.41    5745  118.93
#Mann= 7 ,-1 , 0
  4393.2     .07       0  4531.6     .12       0  4909.2      .1       0
  4978.4     .12       0  4985.8     .05       0  4989.8     .12       0
  5077.3     .12       0
Bank Sta=4985.8,4989.8
XS Rating Curve= 0 ,0
Exp/Cntr=0.3,0.1

Type RM Length L Ch R = 1 ,5052    ,425,425,425
BEGIN DESCRIPTION:
Mapping XS 91097e7d
END DESCRIPTION:
XS GIS Cut Line= 3
      2546273.38      13462916.4      2546544.21     13462235.86
      2546377.83     13461528.72
#Sta/Elev= 30
    4205  115.81  4222.8  115.63  4228.2  115.22  4247.1  115.04  4252.4  114.55
  4276.7  114.68  4282.1  114.35  4360.3   113.1  4384.6  113.31  4395.5  113.05
    4451  112.86  4492.5  112.41  4551.9  110.84  4624.7  111.06  4776.9  108.96
    4792  108.45  4816.2  106.88  4870.2  104.36  4968.6  102.06  4987.7  101.61
    4988  101.11  4991.5  101.11  4991.7  101.61  5044.7  103.19  5070.6  104.38
  5172.6  108.66  5304.1   112.9  5388.8  115.07    5611  117.39  5663.9  117.44
#Mann= 9 ,-1 , 0
    4205     .07       0  4222.8     .12       0  4395.5     .07       0
    4451     .12       0  4968.6     .12       0  4987.7     .05       0
  4991.7     .12       0  5070.6      .1       0  5172.6     .12       0
Bank Sta=4987.7,4991.7
XS Rating Curve= 0 ,0
Exp/Cntr=0.3,0.1

Type RM Length L Ch R = 1 ,4627    ,377,377,377
BEGIN DESCRIPTION:
Mapping XS 540f1bdb
END DESCRIPTION:
XS GIS Cut Line= 3
      2547002.55     13463055.34      2546863.66     13462173.36
      2546565.83     13461598.48
#Sta/Elev= 30
  4079.7  121.93  4282.5  119.31  4343.3  117.83  4413.3  115.68  4485.9  113.14
  4535.6  111.77  4555.8   110.8  4605.9  109.33  4616.6  108.71  4667.2  107.35
  4687.4  106.47  4707.7  106.04  4758.3  105.89  4801.7  104.94  4866.1  103.98
  4871.1  104.12  4928.6  102.62  5011.7  101.28  5036.3  100.97  5036.5  100.47
    5040  100.47  5040.3  100.97  5083.3  101.55  5154.4  103.19  5263.5  106.56
  5326.9   108.4  5398.9  111.01    5504  113.78  5548.2  114.65    5620  115.01
#Mann= 7 ,-1 , 0
  4079.7     .12       0  4801.7     .12       0  5011.7    .033       0
  5036.3     .05       0  5040.3    .033       0  5154.4      .1       0
  5263.5     .12       0
Bank Sta=5036.3,5040.3
XS Rating Curve= 0 ,0
Exp/Cntr=0.3,0.1

Type RM Length L Ch R = 1 ,4250    ,198,198,198
BEGIN DESCRIPTION:
Mapping XS 522e6179
END DESCRIPTION:
XS GIS Cut Line= 3
      2547440.08     13462235.89      2547148.38     13461902.52
      2546676.16     13461610.86
#Sta/Elev= 30
  4520.2     118  4595.4  116.34  4652.3  114.69  4658.9  114.22  4666.5     114
  4673.2  113.52  4680.8  113.31  4687.4  112.82  4701.7  112.39  4708.3  111.91
  4715.9  111.63  4800.4  106.15  4841.5  104.02  4893.4  101.51  4946.4  100.06
    4957   99.79  4965.6   99.79  4968.4   99.55  4968.7   99.05  4972.3   99.05
  4972.5   99.55  5059.2   99.93  5101.7  100.85  5158.2  102.66  5180.9   103.4
  5248.4  104.85  5271.7  105.64  5449.3  112.09  5464.7  112.49  5518.2  113.36
#Mann= 7 ,-1 , 0
  4520.2     .12       0  4841.5     .12       0  4946.4    .033       0
  4968.4    .033       0  4972.5    .033       0  5158.2      .1       0
  5271.7     .12       0
Bank Sta=4968.4,4972.5
XS Rating Curve= 0 ,0
Exp/Cntr=0.3,0.1

Type RM Length L Ch R = 1 ,4052    ,428,428,428
BEGIN DESCRIPTION:
TRIB A TO TURKEY CREEK 8.0
END DESCRIPTION:
XS GIS Cut Line= 3
      2547474.98     13462074.97        2547225.       13461725.
      2546774.97     13461474.98
#Sta/Elev= 30
  4569.7  115.79  4584.2  115.29    4684   111.6    4744  108.82  4746.9  108.66
  4778.6  107.14  4790.9  106.16  4799.5   105.9  4805.6  105.32  4814.2  105.11
  4820.4  104.53  4827.7  104.31  4867.7  102.01  4885.5  100.75  4891.6  100.63
  4900.2   99.96  4909.6   99.56  4913.8   99.19  4927.3   98.95  4994.7   98.54
  4994.9   98.04  4998.5   98.04  4998.8   98.54  5067.3   99.13  5125.6  101.12
  5159.9  102.66  5270.6  107.04  5365.8  111.01  5447.1  113.02  5514.6  113.88
#Mann= 10 ,-1 , 0
  4569.7     .12       0  4584.2     .05       0    4744     .12       0
  4746.9    .033       0  4867.7     .12       0  4909.6    .033       0
  4994.7    .033       0  4998.8    .033       0  5159.9      .1       0
  5270.6     .12       0
Bank Sta=4994.7,4998.8
XS Rating Curve= 0 ,0
Exp/Cntr=0.3,0.1

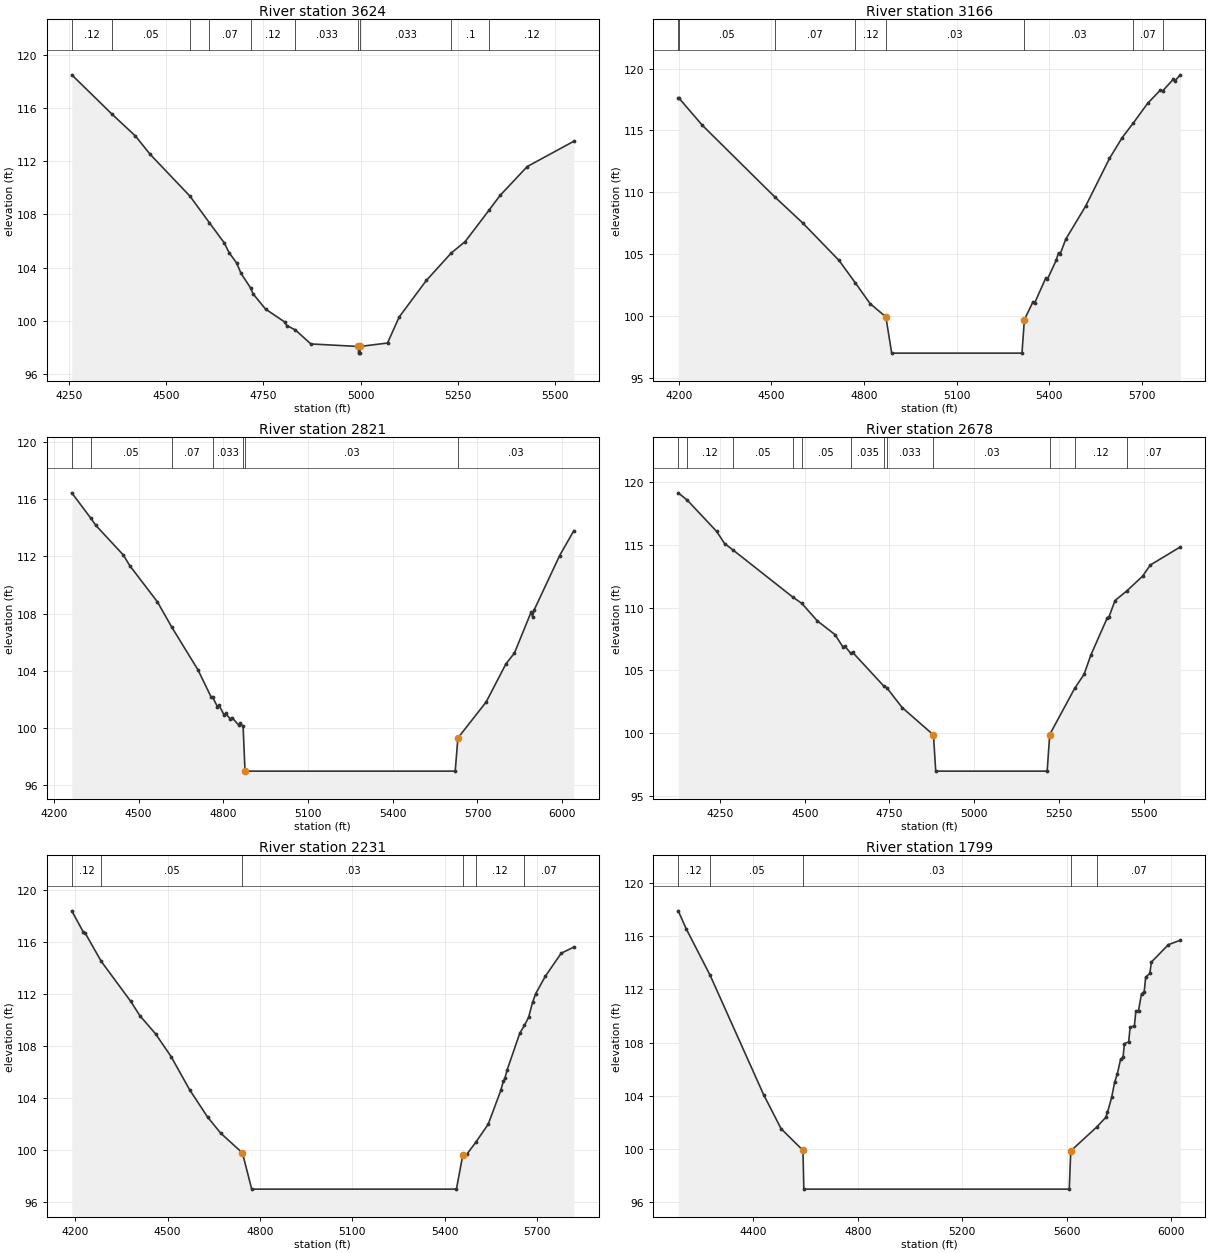
Type RM Length L Ch R = 1 ,3624    ,458,458,458
BEGIN DESCRIPTION:
TRIB A TO TURKEY CREEK 7.0
END DESCRIPTION:
XS GIS Cut Line= 3
        2547675.       13462075.        2547425.       13461375.
        2546875.       13461375.
#Sta/Elev= 30
  4256.2  118.48  4359.7  115.53  4420.3  113.88    4458  112.51  4560.8  109.36
  4610.9  107.36  4649.1  105.85  4661.3  105.13  4680.9  104.34  4692.1  103.57
  4716.7  102.47  4723.4  102.02  4755.3  100.88  4804.7   99.91    4810   99.64
  4831.8   99.32  4872.1   98.26  4994.7   98.07    4995   97.57  4998.6   97.57
  4998.9   98.07  5069.5   98.33  5099.5  100.28  5169.5  103.03  5233.6  105.09
  5269.5  105.95  5331.8  108.34  5359.5  109.42  5429.5  111.59  5549.5  113.49
#Mann= 10 ,-1 , 0
  4256.2     .12       0  4359.7     .05       0  4560.8     .12       0
  4610.9     .07       0  4716.7     .12       0  4831.8    .033       0
  4994.7    .033       0  4998.9    .033       0  5233.6      .1       0
  5331.8     .12       0
Bank Sta=4994.7,4998.9
XS Rating Curve= 0 ,0
Exp/Cntr=0.3,0.1

Type RM Length L Ch R = 1 ,3166    ,345,345,345
BEGIN DESCRIPTION:
TRIB A TO TURKEY CREEK 6.0
END DESCRIPTION:
XS GIS Cut Line= 3
        2547775.     13462025.01        2547825.       13461225.
        2547625.     13460424.99
#Sta/Elev= 30
  4198.4  117.63  4201.8  117.59  4276.1  115.43  4511.1  109.63  4601.7  107.52
  4719.4  104.49  4772.3  102.67  4819.6  101.01  4870.9   99.93  4889.8      97
  5311.8      97  5319.5    99.7  5347.9  101.17    5353  101.06  5389.1  103.09
  5394.2  102.97  5422.6  104.51  5430.3  105.12  5435.5  105.01  5453.5  106.21
  5517.9  108.88  5595.2  112.74  5636.5  114.43  5672.2   115.6  5718.9   117.2
  5760.2  118.27  5767.4   118.2  5801.4  119.13  5806.6     119  5824.6   119.5
#Mann= 8 ,-1 , 0
  4198.4     .12       0  4201.8     .05       0  4511.1     .07       0
  4772.3     .12       0  4870.9     .03       0  5319.5     .03       0
  5672.2     .07       0  5767.4     .12       0
Bank Sta=4870.9,5319.5
XS Rating Curve= 0 ,0
Exp/Cntr=0.3,0.1

Type RM Length L Ch R = 1 ,2821    ,143,143,143
BEGIN DESCRIPTION:
Mapping XS fb4fb330
END DESCRIPTION:
XS GIS Cut Line= 3
      2547834.29     13461996.61       2548132.9     13461343.83
       2548094.7     13460284.76
#Sta/Elev= 30
  4263.7  116.43    4331  114.66  4348.8  114.16  4446.3  112.09  4469.3  111.34
  4566.9  108.82  4616.9  107.08  4710.5  104.07  4756.5   102.2  4762.7  102.15
  4779.5   101.5    4785  101.61  4802.6  100.93  4808.1  101.03  4825.6  100.63
  4831.1  100.74  4854.1  100.23  4859.6  100.34  4870.3  100.14  4877.1      97
  5621.3      97  5630.8   99.31  5730.9  101.83  5800.9  104.49  5830.9  105.24
  5890.1  108.11  5895.1  107.78    5901  108.26    5991  112.05  6041.3  113.79
#Mann= 7 ,-1 , 0
  4263.7     .12       0    4331     .05       0  4616.9     .07       0
  4762.7    .033       0  4870.3     .03       0  4877.1     .03       0
  5630.8     .03       0
Bank Sta=4877.1,5630.8
XS Rating Curve= 0 ,0
Exp/Cntr=0.3,0.1

Type RM Length L Ch R = 1 ,2678    ,447,447,447
BEGIN DESCRIPTION:
TRIB A TO TURKEY CREEK 5.0
END DESCRIPTION:
XS GIS Cut Line= 3
        2547925.       13462125.        2548275.       13461325.
        2548375.     13460724.99
#Sta/Elev= 30
  4126.7  119.12  4153.7  118.53  4240.1  116.05  4263.5  115.09  4287.8  114.59
  4465.8  110.81  4491.1  110.34  4537.2  108.94  4589.4  107.85  4612.8  106.86
  4618.3  106.93    4636  106.36  4641.7  106.43    4734  103.74  4742.3  103.62
  4787.5  102.05  4879.8   99.88  4886.5      97  5215.3      97  5222.9   99.91
  5296.5  103.58  5324.3   104.7  5344.6  106.25  5392.8  109.19  5397.8  109.27
  5415.6  110.56  5450.5  111.33  5496.7  112.49  5519.5  113.38  5608.2  114.82
#Mann= 12 ,-1 , 0
  4126.7     .05       0  4153.7     .12       0  4287.8     .05       0
  4465.8     .07       0  4491.1     .05       0    4636    .035       0
    4734     .07       0  4742.3    .033       0  4879.8     .03       0
  5222.9     .03       0  5296.5     .12       0  5450.5     .07       0
Bank Sta=4879.8,5222.9
XS Rating Curve= 0 ,0
Exp/Cntr=0.3,0.1

Type RM Length L Ch R = 1 ,2231    ,432,432,432
BEGIN DESCRIPTION:
TRIB A TO TURKEY CREEK 4.0
END DESCRIPTION:
XS GIS Cut Line= 3
        2548525.     13462374.98        2548625.       13461575.
      2548425.01     13460775.03
#Sta/Elev= 30
  4188.7  118.43  4226.5  116.78  4231.5  116.75  4284.4  114.54  4380.2  111.46
  4410.4  110.34  4460.8  108.96  4511.2  107.21  4571.6  104.65  4629.6  102.56
  4672.4  101.31    4743   99.79  4773.2      97  5438.1      97  5458.8   99.62
  5471.6   99.67  5500.7   100.6  5541.2  101.99  5582.4  104.61  5590.2  105.29
  5595.3  105.52  5603.1   106.2  5644.3  109.03  5658.9   109.6  5672.6  110.23
  5685.5   111.4  5695.8  112.06  5726.8  113.39  5778.3  115.16  5819.5  115.64
#Mann= 6 ,-1 , 0
  4188.7     .12       0  4284.4     .05       0    4743     .03       0
  5458.8     .03       0  5500.7     .12       0  5658.9     .07       0
Bank Sta=4743,5458.8
XS Rating Curve= 0 ,0
Exp/Cntr=0.3,0.1

Type RM Length L Ch R = 1 ,1799    ,850,850,850
BEGIN DESCRIPTION:
TRIB A TO TURKEY CREEK 3.0
END DESCRIPTION:
XS GIS Cut Line= 3
      2548574.98     13462375.03        2548975.       13461575.
      2548475.01     13460675.02
#Sta/Elev= 30
  4111.7   117.9  4142.5  116.54  4233.4  113.08  4438.8   104.1  4505.8  101.54
  4589.7   99.91    4593      97  5610.2      97  5615.9   99.87  5714.7  101.65
  5749.7  102.38  5756.6  102.76  5772.6  103.89  5784.1  105.03  5794.4  105.66
  5806.9  106.75  5816.1  106.89  5821.8  107.93  5837.8  108.06  5843.5  109.18
  5859.6  109.24  5865.3  110.36  5875.6  110.41    5887  111.67  5897.3  111.81
    5903  112.92    5919   113.2  5924.8  114.05    5990  115.36  6035.7  115.69
#Mann= 5 ,-1 , 0
  4111.7     .12       0  4233.4     .05       0  4589.7     .03       0
  5615.9     .03       0  5714.7     .07       0
Bank Sta=4589.7,5615.9
XS Rating Curve= 0 ,0
Exp/Cntr=0.3,0.1

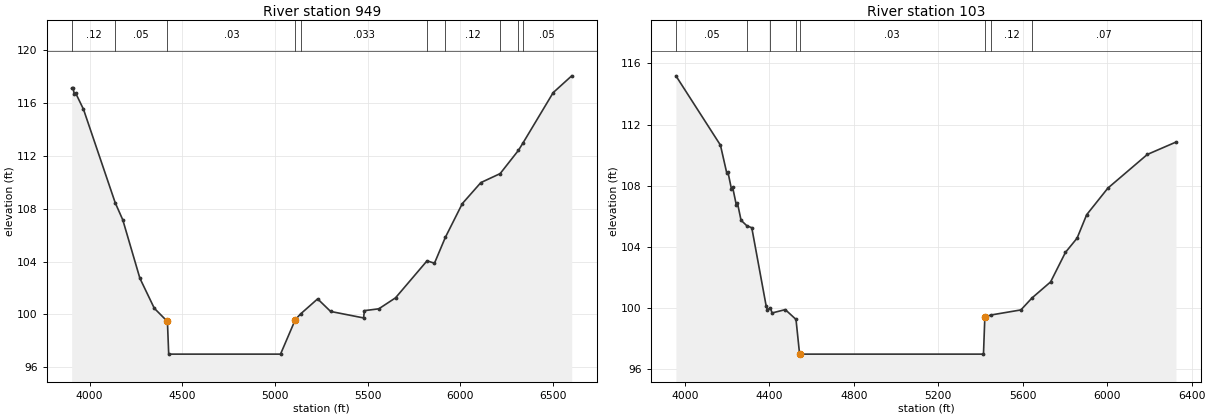
Type RM Length L Ch R = 1 ,949     ,846,846,846
BEGIN DESCRIPTION:
TRIB A TO TURKEY CREEK 2.0
END DESCRIPTION:
XS GIS Cut Line= 3
      2548675.02     13462624.98        2549425.       13461825.
        2549475.     13460225.04
#Sta/Elev= 30
  3903.3  117.11  3910.4  117.17  3917.2   116.7  3924.5  116.76    3967  115.53
    4138  108.46    4179  107.16  4271.3  102.74    4349  100.47  4419.8   99.47
  4426.7      97  5029.9      97  5109.9   99.62  5138.8  100.05    5230  101.18
    5300  100.23  5477.6   99.74  5482.6  100.29  5560.1  100.43  5650.2  101.26
  5820.1  104.06  5860.3  103.88  5918.7  105.83  6010.4  108.39  6110.4  109.98
  6214.5  110.66  6313.1  112.42  6336.9  112.96  6500.6  116.79  6600.6  118.06
#Mann= 10 ,-1 , 0
  3903.3     .12       0    4138     .05       0  4419.8     .03       0
  5109.9     .03       0  5138.8    .033       0  5820.1     .05       0
  5918.7     .12       0  6214.5     .05       0  6313.1     .07       0
  6336.9     .05       0
Bank Sta=4419.8,5109.9
XS Rating Curve= 0 ,0
Exp/Cntr=0.3,0.1

Type RM Length L Ch R = 1 ,103     ,0,0,0
BEGIN DESCRIPTION:
TRIB A TO TURKEY CREEK 1.0
END DESCRIPTION:
XS GIS Cut Line= 4
        2548925.       13462775.      2549754.28     13462376.48
      2549920.95       13462125.      2549817.88     13460983.81
#Sta/Elev= 30
  3958.2  115.19    4169  110.66  4198.7  108.85  4204.2  108.92  4221.3  107.78
  4226.9   107.9    4244  106.76  4249.5  106.88  4266.6  105.75    4294  105.39
  4317.4  105.26  4385.3  100.16  4390.9   99.89  4405.2  100.03  4413.5   99.69
  4475.9   99.91  4526.7   99.27  4543.8      97  5414.4      97  5420.9   99.43
    5451   99.56  5591.6   99.89    5644  100.67  5732.2  101.72  5802.5  103.65
  5857.6  104.58  5902.9  106.11  6003.3  107.85  6190.1  110.05  6325.8  110.86
#Mann= 8 ,-1 , 0
  3958.2     .05       0    4294     .12       0  4405.2    .033       0
  4526.7     .03       0  4543.8     .03       0  5420.9     .03       0
    5451     .12       0    5644     .07       0
Bank Sta=4543.8,5420.9
XS Rating Curve= 0 ,0
Exp/Cntr=0.3,0.1

Chan Stop Cuts=-1
Use User Specified Reach Order=0
Composite Channel Slope=5