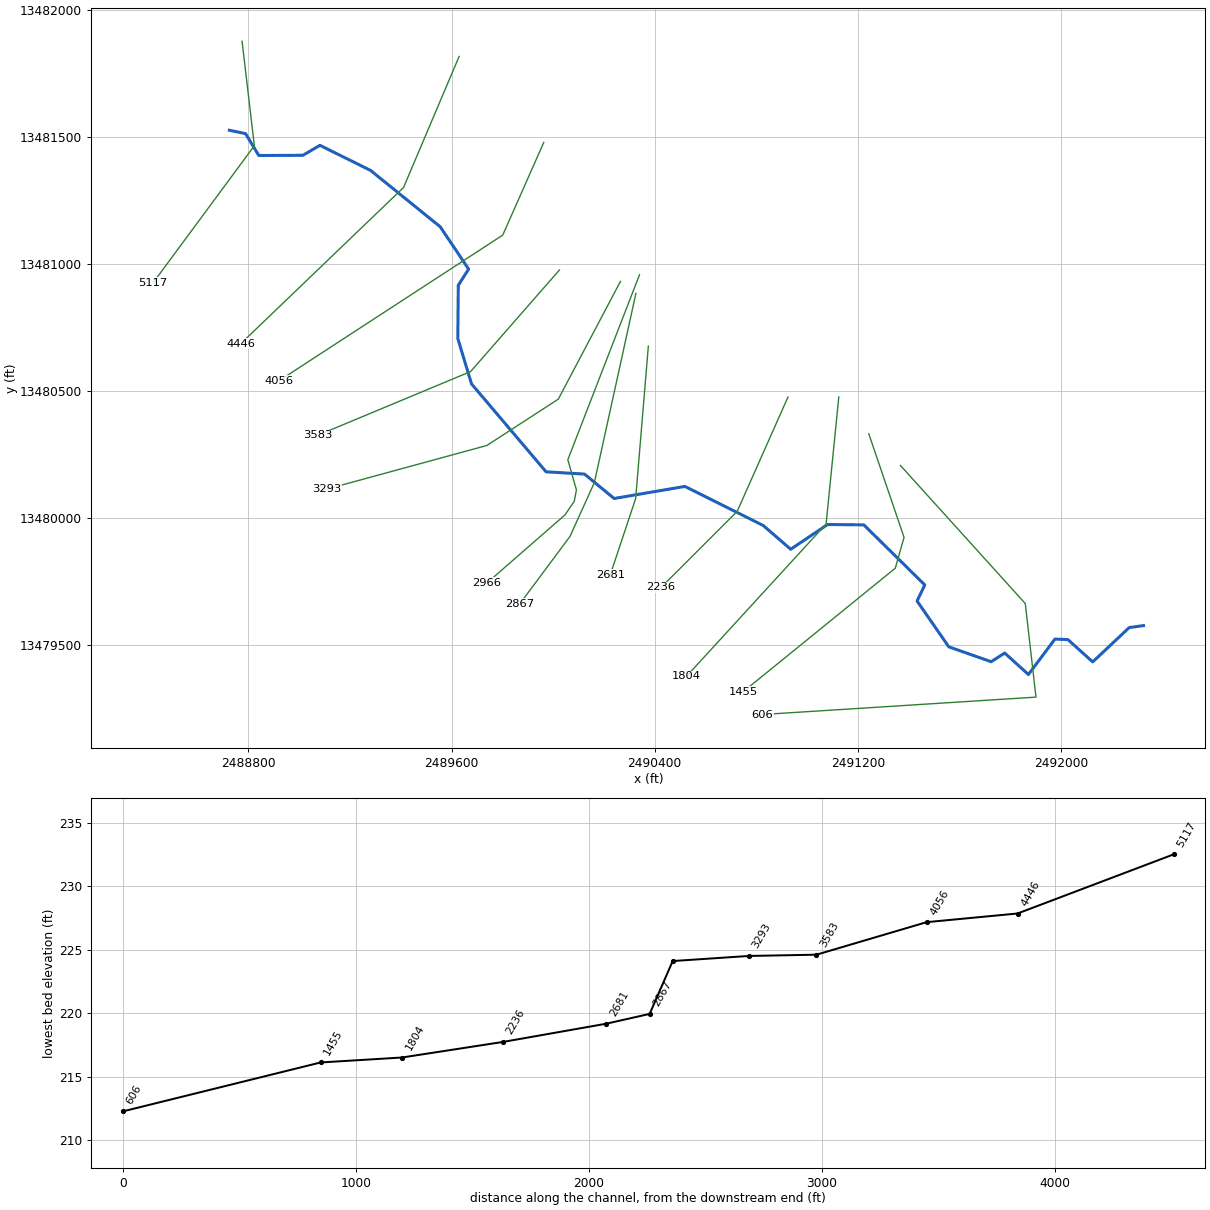
--- TRIB TO TRIB 5 TO PERDIDO CREEK.prj (project) ---

Proj Title=TRIB TO TRIB 5 TO PERDIDO CREEK Base Level Engineering
Current Plan=p01
Default Exp/Contr=0.3,0.1
English Units
Geom File=g01
Flow File=f01
Plan File=p01
Y Axis Title=Elevation
X Axis Title(PF)=Main Channel Distance
X Axis Title(XS)=Station
BEGIN DESCRIPTION:
TRIB TO TRIB 5 TO PERDIDO CREEK
END DESCRIPTION:
DSS Export Rating Curves= 0
DSS Export Rating Curve Sorted= 0
DSS Export Volume Flow Curves= 0
DXF OffsetX= 0
DXF OffsetY= 0
DXF ScaleX= 1
DXF ScaleY= 10

--- TRIB TO TRIB 5 TO PERDIDO CREEK.p01 (plan) ---

Plan Title=Multiple Run
Short Identifier=Multiple
Geom File=g01
Flow File=f01
Subcritical Flow
K Sum by GR= 0
Std Step Tol= 0.01
Critical Tol= 0.01
Num of Std Step Trials= 20
Max Error Tol= 0.3
Flow Tol Ratio= 0.001
Split Flow NTrial= 30
Split Flow Tol= 0.02
Split Flow Ratio= 0.02
Log Output Level= 0
Friction Slope Method= 1
Unsteady Friction Slope Method= 2
Unsteady Bridges Friction Slope Method= 1
Parabolic Critical Depth
Global Vel Dist=  1 , 1 , 1
Global Log Level= 0
CheckData=True
Encroach Param= -1, 0, 0, 0
BEGIN DESCRIPTION:
Multiple Run
END DESCRIPTION:

--- TRIB TO TRIB 5 TO PERDIDO CREEK.f01 (steady flow) ---

Flow Title=Multiple
Number of Profiles=7
Profile Names=10-year,25-year,50-year,1pct_min,100-year,1pct_plu,500-year
River Rch & RM= TRIB TO TRIB 5 T,Reach-1,5117
     520     827    1102     712    1420    2834    2330
River Rch & RM= TRIB TO TRIB 5 T,Reach-1,3293
     736    1195    1612    1052    2099    4188    3522
Boundary for River Rch & Prof#=TRIB TO TRIB 5 T,Reach-1,1
Up Type=0
Dn Type=3
Dn Slope=0.005
Boundary for River Rch & Prof#=TRIB TO TRIB 5 T,Reach-1,2
Up Type=0
Dn Type=3
Dn Slope=0.005
Boundary for River Rch & Prof#=TRIB TO TRIB 5 T,Reach-1,3
Up Type=0
Dn Type=3
Dn Slope=0.005
Boundary for River Rch & Prof#=TRIB TO TRIB 5 T,Reach-1,4
Up Type=0
Dn Type=3
Dn Slope=0.005
Boundary for River Rch & Prof#=TRIB TO TRIB 5 T,Reach-1,5
Up Type=0
Dn Type=3
Dn Slope=0.005
Boundary for River Rch & Prof#=TRIB TO TRIB 5 T,Reach-1,6
Up Type=0
Dn Type=3
Dn Slope=0.005
Boundary for River Rch & Prof#=TRIB TO TRIB 5 T,Reach-1,7
Up Type=0
Dn Type=3
Dn Slope=0.005

--- TRIB TO TRIB 5 TO PERDIDO CREEK.g01 (geometry) ---

Geom Title=Existing Conditions
Program Version=4.10

River Reach=TRIB TO TRIB 5 T,Reach-1
Reach XY= 30
        2488725.       13481525.      2488788.74     13481511.63
      2488840.82     13481425.66      2489014.56     13481426.38
      2489081.62     13481465.59      2489281.06     13481366.86
      2489555.23     13481145.13      2489667.19     13480978.41
      2489626.39     13480914.57      2489624.64     13480704.85
      2489678.61      13480526.5       2489972.3     13480180.36
      2490123.53     13480171.44      2490240.17     13480075.37
      2490519.03     13480122.86      2490827.29     13479969.15
      2490935.64     13479875.56      2491080.86     13479972.94
      2491223.53     13479971.47      2491463.76       13479735.
      2491433.25     13479671.77      2491558.21     13479491.44
       2491725.1      13479432.8      2491778.34     13479466.98
      2491871.85     13479382.54      2491976.43     13479521.99
      2492027.27     13479519.92        2492125.     13479432.08
      2492268.79     13479567.24        2492325.       13479575.

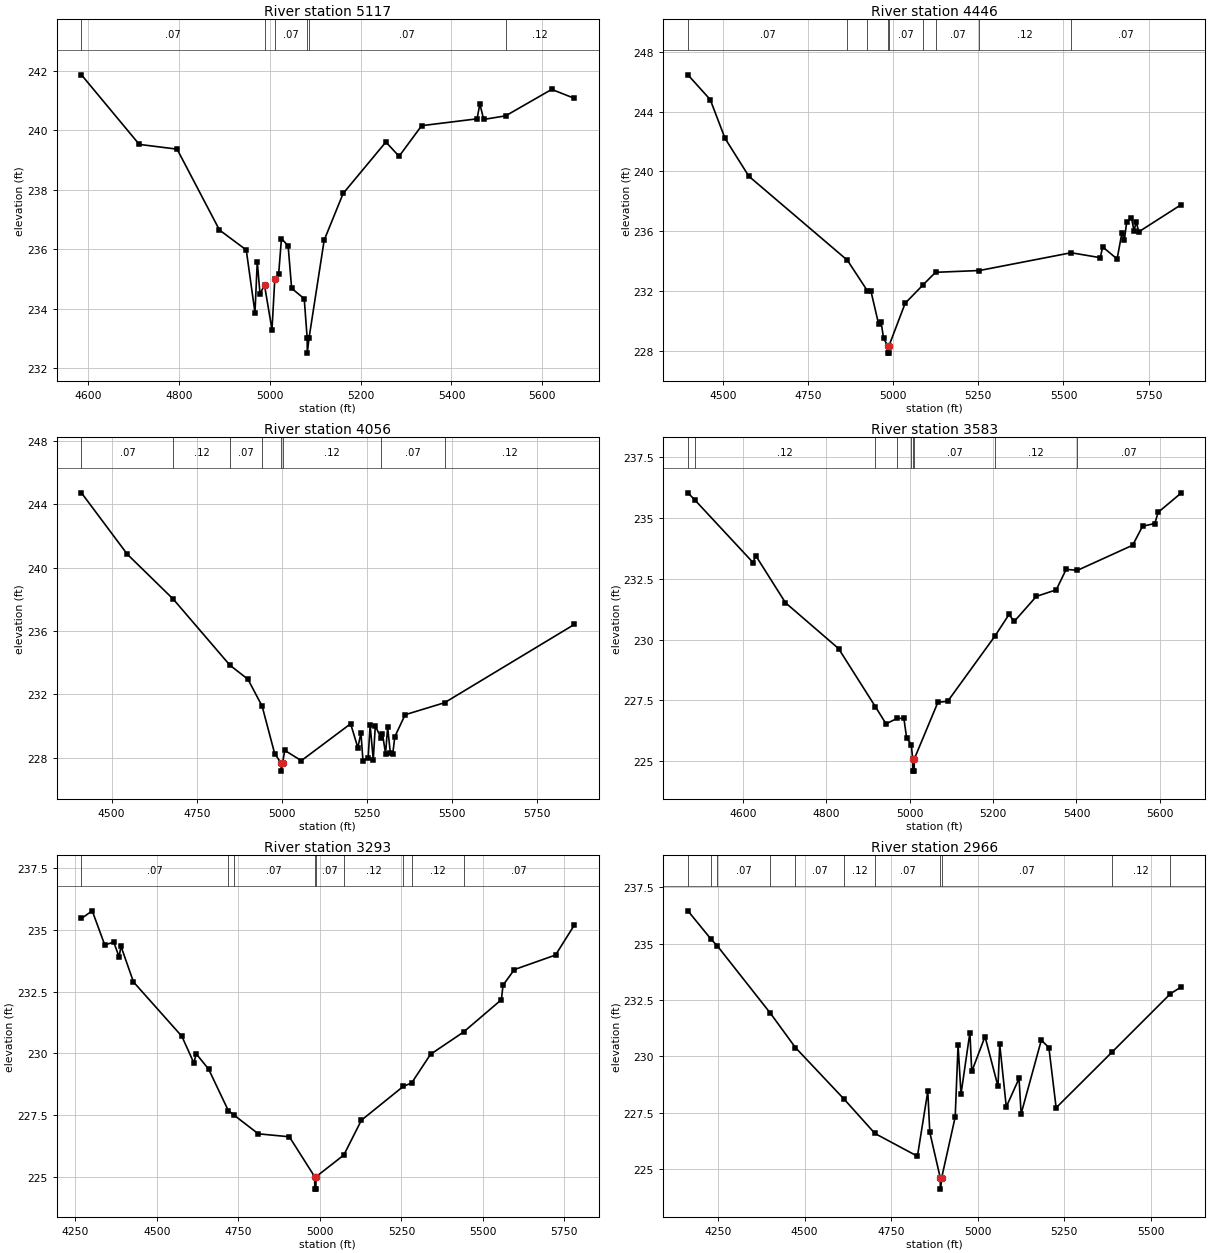
Type RM Length L Ch R = 1 ,5117    ,671,671,671
BEGIN DESCRIPTION:
TRIB TO TRIB 5 TO PERDIDO CREEK 8.0
END DESCRIPTION:
XS GIS Cut Line= 3
        2488775.       13481875.      2488823.27     13481463.93
      2488425.01     13480925.02
#Sta/Elev= 30
  4586.1  241.86  4713.3  239.52  4796.5  239.36  4889.7  236.64  4948.6  235.97
  4967.8  233.86  4972.8  235.58  4978.8   234.5  4988.8  234.78  5005.2  233.29
  5011.4     235  5019.8  235.15    5026  236.35  5040.7  236.11  5048.4  234.68
  5076.1  234.33  5082.6     233  5082.8   232.5  5086.6     233    5120   236.3
  5161.7  237.87  5255.7   239.6  5284.7  239.12  5334.4  240.15  5456.2  240.38
  5462.4  240.88  5470.8  240.36    5519  240.48  5620.4  241.37  5670.1  241.07
#Mann= 6 ,-1 , 0
  4586.1     .07       0  4988.8     .05       0  5011.4     .07       0
  5082.6     .07       0  5086.6     .07       0    5519     .12       0
Bank Sta=4988.8,5011.4
XS Rating Curve= 0 ,0
Exp/Cntr=0.3,0.1

Type RM Length L Ch R = 1 ,4446    ,390,390,390
BEGIN DESCRIPTION:
Mapping XS 9664abb0
END DESCRIPTION:
XS GIS Cut Line= 3
      2489629.72     13481815.37      2489410.97     13481299.74
      2488770.33     13480685.13
#Sta/Elev= 30
  4396.7  246.47  4462.3  244.81  4505.7  242.22  4575.8  239.68  4865.1  234.06
  4924.1  232.01  4934.2  232.01  4956.7  229.81  4964.5   229.9  4971.4  228.84
  4983.6  228.34  4983.8  227.84  4987.3  227.84  4987.6  228.34    5035  231.18
  5088.4  232.43  5124.2  233.25  5253.1  233.37  5522.5  234.56    5608  234.23
  5615.2  234.95  5657.6  234.14  5671.8  235.91  5678.7  235.38  5685.7  236.62
  5699.8  236.91    5707  236.04  5713.9  236.61  5721.2  235.96  5844.6  237.76
#Mann= 9 ,-1 , 0
  4396.7     .07       0  4865.1     .12       0  4924.1     .07       0
  4983.6     .05       0  4987.6     .07       0  5088.4     .12       0
  5124.2     .07       0  5253.1     .12       0  5522.5     .07       0
Bank Sta=4983.6,4987.6
XS Rating Curve= 0 ,0
Exp/Cntr=0.3,0.1

Type RM Length L Ch R = 1 ,4056    ,473,473,473
BEGIN DESCRIPTION:
Mapping XS d05adf38
END DESCRIPTION:
XS GIS Cut Line= 3
      2489963.06     13481476.83       2489801.6     13481112.24
      2488921.88     13480539.64
#Sta/Elev= 30
  4411.1  244.73    4546  240.85  4681.3  238.01  4847.3  233.85  4900.4  232.96
  4942.1  231.26  4978.9  228.27    4998  227.66  4998.2  227.16    5002  227.66
  5008.6  228.47  5057.3  227.82  5202.2  230.15  5223.4  228.64  5232.5  229.57
  5238.4  227.83  5253.6  227.98  5259.5  230.06  5268.7  227.88  5274.7  230.02
  5291.5  229.25  5295.8   229.5  5304.9  228.26  5310.9  229.93  5318.9  228.32
    5326  228.25    5332  229.33  5362.3  230.72  5478.3  231.48  5859.5  236.42
#Mann= 8 ,-1 , 0
  4411.1     .07       0  4681.3     .12       0  4847.3     .07       0
  4942.1     .12       0    4998     .05       0    5002     .12       0
  5291.5     .07       0  5478.3     .12       0
Bank Sta=4998,5002
XS Rating Curve= 0 ,0
Exp/Cntr=0.3,0.1

Type RM Length L Ch R = 1 ,3583    ,290,290,290
BEGIN DESCRIPTION:
TRIB TO TRIB 5 TO PERDIDO CREEK 6.0
END DESCRIPTION:
XS GIS Cut Line= 3
      2490024.97     13480974.96        2489675.       13480575.
      2489074.96     13480324.98
#Sta/Elev= 30
  4468.5  236.02  4485.5  235.72  4624.6  233.16  4631.2  233.44  4702.4  231.51
  4829.6  229.63  4917.7  227.25  4943.5  226.54  4969.5  226.76  4986.2  226.77
  4992.8  225.97  5004.1  225.68  5007.2   225.1  5007.4   224.6  5010.9   224.6
  5011.2   225.1  5067.7  227.42  5091.5  227.47  5204.5  230.14  5238.3  231.03
  5250.7  230.74  5303.8  231.77  5351.5  232.04  5375.3  232.88  5402.4  232.84
  5534.6  233.87  5558.4  234.65  5587.7  234.76  5595.8  235.22    5650     236
#Mann= 9 ,-1 , 0
  4468.5     .07       0  4485.5     .12       0  4917.7     .07       0
  4969.5     .12       0  5004.1     .07       0  5007.2     .05       0
  5011.2     .07       0  5204.5     .12       0  5402.4     .07       0
Bank Sta=5007.2,5011.2
XS Rating Curve= 0 ,0
Exp/Cntr=0.3,0.1

Type RM Length L Ch R = 1 ,3293    ,327,327,327
BEGIN DESCRIPTION:
Mapping XS 44388176
END DESCRIPTION:
XS GIS Cut Line= 4
      2490265.14     13480929.95      2490020.35      13480466.4
       2489739.1     13480284.11      2489109.47      13480112.4
#Sta/Elev= 30
  4268.5  235.46  4301.6  235.77    4340  234.39  4367.7   234.5  4384.1   233.9
  4389.7  234.34  4428.1  232.89  4576.5  230.69  4613.4  229.61  4620.6  229.98
  4658.6  229.36  4719.1  227.68  4735.3  227.51    4811  226.74  4906.3  226.62
  4984.1     225  4984.3   224.5  4987.8   224.5  4988.1     225  5073.4  225.88
  5127.3  227.29  5255.8  228.66  5281.6   228.8  5339.4  229.96  5440.6  230.86
  5556.7  232.17  5561.9  232.76  5596.5  233.39  5722.9  233.98  5780.5  235.19
#Mann= 9 ,-1 , 0
  4268.5     .07       0  4719.1     .12       0  4735.3     .07       0
  4984.1     .05       0  4988.1     .07       0  5073.4     .12       0
  5255.8     .07       0  5281.6     .12       0  5440.6     .07       0
Bank Sta=4984.1,4988.1
XS Rating Curve= 0 ,0
Exp/Cntr=0.3,0.1

Type RM Length L Ch R = 1 ,2966    ,99,99,99
BEGIN DESCRIPTION:
Mapping XS e3319b17
END DESCRIPTION:
XS GIS Cut Line= 6
      2490340.11     13480956.15      2490057.87     13480227.96
      2490091.74     13480109.42      2490083.28     13480064.26
      2490046.58     13480010.63      2489739.45     13479742.94
#Sta/Elev= 30
  4163.3  236.45  4230.7  235.18  4247.9   234.9  4401.2  231.91  4473.8  230.38
    4615  228.08  4703.2  226.57  4825.9  225.56  4855.8  228.44  4861.6  226.62
  4891.8   224.6  4892.1   224.1  4895.8   224.6  4934.9   227.3  4943.2  230.49
  4951.7  228.32  4977.4  231.05  4982.7  229.32    5021  230.87  5058.4  228.66
  5063.5  230.52  5082.4  227.75  5119.2  229.01  5125.2  227.44  5183.5  230.71
  5205.4  230.38  5226.3  227.71  5388.3  230.19  5556.2  232.77  5586.1  233.06
#Mann= 11 ,-1 , 0
  4163.3     .07       0  4230.7     .12       0  4247.9     .07       0
  4401.2     .12       0  4473.8     .07       0    4615     .12       0
  4703.2     .07       0  4891.8     .05       0  4895.8     .07       0
  5388.3     .12       0  5556.2     .07       0
Bank Sta=4891.8,4895.8
XS Rating Curve= 0 ,0
Exp/Cntr=0.3,0.1

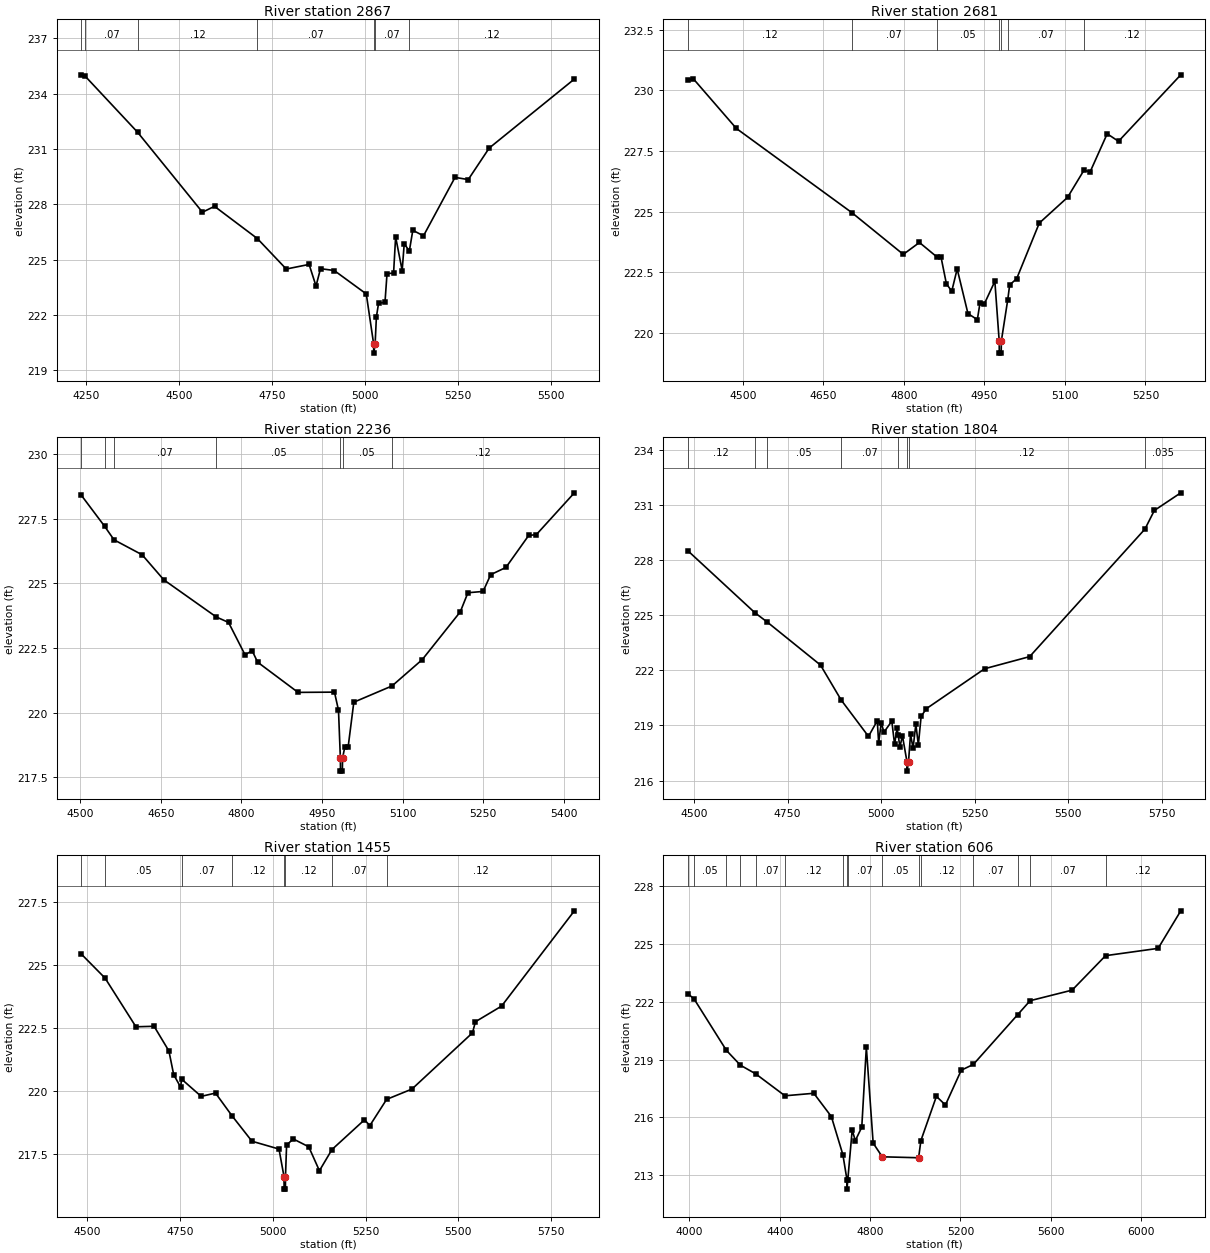
Type RM Length L Ch R = 1 ,2867    ,186,186,186
BEGIN DESCRIPTION:
Mapping XS 1b9f4462
END DESCRIPTION:
XS GIS Cut Line= 4
        2490326.     13480882.74      2490162.31     13480137.64
      2490066.34     13479925.95      2489869.36     13479661.44
#Sta/Elev= 30
  4237.5  235.03  4248.3  234.94  4388.3  231.92  4562.8  227.58  4595.2   227.9
  4710.5  226.15  4788.1   224.5  4849.5  224.75  4868.1  223.58  4880.2  224.52
    4917  224.42  5003.2  223.15    5023  220.44  5023.2  219.94    5027  220.44
  5030.4   221.9  5036.2  222.64  5053.5   222.7    5059  224.25  5076.6  224.28
  5082.1  226.24  5099.7  224.42  5105.2  225.87    5119  225.48  5128.3   226.6
    5157   226.3  5241.8  229.47  5277.3  229.35  5333.7  231.06  5562.6   234.8
#Mann= 7 ,-1 , 0
  4237.5     .12       0  4248.3     .07       0  4388.3     .12       0
  4710.5     .07       0    5023     .05       0    5027     .07       0
    5119     .12       0
Bank Sta=5023,5027
XS Rating Curve= 0 ,0
Exp/Cntr=0.3,0.1

Type RM Length L Ch R = 1 ,2681    ,445,445,445
BEGIN DESCRIPTION:
TRIB TO TRIB 5 TO PERDIDO CREEK 4.0
END DESCRIPTION:
XS GIS Cut Line= 3
        2490375.     13480675.05        2490325.       13480075.
      2490224.99     13479774.96
#Sta/Elev= 30
  4397.4  230.42  4407.5  230.48  4487.8  228.43    4703  224.96  4798.8  223.24
  4828.9  223.73  4861.1  223.14  4869.1  223.13  4879.1  222.03  4889.1  221.72
  4899.2  222.64  4919.3   220.8  4936.8  220.55  4941.8  221.25  4949.4  221.18
  4969.4  222.13  4977.5  219.67  4977.7  219.17  4981.2  219.17  4981.5  219.67
  4993.5  221.38    4997  221.98  5010.1  222.24  5052.2  224.53  5104.9  225.59
  5135.2   226.7  5147.1  226.65  5178.7  228.21  5199.8   227.9  5315.8  230.64
#Mann= 7 ,-1 , 0
  4397.4     .12       0    4703     .07       0  4861.1     .05       0
  4977.5     .05       0  4981.5     .05       0  4993.5     .07       0
  5135.2     .12       0
Bank Sta=4977.5,4981.5
XS Rating Curve= 0 ,0
Exp/Cntr=0.3,0.1

Type RM Length L Ch R = 1 ,2236    ,432,432,432
BEGIN DESCRIPTION:
TRIB TO TRIB 5 TO PERDIDO CREEK 3.0
END DESCRIPTION:
XS GIS Cut Line= 3
      2490925.02     13480475.04        2490725.       13480025.
      2490424.97     13479724.97
#Sta/Elev= 30
  4502.5  228.41  4545.4  227.22  4563.1  226.69  4615.4  226.11  4655.7  225.14
  4753.4   223.7  4776.1  223.49  4806.9  222.23  4819.9   222.4  4830.2  221.95
  4905.4  220.78  4973.1  220.79  4980.6  220.09  4984.1  218.23  4984.3  217.73
  4987.8  217.73  4988.1  218.23  4992.3  218.66  4998.5  218.66  5009.1   220.4
  5080.2  221.03  5136.4  222.05  5207.1   223.9  5221.3  224.64  5249.5  224.69
  5263.7  225.34    5292  225.62  5334.4  226.86  5348.5  226.89  5419.3  228.51
#Mann= 7 ,-1 , 0
  4502.5     .07       0  4545.4     .12       0  4563.1     .07       0
  4753.4     .05       0  4984.1     .05       0  4988.1     .05       0
  5080.2     .12       0
Bank Sta=4984.1,4988.1
XS Rating Curve= 0 ,0
Exp/Cntr=0.3,0.1

Type RM Length L Ch R = 1 ,1804    ,349,349,349
BEGIN DESCRIPTION:
TRIB TO TRIB 5 TO PERDIDO CREEK 2.0
END DESCRIPTION:
XS GIS Cut Line= 3
        2491125.       13480475.        2491075.       13479975.
      2490525.02     13479375.02
#Sta/Elev= 30
  4483.8   228.5  4662.7  225.13  4695.2  224.63  4838.1  222.28  4893.2  220.38
  4966.2   218.4  4989.7  219.25  4993.4  218.04  5000.2  219.14  5007.6  218.63
  5028.5  219.23  5035.9  217.97  5042.7  218.85  5045.3  218.49  5050.1  217.83
  5056.9  218.43  5069.1  217.01  5069.3  216.51  5073.1  217.01  5078.5  218.51
  5085.3  217.76  5092.7  219.06  5099.4  217.94  5106.8  219.49    5121  219.91
  5276.4  222.08  5396.7  222.74  5704.6  229.68  5729.6  230.69  5800.2  231.65
#Mann= 8 ,-1 , 0
  4483.8     .12       0  4662.7     .07       0  4695.2     .05       0
  4893.2     .07       0  5045.3     .12       0  5069.1     .05       0
  5073.1     .12       0  5704.6    .035       0
Bank Sta=5069.1,5073.1
XS Rating Curve= 0 ,0
Exp/Cntr=0.3,0.1

Type RM Length L Ch R = 1 ,1455    ,849,849,849
BEGIN DESCRIPTION:
Mapping XS a92374c4
END DESCRIPTION:
XS GIS Cut Line= 4
       2491243.1     13480330.25        2491382.     13479922.23
      2491347.28      13479800.7      2490749.18     13479315.28
#Sta/Elev= 30
  4484.7  225.44  4548.4  224.49  4631.5  222.56  4680.4  222.58  4720.3   221.6
  4733.2  220.66  4751.7  220.17  4754.7  220.48  4807.2   219.8  4845.8  219.93
  4890.2  219.03    4944  218.02  5016.8  217.71  5030.3  216.62  5030.6  216.12
  5034.1  216.12  5034.3  216.62  5037.3  217.87  5055.3  218.11  5096.9   217.8
  5125.7  216.85  5159.5  217.69  5247.1  218.87  5261.5  218.64  5306.7  219.68
    5375  220.09    5538  222.32  5545.9  222.76  5616.3  223.38  5812.4  227.16
#Mann= 8 ,-1 , 0
  4484.7     .12       0  4548.4     .05       0  4754.7     .07       0
  4890.2     .12       0  5030.3     .05       0  5034.3     .12       0
  5159.5     .07       0  5306.7     .12       0
Bank Sta=5030.3,5034.3
XS Rating Curve= 0 ,0
Exp/Cntr=0.3,0.1

Type RM Length L Ch R = 1 ,606     ,0,0,0
BEGIN DESCRIPTION:
TRIB TO TRIB 5 TO PERDIDO CREEK 1.0
END DESCRIPTION:
XS GIS Cut Line= 4
      2491367.61     13480205.58      2491859.43     13479661.81
       2491901.5     13479293.42      2490824.96       13479225.
#Sta/Elev= 30
    3993  222.43  4021.2  222.14  4163.7  219.48  4225.7  218.71  4293.4  218.26
    4423  217.12  4550.8  217.25  4628.5  216.04  4679.5  214.06  4697.4  212.77
  4697.7  212.27  4701.4  212.77  4720.7  215.34  4734.6  214.79  4763.2  215.49
  4783.4  219.64  4813.6  214.66  4853.8  213.95  5014.9   213.9  5024.9  214.79
  5093.7  217.09  5133.6  216.64  5203.7  218.45  5257.3  218.75  5453.9  221.34
  5508.5  222.06  5694.7  222.61  5842.7   224.4  6075.5  224.78  6175.7  226.73
#Mann= 16 ,-1 , 0
    3993     .07       0  4021.2     .05       0  4163.7     .07       0
  4225.7     .12       0  4293.4     .07       0    4423     .12       0
  4679.5     .07       0  4697.4     .07       0  4701.4     .07       0
  4853.8     .05       0  5014.9     .07       0  5024.9     .12       0
  5257.3     .07       0  5453.9     .12       0  5508.5     .07       0
  5842.7     .12       0
Bank Sta=4853.8,5014.9
XS Rating Curve= 0 ,0
Exp/Cntr=0.3,0.1

Chan Stop Cuts=-1
Use User Specified Reach Order=0
Composite Channel Slope=5