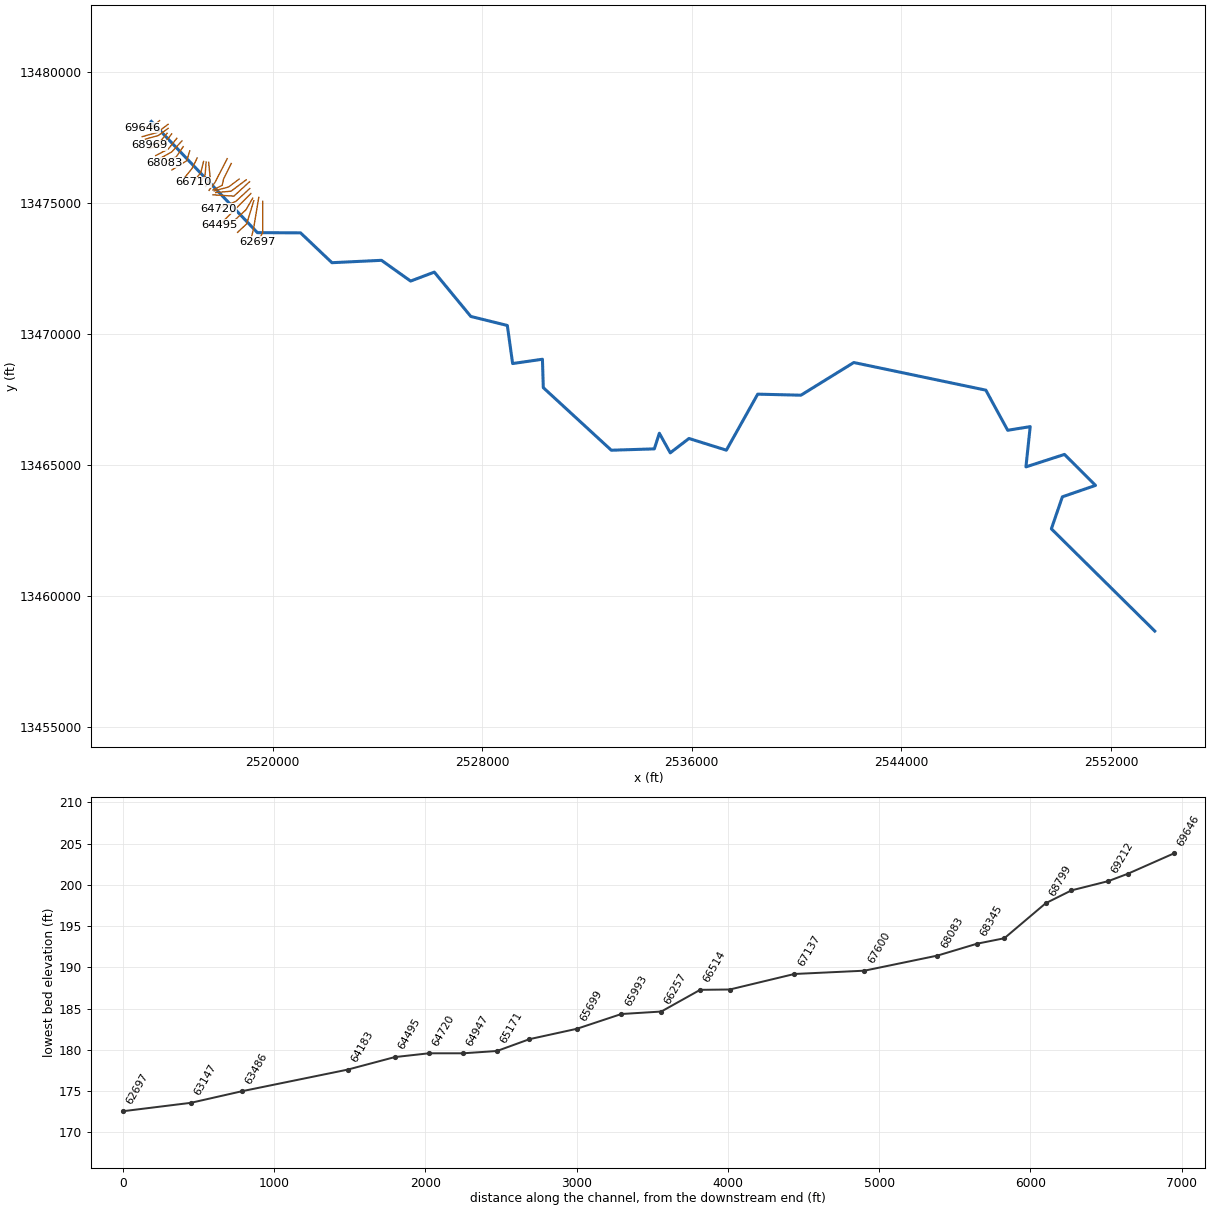
--- TURKEY CREEK.prj (project) ---

Proj Title=TURKEY CREEK Base Level Engineering
Current Plan=p01
Default Exp/Contr=0.3,0.1
English Units
Geom File=g01
Flow File=f01
Plan File=p01
Y Axis Title=Elevation
X Axis Title(PF)=Main Channel Distance
X Axis Title(XS)=Station
BEGIN DESCRIPTION:
TURKEY CREEK
END DESCRIPTION:
DSS Export Rating Curves= 0
DSS Export Rating Curve Sorted= 0
DSS Export Volume Flow Curves= 0
DXF OffsetX= 0
DXF OffsetY= 0
DXF ScaleX= 1
DXF ScaleY= 10

--- TURKEY CREEK.p01 (plan) ---

Plan Title=Multiple Run
Program Version=4.10
Short Identifier=Multiple
Geom File=g01
Flow File=f01
Subcritical Flow
K Sum by GR= 0
Std Step Tol= 0.01
Critical Tol= 0.01
Num of Std Step Trials= 20
Max Error Tol= 0.3
Flow Tol Ratio= 0.001
Split Flow NTrial= 30
Split Flow Tol= 0.02
Split Flow Ratio= 0.02
Log Output Level= 0
Friction Slope Method= 1
Unsteady Friction Slope Method= 2
Unsteady Bridges Friction Slope Method= 1
Parabolic Critical Depth
Global Vel Dist= 1 , 1 , 1
Global Log Level= 0
CheckData=True
Encroach Param=-1 ,0,0, 0
BEGIN DESCRIPTION:
Multiple Run
END DESCRIPTION:
Computation Interval=1HOUR
Output Interval=1HOUR
Run HTab= 0
Run UNet= 0
Run PostProcess= 0
Run WQNet= 0
UNET Theta= 1
UNET Theta Warmup= 1
UNET ZTol= 0.02
UNET ZSATol= 0.05
UNET MxIter= 20
UNET MaxInSteps= 0
UNET DtIC= 0
UNET DtMin= 0
UNET MaxCRTS= 20
UNET WFStab= 2
UNET SFStab= 1
UNET WFX= 1
UNET SFX= 1
UNET DSS MLevel= 4
UNET DZMax Abort= 100
UNET Convert EG Bridges= 0
UNET Use Existing IB Tables=-1
UNET Froude Reduction=False
UNET Froude Limit= 1
UNET Froude Power= 10
UNET Time Slicing=0,0, 5
UNET Junction Losses=0
Instantaneous Interval=1HOUR
Write IC File= 0
Write IC File at Sim End=0
Echo Input=False
Echo Parameters=False
Echo Output=False
Write Detailed= 0
WQ AD Non Conservative
WQ ULTIMATE=-1
WQ Max Comp Step=1HOUR
WQ Output Interval=15MIN
WQ Output Selected Increments= 0
WQ Output face flow=0
WQ Output face velocity=0
WQ Output face area=0
WQ Output face dispersion=0
WQ Output cell volume=0
WQ Output cell surface area=0
WQ Output cell continuity=0
WQ Output cumulative cell continuity=0
WQ Output face conc=0
WQ Output face dconc_dx=0
WQ Output face courant=0
WQ Output face peclet=0
WQ Output face adv mass=0
WQ Output face disp mass=0
WQ Output cell mass=0
WQ Output cell source sink temp=0
WQ Output cell source sink nsm=0
WQ Output MaxMinRange=-1
WQ Daily Max Min Mean=-1
WQ Daily Range=0
WQ Daily Time=0
WQ Create Restart=0
WQ Fixed Restart=0
WQ System Summary=0
WQ Use Fixed Temperature=0
Sorting and Armoring Iterations= 10
XS Update Threshold= 0.02
Hydraulics Update Threshold= 0.02
Energy Slope Method= 1
Volume Change Method= 0
XS Weighting Method= 0
Number of US Weighted Cross Sections= 1
Number of DS Weighted Cross Sections= 1
Upstream XS Weight=0.25
Main XS Weight=0.5
Downstream XS Weight=0.25
Number of DS XS's Weighted with US Boundary= 1
Upstream Boundary Weight= 1
Weight of XSs Associated with US Boundary= 0
Number of US XS's Weighted with DS Boundary= 1
Downstream Boundary Weight= 0.5
Weight of XSs Associated with DS Boundary= 0.5
Sediment Output Level= 4
Mass or Volume Output= 0
Output Increment Type= 1
Profile and TS Output Increment= 10
XS Output Flag= 0
XS Output Increment= 10
Disregard all LS=0
Disregard all Conn=0
Disregard all Breaches=0
Disregard all Pumps=0

--- TURKEY CREEK.f01 (steady flow) ---

Flow Title=Multiple
Program Version=4.10
Number of Profiles= 7
Profile Names=10-year,25-year,50-year,1pct_min,100-year,1pct_plu,500-year
River Rch & RM=TURKEY CREEK,Reach-1         ,69646
     472     738     970     619    1235    2463    1974
River Rch & RM=TURKEY CREEK,Reach-1         ,65993
     761    1225    1643    1065    2126    4242    3522
River Rch & RM=TURKEY CREEK,Reach-1         ,64183
     990    1615    2186    1430    2852    5691    4805
River Rch & RM=TURKEY CREEK,Reach-1         ,61747
    1177    1934    2629    1726    3443    6870    5843
River Rch & RM=TURKEY CREEK,Reach-1         ,58161
    1321    2181    2974    1957    3904    7790    6661
River Rch & RM=TURKEY CREEK,Reach-1         ,53336
    2044    3444    4759    3169    6324   12618   11055
River Rch & RM=TURKEY CREEK,Reach-1         ,49068
    2677    4560    6349    4256    8492   16943   15043
River Rch & RM=TURKEY CREEK,Reach-1         ,45356
    2780    4728    6576    4402    8782   17523   15513
River Rch & RM=TURKEY CREEK,Reach-1         ,39417
    2979    5061    7033    4704    9386   18727   16545
River Rch & RM=TURKEY CREEK,Reach-1         ,35116
    3239    5511    7668    5132   10240   20432   18080
River Rch & RM=TURKEY CREEK,Reach-1         ,31283
    3360    5715    7949    5318   10612   21173   18718
River Rch & RM=TURKEY CREEK,Reach-1         ,26747
    4346    7454   10426    7010   13987   27907   24912
River Rch & RM=TURKEY CREEK,Reach-1         ,23360
    4437    7591   10599    7112   14190   28313   25172
River Rch & RM=TURKEY CREEK,Reach-1         ,16394
    4402    7495   10431    6974   13915   27764   24506
River Rch & RM=TURKEY CREEK,Reach-1         ,7531
    4631    7878   10956    7318   14601   29133   25664
Boundary for River Rch & Prof#=TURKEY CREEK,Reach-1         , 1
Up Type= 0
Dn Type= 3
Dn Slope=0.0002
Boundary for River Rch & Prof#=TURKEY CREEK,Reach-1         , 2
Up Type= 0
Dn Type= 3
Dn Slope=0.0002
Boundary for River Rch & Prof#=TURKEY CREEK,Reach-1         , 3
Up Type= 0
Dn Type= 3
Dn Slope=0.0002
Boundary for River Rch & Prof#=TURKEY CREEK,Reach-1         , 4
Up Type= 0
Dn Type= 3
Dn Slope=0.0002
Boundary for River Rch & Prof#=TURKEY CREEK,Reach-1         , 5
Up Type= 0
Dn Type= 3
Dn Slope=0.0002
Boundary for River Rch & Prof#=TURKEY CREEK,Reach-1         , 6
Up Type= 0
Dn Type= 3
Dn Slope=0.0002
Boundary for River Rch & Prof#=TURKEY CREEK,Reach-1         , 7
Up Type= 0
Dn Type= 3
Dn Slope=0.0002
DSS Import GetInterval= 0
DSS Import GetPeak= 0
DSS Import FillOption= 0

--- TURKEY CREEK.g01 (geometry) ---

Geom Title=Existing Conditions
Program Version=4.10

River Reach=TURKEY CREEK    ,Reach-1
Reach XY= 30
        2515375.       13478125.      2519422.56     13473880.52
      2521069.35     13473873.03      2522268.45     13472734.25
      2524158.92     13472824.86      2525271.38     13472032.48
        2526175.       13472375.      2527568.81     13470682.81
      2528962.46     13470338.35      2529164.82     13468885.32
       2530302.3     13469049.16      2530335.19     13467965.32
      2532930.85     13465577.06      2534573.53     13465628.53
      2534764.81     13466225.55      2535180.93     13465477.24
      2535895.18      13466025.3       2537323.5     13465578.62
      2538518.94     13467716.86      2540169.14     13467677.07
      2542186.85      13468924.4      2547227.43     13467869.48
        2548061.     13466338.11      2548920.05     13466477.69
      2548757.78     13464941.24      2550228.33     13465417.02
      2551414.05     13464235.05      2550148.31     13463799.28
      2549728.37     13462576.74        2553675.       13458675.

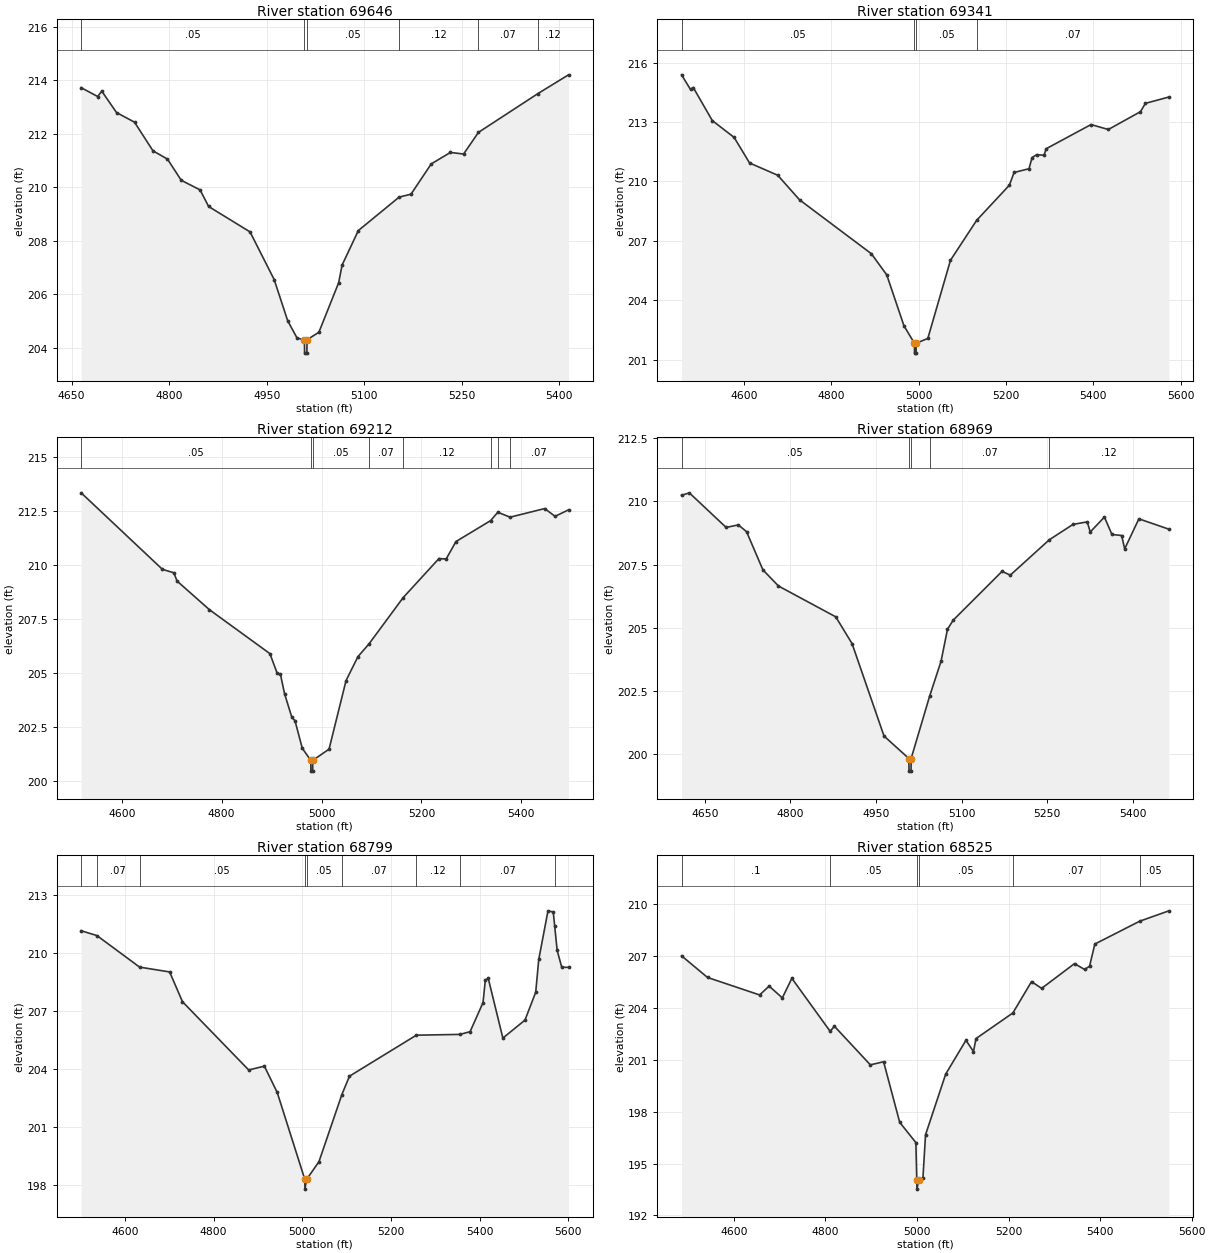
Type RM Length L Ch R = 1 ,69646   ,305,305,305
BEGIN DESCRIPTION:
TURKEY CREEK 107.0
END DESCRIPTION:
XS GIS Cut Line= 3
      2515689.88     13478155.72      2515424.98     13477949.99
      2515015.42     13477887.49
#Sta/Elev= 30
  4664.6  213.72    4690  213.39  4696.3  213.59    4719  212.79  4746.7  212.43
  4775.1  211.36  4797.4  211.05  4818.5  210.26  4847.5   209.9  4860.7  209.28
  4924.4  208.33  4961.5  206.55  4982.3  205.01  4996.8  204.36  5008.1   204.3
  5008.3   203.8  5011.8   203.8  5012.1   204.3  5030.3  204.58  5060.7  206.43
    5066  207.09    5091  208.38  5153.7  209.63    5172  209.74  5203.1  210.87
  5232.6   211.3  5252.9  211.24  5275.8  212.05  5367.3   213.5  5414.3   214.2
#Mann= 6 ,-1 , 0
  4664.6     .05       0  5008.1    .035       0  5012.1     .05       0
  5153.7     .12       0  5275.8     .07       0  5367.3     .12       0
Bank Sta=5008.1,5012.1
XS Rating Curve= 0 ,0
Exp/Cntr=0.3,0.1

Type RM Length L Ch R = 1 ,69341   ,129,129,129
BEGIN DESCRIPTION:
Mapping XS 20187086
END DESCRIPTION:
XS GIS Cut Line= 3
      2516012.77     13478015.08      2515603.93     13477705.19
      2515023.17     13477543.72
#Sta/Elev= 30
  4457.3  215.38  4477.8  214.64  4484.1  214.74  4527.7  213.07  4577.7  212.22
    4613  210.93  4677.5  210.31  4727.4  209.07  4891.8  206.35  4927.1  205.28
  4966.5  202.71  4990.4  201.83  4990.7  201.33  4994.2  201.33  4994.4  201.83
  5021.1  202.07    5073  206.02  5133.1  208.04  5207.9  209.81  5218.6  210.45
  5252.8  210.64  5259.8   211.2  5270.2  211.35  5287.1  211.32  5292.2  211.65
  5394.8  212.87  5434.4  212.62    5508  213.52  5519.3  213.94  5573.1  214.26
#Mann= 4 ,-1 , 0
  4457.3     .05       0  4990.4    .035       0  4994.4     .05       0
  5133.1     .07       0
Bank Sta=4990.4,4994.4
XS Rating Curve= 0 ,0
Exp/Cntr=0.3,0.1

Type RM Length L Ch R = 1 ,69212   ,243,243,243
BEGIN DESCRIPTION:
Mapping XS 2164f940
END DESCRIPTION:
XS GIS Cut Line= 3
      2516016.26     13477862.31        2515643.     13477588.87
      2515149.09     13477450.23
#Sta/Elev= 30
  4518.7  213.35  4681.4   209.8  4704.4  209.64  4710.6  209.26  4775.4  207.93
  4896.6  205.89  4911.3  204.97  4917.5  204.95  4925.9  204.03  4940.6  202.93
  4946.8  202.78  4961.4   201.5  4978.4  200.94  4978.7  200.44  4982.2  200.44
  4982.4  200.94    5015  201.46    5049  204.64  5072.8  205.75  5094.9  206.34
  5163.4  208.49    5235   210.3  5249.4  210.28  5269.1  211.09  5338.4  212.06
  5352.9  212.45  5377.4  212.22  5446.7  212.62  5467.5  212.26  5494.4  212.56
#Mann= 8 ,-1 , 0
  4518.7     .05       0  4978.4    .035       0  4982.4     .05       0
  5094.9     .07       0  5163.4     .12       0  5338.4     .07       0
  5352.9     .12       0  5377.4     .07       0
Bank Sta=4978.4,4982.4
XS Rating Curve= 0 ,0
Exp/Cntr=0.3,0.1

Type RM Length L Ch R = 1 ,68969   ,170,170,170
BEGIN DESCRIPTION:
TURKEY CREEK 106.0
END DESCRIPTION:
XS GIS Cut Line= 3
      2515974.97     13477674.96        2515725.       13477375.
      2515291.65     13477211.04
#Sta/Elev= 30
  4609.3  210.24  4622.9  210.34  4687.4  208.97  4708.8  209.07  4723.2   208.8
  4751.8  207.29  4779.1  206.65  4879.4  205.43    4908  204.37    4964  200.71
  5007.5  199.82  5007.8  199.32  5011.3  199.32  5011.5  199.82  5043.8  202.28
  5063.9  203.67  5075.2  204.94  5085.3   205.3  5170.8  207.23  5185.2  207.08
  5253.5  208.48  5295.1  209.09    5320  209.19  5325.3  208.79  5350.1  209.38
  5363.3  208.69  5380.3  208.65  5385.6  208.12  5410.5  209.31  5463.1   208.9
#Mann= 5 ,-1 , 0
  4609.3     .05       0  5007.5    .035       0  5011.5     .05       0
  5043.8     .07       0  5253.5     .12       0
Bank Sta=5007.5,5011.5
XS Rating Curve= 0 ,0
Exp/Cntr=0.3,0.1

Type RM Length L Ch R = 1 ,68799   ,274,274,274
BEGIN DESCRIPTION:
Mapping XS 4829f655
END DESCRIPTION:
XS GIS Cut Line= 3
      2516150.81     13477649.64      2515838.31     13477245.99
      2515270.34     13477089.91
#Sta/Elev= 30
  4501.1  211.13  4536.7  210.88  4632.9  209.25  4700.7     209  4729.7  207.46
  4879.1  203.93  4914.4  204.13  4943.4  202.77  5005.7  198.27  5005.9  197.77
  5009.7  198.27  5037.6  199.19  5089.3  202.66  5106.4  203.61  5257.3  205.73
  5355.6  205.77  5378.5  205.91  5407.7  207.41  5412.9  208.57  5419.5  208.67
  5452.5  205.58  5502.4  206.51  5526.6  207.95  5533.5  209.65  5554.3  212.16
  5566.2   212.1  5569.5  211.35    5575  210.11  5585.4  209.24  5600.6  209.24
#Mann= 9 ,-1 , 0
  4501.1     .05       0  4536.7     .07       0  4632.9     .05       0
  5005.7    .035       0  5009.7     .05       0  5089.3     .07       0
  5257.3     .12       0  5355.6     .07       0  5569.5     .12       0
Bank Sta=5005.7,5009.7
XS Rating Curve= 0 ,0
Exp/Cntr=0.3,0.1

Type RM Length L Ch R = 1 ,68525   ,180,180,180
BEGIN DESCRIPTION:
TURKEY CREEK 105.0
END DESCRIPTION:
XS GIS Cut Line= 3
      2516347.18      13477481.9        2516025.       13477075.
      2515541.64     13476822.16
#Sta/Elev= 30
  4485.8     207  4542.5  205.75  4656.3  204.74  4677.1  205.25  4705.9  204.57
  4726.7   205.7  4810.3  202.64  4819.7  202.93  4898.2   200.7  4927.1  200.88
  4962.3  197.38  4997.6  196.21  4999.6  194.02  4999.9  193.52  5003.6  194.02
    5013  194.15  5018.7  196.66  5062.8  200.17    5107  202.12  5123.4  201.47
    5129  202.22  5209.5   203.7  5250.2  205.51  5272.3  205.12  5344.1  206.55
  5366.2  206.21    5377   206.4  5388.5  207.68  5486.5     209  5550.3   209.6
#Mann= 6 ,-1 , 0
  4485.8      .1       0  4810.3     .05       0  4999.6    .035       0
  5003.6     .05       0  5209.5     .07       0  5486.5     .05       0
Bank Sta=4999.6,5003.6
XS Rating Curve= 0 ,0
Exp/Cntr=0.3,0.1

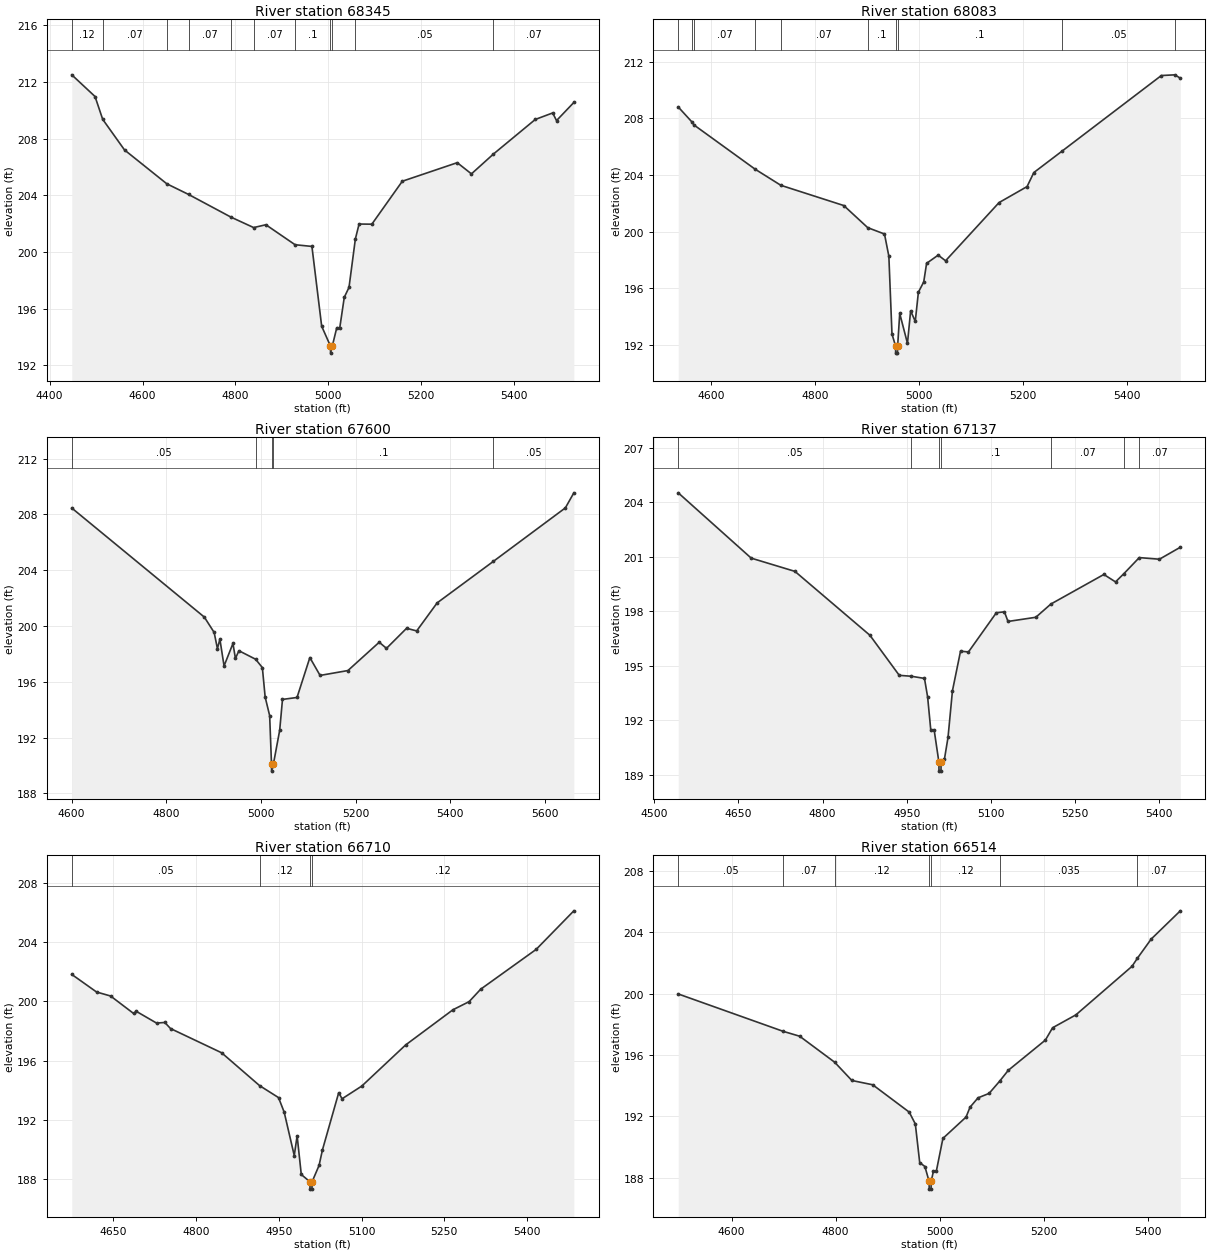
Type RM Length L Ch R = 1 ,68345   ,262,262,262
BEGIN DESCRIPTION:
Mapping XS e850c5b7
END DESCRIPTION:
XS GIS Cut Line= 3
       2516545.8      13477384.9      2516155.15     13476963.87
      2515712.43     13476716.47
#Sta/Elev= 30
  4447.6   212.5  4497.7  210.97  4514.2  209.36  4561.2   207.2  4652.3  204.81
  4699.1  204.06  4790.4  202.46  4839.4  201.72  4865.7  201.92  4928.6  200.51
  4964.9  200.39  4985.9  194.76  5004.8  193.36  5005.1  192.86  5008.8  193.36
  5018.4  194.65  5024.9  194.65  5034.6   196.8  5044.8   197.5  5058.5  200.92
  5066.5  201.97    5094  201.96  5159.6  204.99  5277.9   206.3  5308.5  205.51
  5355.9  206.91    5446  209.35  5483.5  209.81  5491.8  209.27  5529.1  210.55
#Mann= 11 ,-1 , 0
  4447.6     .12       0  4514.2     .07       0  4652.3     .05       0
  4699.1     .07       0  4790.4      .1       0  4839.4     .07       0
  4928.6      .1       0  5004.8     .05       0  5008.8      .1       0
  5058.5     .05       0  5355.9     .07       0
Bank Sta=5004.8,5008.8
XS Rating Curve= 0 ,0
Exp/Cntr=0.3,0.1

Type RM Length L Ch R = 1 ,68083   ,483,483,483
BEGIN DESCRIPTION:
TURKEY CREEK 104.0
END DESCRIPTION:
XS GIS Cut Line= 3
      2516590.19     13477162.39        2516325.       13476775.
      2515881.83     13476551.28
#Sta/Elev= 30
  4536.2   208.8  4562.1  207.76  4566.5  207.53    4684  204.41  4733.6  203.27
  4854.7  201.84  4900.7  200.28    4933  199.83  4941.4  198.26  4947.4  192.77
  4954.3  191.92  4954.5  191.42    4958  191.42  4958.3  191.92  4962.3  194.22
  4977.2  192.11  4983.3  194.41  4992.2  193.66  4998.2  195.72  5008.5  196.45
    5014  197.76  5036.3  198.34  5050.5  197.94  5153.4  202.05  5207.3  203.18
  5220.3  204.17  5275.2   205.7  5465.6  211.02  5491.8  211.07  5502.1  210.83
#Mann= 10 ,-1 , 0
  4536.2     .07       0  4562.1     .05       0  4566.5     .07       0
    4684     .05       0  4733.6     .07       0  4900.7      .1       0
  4954.3     .05       0  4958.3      .1       0  5275.2     .05       0
  5491.8     .07       0
Bank Sta=4954.3,4958.3
XS Rating Curve= 0 ,0
Exp/Cntr=0.3,0.1

Type RM Length L Ch R = 1 ,67600   ,463,463,463
BEGIN DESCRIPTION:
TURKEY CREEK 103.0
END DESCRIPTION:
XS GIS Cut Line= 3
       2516840.2     13477002.65        2516725.       13476625.
      2516159.85     13476273.65
#Sta/Elev= 30
  4600.4  208.45  4880.4  200.63  4901.1  199.53    4908  198.37  4913.2  199.05
    4922  197.13  4940.8  198.74    4946  197.67  4953.4  198.22  4988.7  197.61
  5002.9  197.01  5008.8   194.9  5018.3  193.57  5022.2  190.09  5022.4  189.59
  5026.2  190.09  5039.5  192.52  5045.4  194.73  5076.1  194.87  5103.2  197.73
  5124.8  196.45  5183.6   196.8  5249.7  198.83    5265  198.39  5307.5  199.83
  5328.8  199.64    5372  201.65  5490.9  204.63  5642.8  208.46  5660.7  209.54
#Mann= 5 ,-1 , 0
  4600.4     .05       0  4988.7      .1       0  5022.2     .05       0
  5026.2      .1       0  5490.9     .05       0
Bank Sta=5022.2,5026.2
XS Rating Curve= 0 ,0
Exp/Cntr=0.3,0.1

Type RM Length L Ch R = 1 ,67137   ,427,427,427
BEGIN DESCRIPTION:
TURKEY CREEK 102.0
END DESCRIPTION:
XS GIS Cut Line= 3
      2517124.93     13476731.85        2516925.       13476325.
      2516645.78     13475981.88
#Sta/Elev= 30
  4542.5  204.53  4672.7  200.93  4750.7   200.2  4884.4  196.68  4936.8  194.47
  4958.3  194.42  4981.8   194.3  4987.4  193.28    4993  191.47    4999  191.47
  5007.5  189.69  5007.7  189.19  5011.2  189.19  5011.5  189.69  5017.4  189.85
  5023.8  191.05  5031.7  193.62  5046.1   195.8  5060.3  195.76    5110  197.92
  5124.4  197.97  5130.8  197.44  5180.4  197.67  5207.3   198.4  5301.8  200.03
  5322.6  199.62  5337.4  200.07    5365  200.96  5400.9  200.87  5438.2  201.53
#Mann= 7 ,-1 , 0
  4542.5     .05       0  4958.3      .1       0  5007.5     .05       0
  5011.5      .1       0  5207.3     .07       0  5337.4     .12       0
    5365     .07       0
Bank Sta=5007.5,5011.5
XS Rating Curve= 0 ,0
Exp/Cntr=0.3,0.1

Type RM Length L Ch R = 1 ,66710   ,196,196,196
BEGIN DESCRIPTION:
TURKEY CREEK 101.0
END DESCRIPTION:
XS GIS Cut Line= 3
      2517366.67     13476598.63      2517265.48     13476186.16
      2516979.57     13475795.01
#Sta/Elev= 30
  4575.3  201.83  4620.2  200.64  4645.6  200.37  4687.2  199.19  4692.3  199.33
  4728.8  198.54  4743.8  198.58  4754.1  198.17  4846.7  196.53  4915.4  194.31
  4949.7   193.5    4960  192.51  4978.2  189.58  4983.4  190.92  4990.9   188.3
  5006.5  187.81  5006.7  187.31  5010.2  187.31  5010.5  187.81  5023.1  188.91
  5029.3  189.97  5058.7  193.83  5064.8  193.42  5100.5  194.28  5179.9  197.06
  5265.6  199.44  5294.9  199.99  5315.8  200.83  5416.2  203.52  5484.5  206.13
#Mann= 4 ,-1 , 0
  4575.3     .05       0  4915.4     .12       0  5006.5     .05       0
  5010.5     .12       0
Bank Sta=5006.5,5010.5
XS Rating Curve= 0 ,0
Exp/Cntr=0.3,0.1

Type RM Length L Ch R = 1 ,66514   ,257,257,257
BEGIN DESCRIPTION:
Mapping XS a6fbe1e8
END DESCRIPTION:
XS GIS Cut Line= 3
      2517465.92     13476577.63      2517426.85     13476087.14
       2517179.7      13475683.9
#Sta/Elev= 30
  4497.6  199.97  4699.1  197.54    4731  197.22  4798.2  195.53  4831.3  194.34
  4871.4  194.06  4941.6  192.28  4953.3  191.51  4961.7     189  4971.7  188.74
  4979.8  187.77    4980  187.27  4983.5  187.27  4983.8  187.77  4988.2  188.46
  4993.8  188.46  5006.3  190.57  5050.8  191.96  5058.4   192.6  5073.8  193.21
  5095.1   193.5  5115.5   194.3  5131.9     195  5203.3  196.97  5217.1  197.77
  5261.9  198.61  5369.8  201.77  5379.8  202.28  5406.6  203.54  5462.6  205.38
#Mann= 7 ,-1 , 0
  4497.6     .05       0  4699.1     .07       0  4798.2     .12       0
  4979.8     .05       0  4983.8     .12       0  5115.5    .035       0
  5379.8     .07       0
Bank Sta=4979.8,4983.8
XS Rating Curve= 0 ,0
Exp/Cntr=0.3,0.1

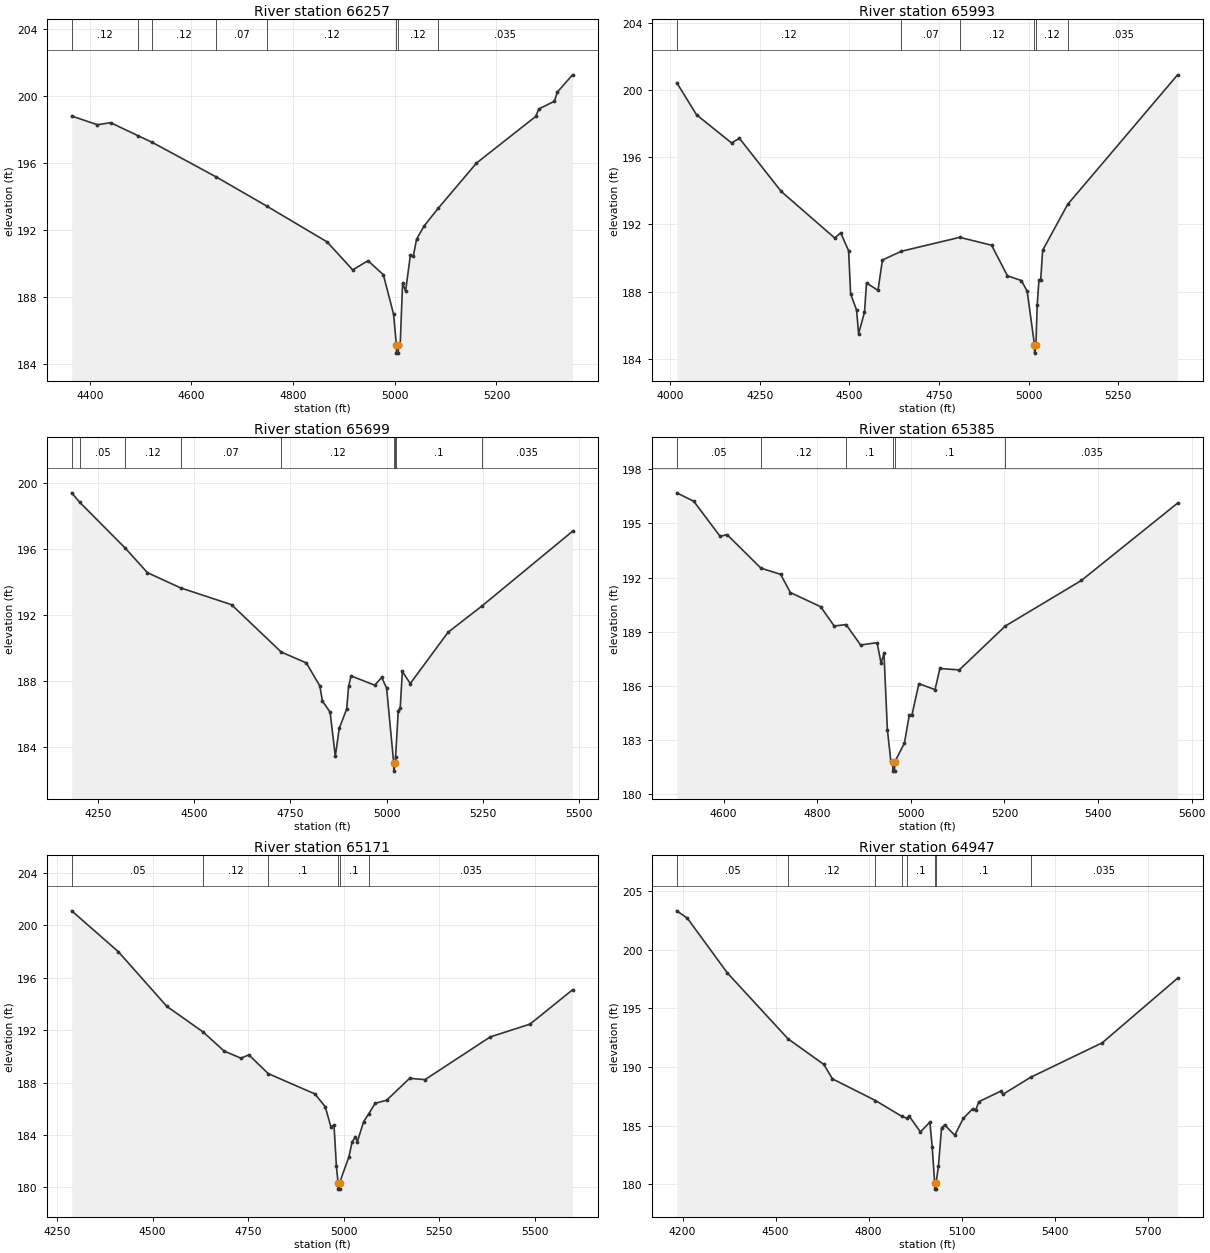
Type RM Length L Ch R = 1 ,66257   ,264,264,264
BEGIN DESCRIPTION:
TURKEY CREEK 100.0
END DESCRIPTION:
XS GIS Cut Line= 3
      2517562.44     13476565.16        2517625.       13475925.
      2517444.36     13475634.61
#Sta/Elev= 30
  4364.5   198.8  4414.9  198.28  4441.1   198.4  4495.3  197.62  4522.7  197.23
  4648.9  195.16  4747.7  193.43    4867  191.28  4917.3  189.61  4947.4  190.16
  4977.6  189.32  4997.7  186.96  5003.2  185.14  5003.4  184.64  5006.9  184.64
  5007.2  185.14  5010.7  185.14  5015.4  188.83  5021.3  188.34  5030.7  190.48
  5036.6  190.45    5043  191.45  5057.9  192.24  5085.2  193.28  5160.8  195.99
  5277.5  198.78  5283.3  199.22  5313.9  199.68  5319.9  200.23  5349.7  201.26
#Mann= 8 ,-1 , 0
  4364.5     .12       0  4495.3     .07       0  4522.7     .12       0
  4648.9     .07       0  4747.7     .12       0  5003.2     .05       0
  5007.2     .12       0  5085.2    .035       0
Bank Sta=5003.2,5007.2
XS Rating Curve= 0 ,0
Exp/Cntr=0.3,0.1

Type RM Length L Ch R = 1 ,65993   ,294,294,294
BEGIN DESCRIPTION:
Mapping XS d18c90cf
END DESCRIPTION:
XS GIS Cut Line= 3
      2518270.78      13476704.1      2517805.49      13475801.3
      2517576.32     13475495.74
#Sta/Elev= 30
  4018.3  200.43  4073.5  198.52    4171  196.85  4193.1  197.12  4309.8  193.96
  4459.1  191.19  4475.7   191.5  4497.8  190.43  4503.4  187.87    4520   186.9
  4525.6  185.49  4542.1  186.77  4547.8  188.52  4579.8  188.07  4592.1  189.88
  4644.9   190.4  4807.9  191.23  4896.8  190.76  4941.1  188.94  4979.8  188.66
    4996  188.03  5016.5  184.84  5016.8  184.34  5020.5  184.84  5024.1   187.2
  5029.1  188.71  5033.9  188.71  5039.3  190.46  5109.1  193.19  5415.9   200.9
#Mann= 6 ,-1 , 0
  4018.3     .12       0  4644.9     .07       0  4807.9     .12       0
  5016.5     .05       0  5020.5     .12       0  5109.1    .035       0
Bank Sta=5016.5,5020.5
XS Rating Curve= 0 ,0
Exp/Cntr=0.3,0.1

Type RM Length L Ch R = 1 ,65699   ,314,314,314
BEGIN DESCRIPTION:
Mapping XS 95ca7677
END DESCRIPTION:
XS GIS Cut Line= 4
      2518425.12     13476521.19      2518134.31     13475935.23
      2518077.89     13475687.83      2517726.45     13475509.94
#Sta/Elev= 30
  4181.5  199.42  4202.2  198.85  4320.6  196.07  4378.4  194.58  4464.3  193.66
  4596.9  192.64  4726.1  189.77  4791.3  189.11  4826.6  187.71    4833  186.81
  4853.2  186.12  4866.7  183.45  4876.9  185.14  4896.2  186.31  4901.3   187.7
  4907.7  188.32  4969.2  187.76  4987.3  188.23    5000  187.59  5018.5  183.05
  5018.8  182.55  5022.5  183.05  5023.4  183.41  5030.3   186.2  5035.4  186.39
    5041  188.59  5061.5  187.86  5159.9  190.97  5248.4  192.57  5483.3  197.09
#Mann= 9 ,-1 , 0
  4181.5     .12       0  4202.2     .05       0  4320.6     .12       0
  4464.3     .07       0  4726.1     .12       0  5018.5     .05       0
  5022.5     .12       0  5023.4      .1       0  5248.4    .035       0
Bank Sta=5018.5,5022.5
XS Rating Curve= 0 ,0
Exp/Cntr=0.3,0.1

Type RM Length L Ch R = 1 ,65385   ,214,214,214
BEGIN DESCRIPTION:
TURKEY CREEK 98.0
END DESCRIPTION:
XS GIS Cut Line= 3
      2518724.98     13475924.99        2518325.       13475625.
      2517774.97     13475474.99
#Sta/Elev= 30
  4499.9  196.69  4536.3  196.22  4592.6  194.28  4607.2  194.38  4679.8  192.52
  4721.8  192.18  4742.6  191.17  4807.2  190.39  4836.3  189.32  4861.6   189.4
  4892.6  188.27    4928   188.4  4936.3  187.27  4942.6   187.8  4949.9  183.58
  4957.2  181.86  4961.3  181.79  4961.6  181.29  4965.2  181.29  4965.5  181.79
  4986.3  182.84  4996.8  184.41  5002.5  184.41  5017.2  186.13  5051.7   185.8
  5062.1  186.97  5103.5  186.89  5201.9  189.32  5364.4  191.84    5570  196.12
#Mann= 6 ,-1 , 0
  4499.9     .05       0  4679.8     .12       0  4861.6      .1       0
  4961.3     .05       0  4965.5      .1       0  5201.9    .035       0
Bank Sta=4961.3,4965.5
XS Rating Curve= 0 ,0
Exp/Cntr=0.3,0.1

Type RM Length L Ch R = 1 ,65171   ,224,224,224
BEGIN DESCRIPTION:
Mapping XS c6085364
END DESCRIPTION:
XS GIS Cut Line= 3
      2518993.71     13475896.18      2518416.43     13475462.14
      2517830.49     13475410.05
#Sta/Elev= 30
  4288.4  201.11  4410.4  197.99  4537.5  193.81  4632.2  191.86  4687.4   190.4
  4731.1  189.86    4752  190.11  4802.7  188.68  4924.8  187.13  4951.9  186.15
  4966.5  184.63  4974.8  184.74    4981  181.63  4985.3  180.36  4985.6  179.86
  4989.3  179.86  4989.5  180.36  5013.9  182.34  5022.1  183.46    5031  183.85
    5036  183.49  5052.2  185.01  5065.7  185.61  5082.4  186.41  5112.5  186.65
  5172.7  188.32  5212.9  188.22  5383.5  191.48  5487.7  192.46  5598.9  195.08
#Mann= 6 ,-1 , 0
  4288.4     .05       0  4632.2     .12       0  4802.7      .1       0
  4985.3     .05       0  4989.5      .1       0  5065.7    .035       0
Bank Sta=4985.3,4989.5
XS Rating Curve= 0 ,0
Exp/Cntr=0.3,0.1

Type RM Length L Ch R = 1 ,64947   ,227,227,227
BEGIN DESCRIPTION:
TURKEY CREEK 97.0
END DESCRIPTION:
XS GIS Cut Line= 3
      2519124.99     13475824.99        2518525.       13475275.
      2517724.99       13475325.
#Sta/Elev= 30
  4181.3  203.33  4215.2  202.71  4344.1  198.04  4540.4   192.4  4655.8  190.22
  4683.5  188.99  4822.2  187.14  4907.4  185.79  4922.9  185.64  4931.4  185.79
  4967.2  184.46  4997.7   185.3  5005.2  183.17  5013.2  180.08  5013.4  179.58
  5017.1  179.58  5017.4  180.08  5025.3  181.53  5035.3   184.8  5045.3  185.06
  5077.9  184.18  5105.4  185.61  5135.5  186.43  5145.5  186.32  5155.5  187.04
  5225.7  187.93  5233.2  187.67  5323.2  189.13  5553.8  192.07  5796.8  197.58
#Mann= 8 ,-1 , 0
  4181.3     .05       0  4540.4     .12       0  4822.2      .1       0
  4907.4     .12       0  4922.9      .1       0  5013.2     .05       0
  5017.4      .1       0  5323.2    .035       0
Bank Sta=5013.2,5017.4
XS Rating Curve= 0 ,0
Exp/Cntr=0.3,0.1

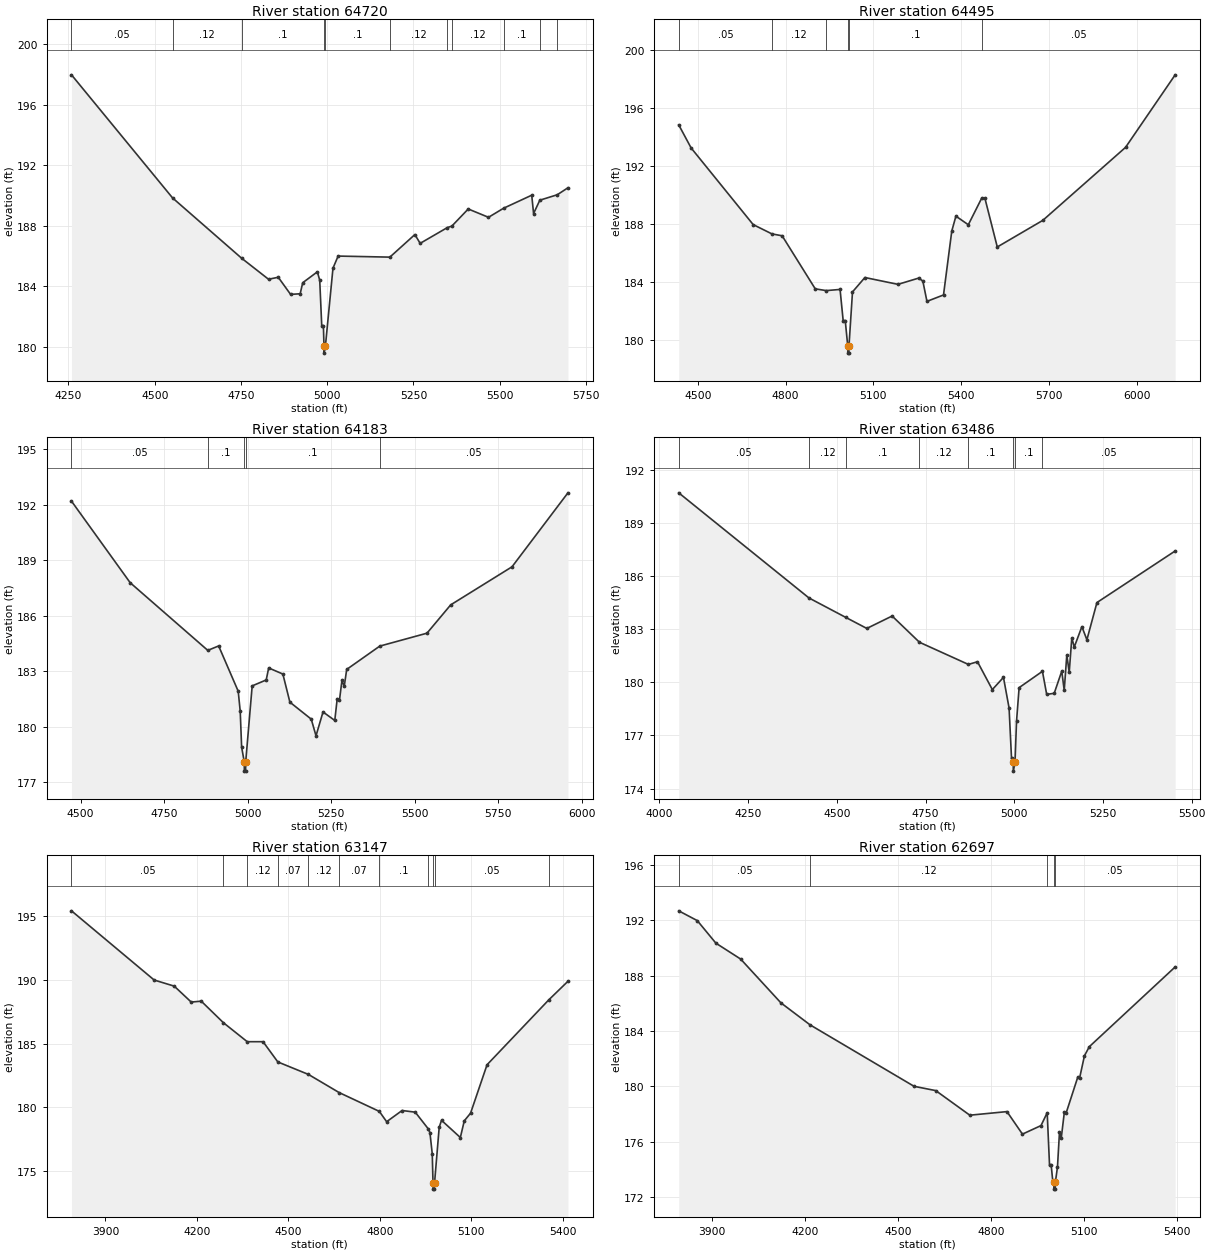
Type RM Length L Ch R = 1 ,64720   ,225,225,225
BEGIN DESCRIPTION:
Mapping XS 27b49937
END DESCRIPTION:
XS GIS Cut Line= 3
      2519131.89      13475565.2      2518597.15     13475072.14
      2517938.74     13474801.84
#Sta/Elev= 30
  4258.7  197.96  4551.7  189.83  4751.8  185.85  4829.8  184.46  4858.1  184.59
  4893.8  183.46  4921.6   183.5    4929  184.23  4971.5  184.95  4978.3  184.39
  4984.1  181.39  4988.9  181.39  4990.6  180.08  4990.9  179.58  4994.9  180.08
  5016.7  185.19  5031.6  185.99  5181.6  185.92  5254.1  187.41  5269.4  186.83
  5348.1  187.87  5361.3  187.97  5408.8   189.1  5467.5  188.55  5511.3  189.15
  5592.8  190.01  5598.2   188.8  5616.3  189.68  5666.9  190.04  5697.8   190.5
#Mann= 11 ,-1 , 0
  4258.7     .05       0  4551.7     .12       0  4751.8      .1       0
  4990.6     .05       0  4994.9      .1       0  5181.6     .12       0
  5348.1     .05       0  5361.3     .12       0  5511.3      .1       0
  5616.3     .12       0  5666.9      .1       0
Bank Sta=4990.6,4994.9
XS Rating Curve= 0 ,0
Exp/Cntr=0.3,0.1

Type RM Length L Ch R = 1 ,64495   ,312,312,312
BEGIN DESCRIPTION:
TURKEY CREEK 96.0
END DESCRIPTION:
XS GIS Cut Line= 3
      2519174.99     13475374.99        2518775.       13474975.
      2517975.03     13474175.03
#Sta/Elev= 30
  4434.6  194.82    4477  193.23  4689.1  187.96  4753.2  187.32  4788.1  187.19
  4901.3  183.54  4938.9  183.42  4986.1   183.5  4996.7  181.36  5003.8  181.36
  5012.3  179.62  5012.6  179.12  5016.3  179.12  5016.6  179.62  5028.6  183.33
    5071  184.32  5184.1  183.85  5254.8  184.28    5269  184.08  5283.1  182.68
  5339.7  183.12    5368  187.52  5382.1  188.54  5424.5  187.95  5470.3  189.78
  5481.1  189.78  5523.5  186.42  5679.1  188.25  5961.9  193.27  6131.6  198.26
#Mann= 6 ,-1 , 0
  4434.6     .05       0  4753.2     .12       0  4938.9      .1       0
  5012.3     .05       0  5016.6      .1       0  5470.3     .05       0
Bank Sta=5012.3,5016.6
XS Rating Curve= 0 ,0
Exp/Cntr=0.3,0.1

Type RM Length L Ch R = 1 ,64183   ,697,697,697
BEGIN DESCRIPTION:
Mapping XS a84b4ea0
END DESCRIPTION:
XS GIS Cut Line= 3
      2519242.99     13475197.14      2518986.04     13474752.69
      2518270.79       13474093.
#Sta/Elev= 30
  4472.6   192.2  4648.3  187.79  4880.7  184.13  4913.2  184.37  4971.8  181.92
  4977.8  180.83    4982   178.9  4989.9   178.1  4990.2   177.6  4993.9   177.6
  4994.2   178.1  5013.6  182.21  5055.6  182.53    5063  183.18  5105.5  182.85
  5126.5  181.33  5190.5  180.41  5204.7  179.51  5225.7   180.8  5260.9  180.34
  5268.2  181.52    5275  181.44  5282.4  182.51  5289.2  182.18  5296.6   183.1
  5395.5  184.36    5537  185.06  5607.9  186.59  5791.6  188.65    5959  192.65
#Mann= 5 ,-1 , 0
  4472.6     .05       0  4880.7      .1       0  4989.9     .05       0
  4994.2      .1       0  5395.5     .05       0
Bank Sta=4989.9,4994.2
XS Rating Curve= 0 ,0
Exp/Cntr=0.3,0.1

Type RM Length L Ch R = 1 ,63486   ,339,339,339
BEGIN DESCRIPTION:
Mapping XS 483c643b
END DESCRIPTION:
XS GIS Cut Line= 3
      2519284.65      13475099.9      2519013.82     13474217.97
      2518666.62      13473891.6
#Sta/Elev= 30
  4054.5  190.69  4421.5  184.76  4525.5  183.66  4584.6  183.04  4655.9  183.74
  4732.9  182.26  4870.8  181.01  4896.5  181.16  4938.3  179.59  4969.7  180.28
  4985.5  178.55  4992.4  175.71  4997.1  175.49  4997.5  174.99  5002.2  175.49
  5006.5   177.8  5013.8   179.7  5079.5  180.62  5091.5  179.32  5112.7  179.38
    5134  180.63  5140.9  179.55  5148.2  181.54    5155  180.57  5162.3  182.51
  5169.2  181.99  5190.7  183.14  5204.8   182.4  5233.1   184.5  5453.6  187.41
#Mann= 8 ,-1 , 0
  4054.5     .05       0  4421.5     .12       0  4525.5      .1       0
  4732.9     .12       0  4870.8      .1       0  4997.1     .05       0
  5002.2      .1       0  5079.5     .05       0
Bank Sta=4997.1,5002.2
XS Rating Curve= 0 ,0
Exp/Cntr=0.3,0.1

Type RM Length L Ch R = 1 ,63147   ,450,450,450
BEGIN DESCRIPTION:
TURKEY CREEK 94.0
END DESCRIPTION:
XS GIS Cut Line= 3
      2519474.99     13475224.97        2519275.       13474025.
      2519175.01     13473625.03
#Sta/Elev= 30
  3788.5  195.42  4059.7  189.99  4125.6  189.51  4181.3  188.26  4214.3  188.33
  4286.9  186.64  4365.1  185.15    4417  185.15  4465.5  183.56    4566  182.58
  4666.4  181.16  4798.5  179.68  4822.5  178.87  4873.2  179.75  4916.3  179.62
  4959.7  178.29  4964.5  178.01  4972.1  176.36  4974.6  174.08    4975  173.58
  4979.3  173.58  4979.7  174.08  4994.9  178.43  5002.5  178.98  5064.3  177.63
  5077.2  178.94  5097.8  179.54  5151.9  183.34  5354.3  188.43  5417.3  189.89
#Mann= 11 ,-1 , 0
  3788.5     .05       0  4286.9     .07       0  4365.1     .12       0
  4465.5     .07       0    4566     .12       0  4666.4     .07       0
  4798.5      .1       0  4959.7     .05       0  4974.6     .05       0
  4979.7     .05       0  5354.3    .035       0
Bank Sta=4974.6,4979.7
XS Rating Curve= 0 ,0
Exp/Cntr=0.3,0.1

Type RM Length L Ch R = 1 ,62697   ,477,477,477
BEGIN DESCRIPTION:
TURKEY CREEK 93.0
END DESCRIPTION:
XS GIS Cut Line= 3
        2519625.     13475075.04        2519625.       13473875.
      2519424.98     13473524.96
#Sta/Elev= 30
  3791.7   192.7  3851.7  191.99  3911.7  190.36  3991.7  189.21  4121.7  186.04
  4215.7  184.45  4551.7     180  4621.7  179.69  4731.7  177.91  4851.7  178.17
  4901.7  176.54  4961.7  177.16  4981.6  178.09  4989.2  174.27  4994.6  174.27
  4999.7  173.12  5002.9  173.06  5003.3  172.56  5007.6  172.56    5008  173.06
  5014.8  174.16  5021.3  176.69    5027  176.25  5037.1  178.15  5042.8  178.07
  5080.3  180.66    5086  180.57  5101.9  182.21  5117.7  182.87  5394.9  188.64
#Mann= 5 ,-1 , 0
  3791.7     .05       0  4215.7     .12       0  4981.6     .05       0
  5002.9     .05       0    5008     .05       0
Bank Sta=5002.9,5008
XS Rating Curve= 0 ,0
Exp/Cntr=0.3,0.1