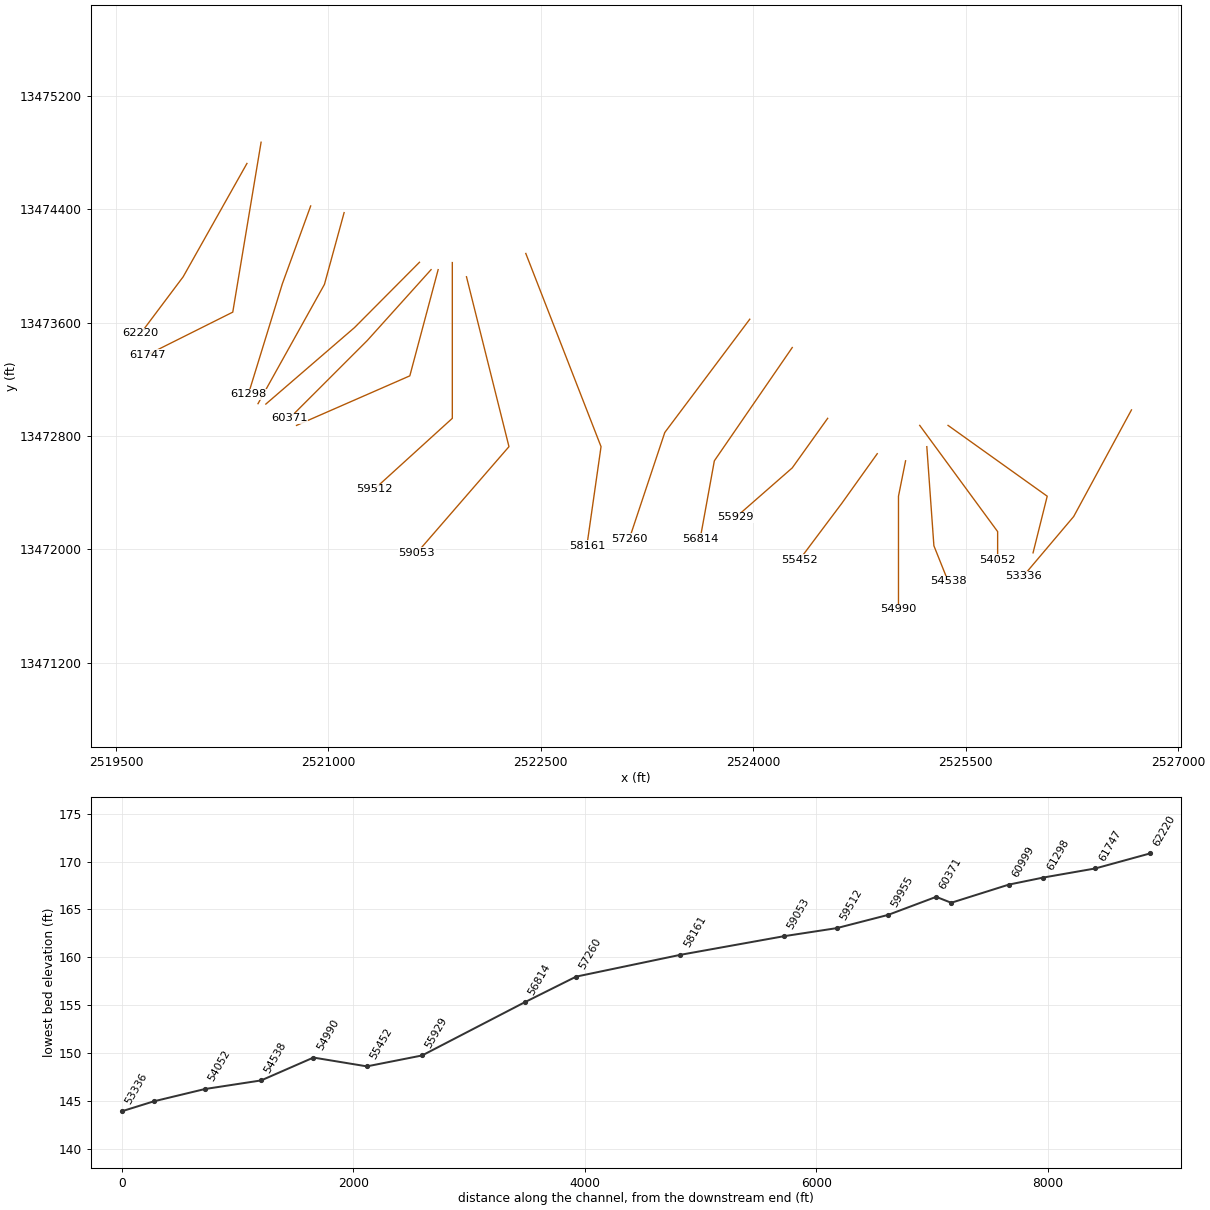
HEC-RAS study TURKEY CREEK.prj: TURKEY CREEK Base Level Engineering

--- TURKEY CREEK.g01 (geometry) --- (continued)

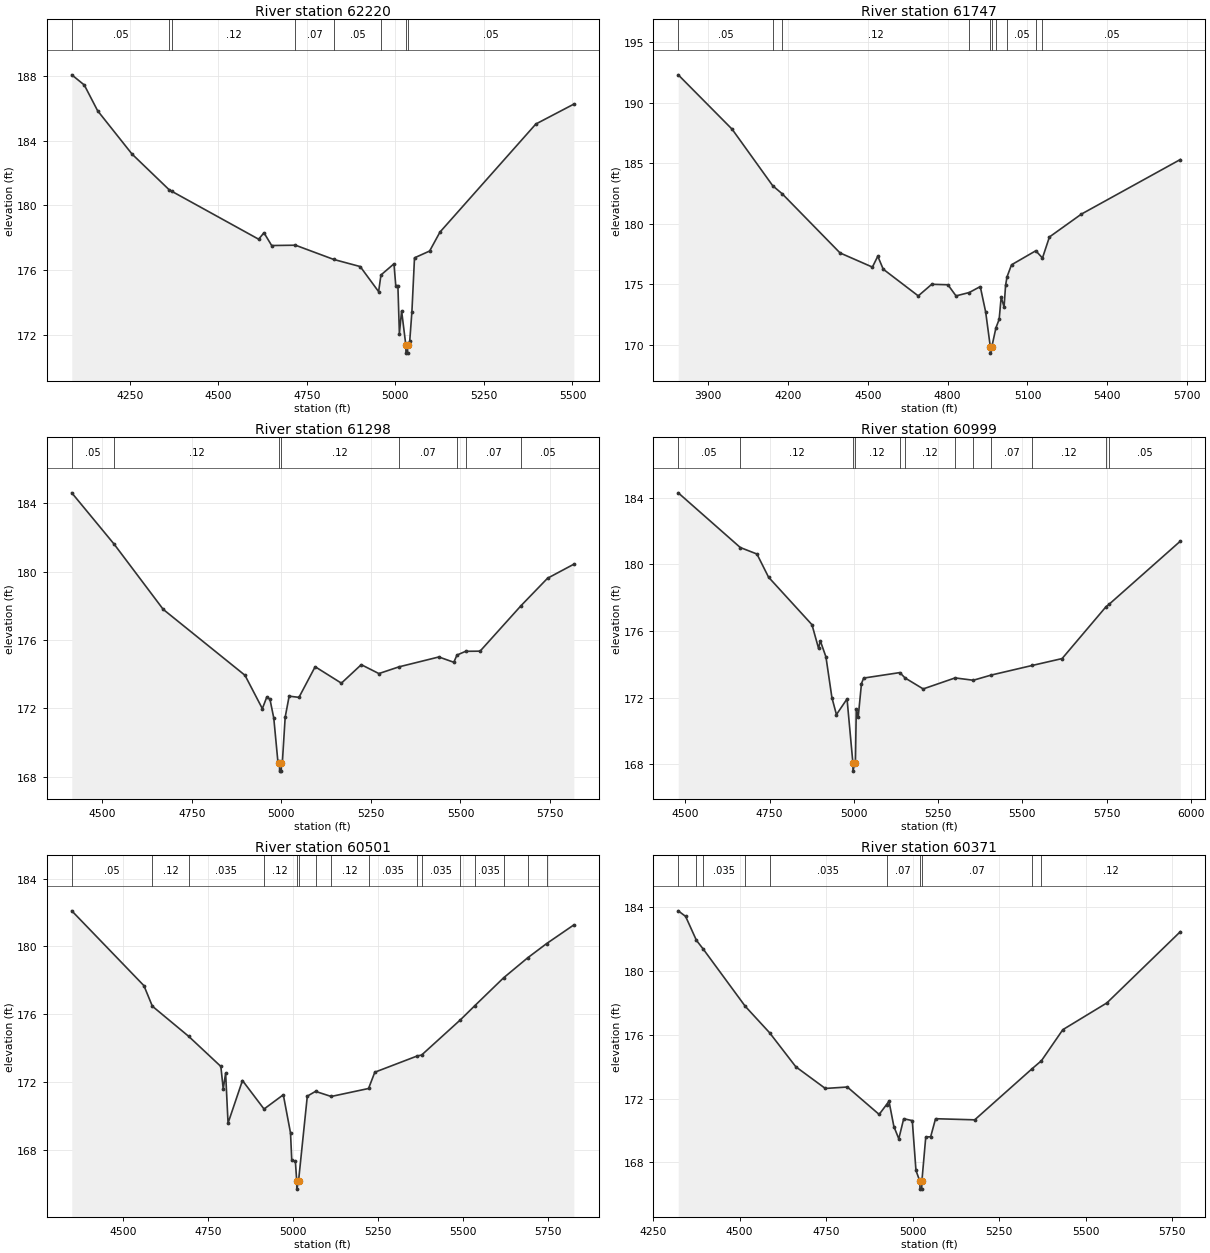
Type RM Length L Ch R = 1 ,62220   ,473,473,473
BEGIN DESCRIPTION:
TURKEY CREEK 92.0
END DESCRIPTION:
XS GIS Cut Line= 3
      2520425.02     13474725.03        2519975.       13473925.
      2519675.01     13473525.01
#Sta/Elev= 30
    4086  188.06  4121.4  187.43    4159  185.84  4255.9  183.17  4361.8  180.94
  4367.8  180.87  4613.8   177.9  4628.8   178.3  4650.5  177.51  4717.8  177.53
  4825.8  176.65  4900.6  176.21  4952.6  174.66  4959.2  175.69  4995.9  176.38
    5001  175.03    5007  175.03  5011.2  172.07  5017.5  173.47  5029.4  171.36
  5029.8  170.86  5034.3  170.86  5034.7  171.36  5040.4  171.59  5046.6  173.43
  5053.9  176.75  5096.6  177.17  5125.8  178.34  5396.6  185.02  5503.9  186.25
#Mann= 8 ,-1 , 0
    4086     .05       0  4361.8     .07       0  4367.8     .12       0
  4717.8     .07       0  4825.8     .05       0  4959.2     .07       0
  5029.4     .05       0  5034.7     .05       0
Bank Sta=5029.4,5034.7
XS Rating Curve= 0 ,0
Exp/Cntr=0.3,0.1

Type RM Length L Ch R = 1 ,61747   ,449,449,449
BEGIN DESCRIPTION:
TURKEY CREEK 91.0
END DESCRIPTION:
XS GIS Cut Line= 3
        2520525.       13474875.        2520325.       13473675.
      2519724.97     13473374.99
#Sta/Elev= 30
  3787.2  192.29    3990  187.79  4142.5  183.12    4178  182.46  4395.5  177.57
  4517.1   176.4  4537.4   177.3  4557.7  176.23  4689.5  174.02  4740.2  174.98
    4801  174.94  4831.4  174.02  4881.2   174.3  4922.6  174.79  4942.9  172.69
  4960.5  169.79  4960.9  169.29  4965.8  169.79  4981.6  171.39  4993.6  172.08
  5001.2  173.92  5012.1   173.1  5017.7  174.88  5023.1  175.59  5040.1  176.59
  5131.4  177.75  5156.4  177.15  5182.6  178.89  5302.8  180.78  5674.6  185.29
#Mann= 10 ,-1 , 0
  3787.2     .05       0  4142.5     .07       0    4178     .12       0
  4881.2     .05       0  4960.5     .05       0  4965.8     .05       0
  4981.6      .1       0  5023.1     .05       0  5131.4     .12       0
  5156.4     .05       0
Bank Sta=4960.5,4965.8
XS Rating Curve= 0 ,0
Exp/Cntr=0.3,0.1

Type RM Length L Ch R = 1 ,61298   ,299,299,299
BEGIN DESCRIPTION:
TURKEY CREEK 90.0
END DESCRIPTION:
XS GIS Cut Line= 3
      2520874.99     13474424.97        2520675.       13473875.
      2520434.76     13473094.86
#Sta/Elev= 30
  4414.9   184.6  4533.2   181.6  4670.2  177.79  4898.4  173.94  4946.9  171.99
  4959.5  172.68  4968.2  172.53  4978.8  171.44  4990.1  168.93  4994.7  168.84
  4995.1  168.34  4999.7  168.34  5000.1  168.84  5002.7  168.84  5010.6  171.49
  5021.7  172.72  5049.1  172.65  5094.3  174.44  5167.5  173.48    5223  174.56
  5272.2  174.04  5327.9  174.43  5439.6  175.01  5481.4   174.7  5490.1  175.12
  5514.3  175.34  5554.7  175.35  5669.1  178.01    5743  179.61  5816.4  180.43
#Mann= 8 ,-1 , 0
  4414.9     .05       0  4533.2     .12       0  4994.7     .05       0
  5000.1     .12       0  5327.9     .07       0  5490.1     .12       0
  5514.3     .07       0  5669.1     .05       0
Bank Sta=4994.7,5000.1
XS Rating Curve= 0 ,0
Exp/Cntr=0.3,0.1

Type RM Length L Ch R = 1 ,60999   ,498,498,498
BEGIN DESCRIPTION:
Mapping XS 834f4526
END DESCRIPTION:
XS GIS Cut Line= 3
      2521111.03     13474377.66      2520972.15     13473870.75
      2520503.26     13473028.57
#Sta/Elev= 30
  4478.9  184.29    4663  181.01  4712.4  180.62  4746.9  179.23  4875.7  176.38
  4895.2  174.96  4900.3  175.42  4917.1  174.45  4934.8  172.01  4948.2  170.99
  4979.7  171.93    4997   168.1  4997.4   167.6  5002.4   168.1  5004.5   168.1
  5007.1  171.32  5012.9  170.86  5022.5  172.85  5028.9  173.18  5136.4  173.51
  5151.7  173.19  5205.6  172.53  5300.3  173.19  5354.2  173.05  5407.2  173.36
  5529.6  173.94  5617.7  174.35    5748  177.46  5756.8   177.6  5968.4  181.39
#Mann= 12 ,-1 , 0
  4478.9     .05       0    4663     .12       0    4997     .05       0
  5002.4     .12       0  5136.4     .07       0  5151.7     .12       0
  5300.3     .07       0  5354.2     .12       0  5407.2     .07       0
  5529.6     .12       0    5748     .07       0  5756.8     .05       0
Bank Sta=4997,5002.4
XS Rating Curve= 0 ,0
Exp/Cntr=0.3,0.1

Type RM Length L Ch R = 1 ,60501   ,130,130,130
BEGIN DESCRIPTION:
Mapping XS b29cb0fd
END DESCRIPTION:
XS GIS Cut Line= 3
      2521643.08     13474027.13      2521184.75      13473566.2
      2520558.54     13473025.74
#Sta/Elev= 30
    4348   182.1  4560.3  177.69  4585.1  176.48  4691.6  174.71  4786.6  172.93
  4793.6  171.61  4800.7  172.53  4807.8  169.59  4850.2   172.1  4913.7  170.42
  4970.4  171.26  4991.6  169.01  4995.3  167.39  5005.9  167.33  5009.8   166.2
  5010.2   165.7  5015.3   166.2    5041  171.18  5065.2  171.46  5111.3  171.16
  5221.2  171.63  5239.6  172.59  5364.8  173.55  5377.2   173.6  5491.6  175.68
  5533.3   176.5  5618.4  178.15  5689.3  179.33  5745.1  180.17  5825.2  181.27
#Mann= 16 ,-1 , 0
    4348     .05       0  4585.1     .12       0  4691.6    .035       0
  4913.7     .12       0  5009.8     .05       0  5015.3     .12       0
  5065.2    .035       0  5111.3     .12       0  5221.2    .035       0
  5364.8     .12       0  5377.2    .035       0  5491.6     .07       0
  5533.3    .035       0  5618.4     .07       0  5689.3    .035       0
  5745.1     .05       0
Bank Sta=5009.8,5015.3
XS Rating Curve= 0 ,0
Exp/Cntr=0.3,0.1

Type RM Length L Ch R = 1 ,60371   ,416,416,416
BEGIN DESCRIPTION:
TURKEY CREEK 88.0
END DESCRIPTION:
XS GIS Cut Line= 3
      2521725.01     13473975.01        2521275.       13473475.
      2520725.01     13472925.01
#Sta/Elev= 30
  4322.5  183.79  4343.8  183.44    4375  181.94  4394.7  181.39    4516   177.8
  4586.3  176.14  4662.2     174  4747.4  172.64    4811  172.73  4902.9  171.01
  4924.4  171.63  4931.3  171.84  4945.5  170.25  4959.7  169.48  4973.9  170.74
  4998.7  170.62  5009.3  167.49  5020.5  166.82    5021  166.32  5025.9  166.32
  5026.4  166.82  5037.6  169.59  5051.8  169.61  5065.9  170.74    5179  170.67
  5345.4  173.89  5371.8  174.38  5433.6  176.33  5560.9  178.01    5773  182.48
#Mann= 10 ,-1 , 0
  4322.5    .035       0    4375     .05       0  4394.7    .035       0
    4516     .05       0  4586.3    .035       0  4924.4     .07       0
  5020.5     .05       0  5026.4     .07       0  5345.4     .05       0
  5371.8     .12       0
Bank Sta=5020.5,5026.4
XS Rating Curve= 0 ,0
Exp/Cntr=0.3,0.1

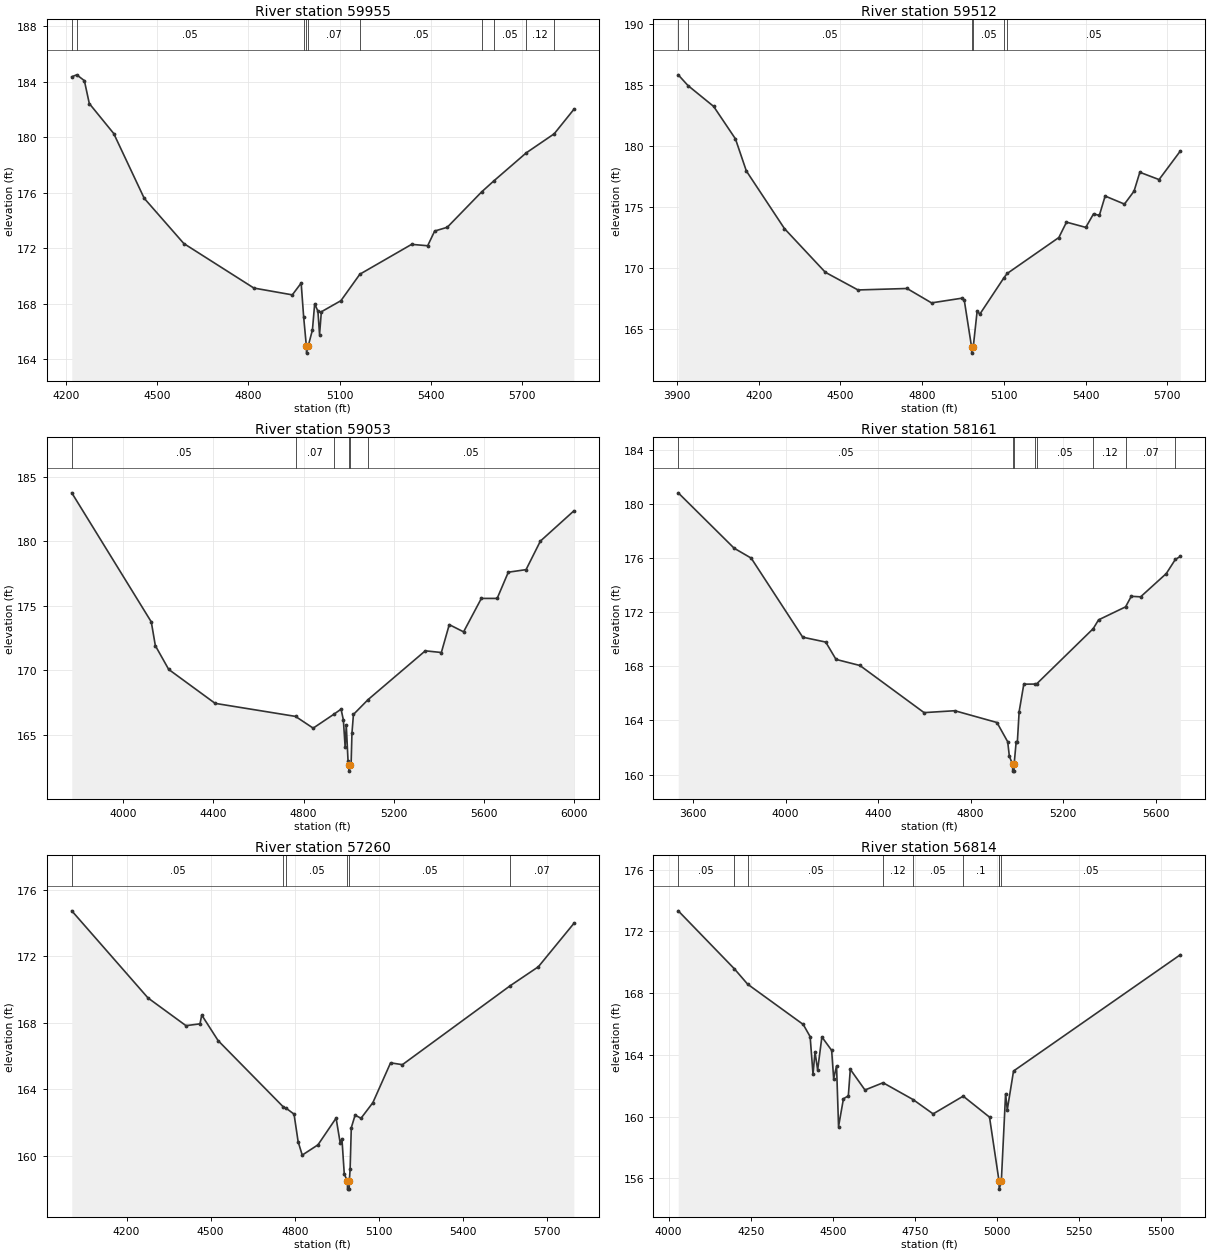
Type RM Length L Ch R = 1 ,59955   ,443,443,443
BEGIN DESCRIPTION:
TURKEY CREEK 87.0
END DESCRIPTION:
XS GIS Cut Line= 3
        2521775.     13473975.01        2521575.       13473225.
      2520775.03     13472875.01
#Sta/Elev= 30
  4219.6  184.35  4235.9  184.49    4261  184.07  4277.2  182.42  4357.4  180.26
  4457.6  175.59  4587.7  172.33  4817.9  169.12  4944.1  168.63  4973.2  169.48
  4981.3  167.06  4990.3  164.93  4990.8  164.43  4996.2  164.93  5010.2   166.1
  5017.6  167.99  5028.2  167.45  5033.6  165.77  5039.5  167.41  5103.8  168.21
  5166.1  170.12  5336.1  172.27  5388.8  172.17  5411.8  173.23  5453.1   173.5
    5566  176.05    5607  176.86  5712.9  178.87  5804.5  180.24    5869     182
#Mann= 10 ,-1 , 0
  4219.6    .035       0  4235.9     .05       0  4981.3     .07       0
  4990.3     .05       0  4996.2     .07       0  5166.1     .05       0
    5566     .07       0    5607     .05       0  5712.9     .12       0
  5804.5     .07       0
Bank Sta=4990.3,4996.2
XS Rating Curve= 0 ,0
Exp/Cntr=0.3,0.1

Type RM Length L Ch R = 1 ,59512   ,459,459,459
BEGIN DESCRIPTION:
TURKEY CREEK 86.0
END DESCRIPTION:
XS GIS Cut Line= 3
        2521875.     13474025.03        2521875.       13472925.
      2521325.03     13472425.02
#Sta/Elev= 30
  3904.7  185.87  3940.5  184.99  4034.7  183.28  4114.7  180.62  4154.7  177.99
  4294.7  173.26  4444.7  169.68  4564.7  168.23  4744.7  168.35  4834.7  167.17
  4944.7  167.55  4954.7  167.41  4981.7  163.55  4982.2  163.05  4987.8  163.55
  5002.2  166.52  5011.8  166.24  5099.6   169.2  5112.3  169.58  5302.1  172.53
  5330.1  173.79    5401  173.36  5429.4  174.47  5450.7  174.34    5472  175.93
  5542.9  175.27  5578.1  176.33  5599.4  177.88    5670  177.28    5748  179.62
#Mann= 6 ,-1 , 0
  3904.7    .035       0  3940.5     .05       0  4981.7     .05       0
  4987.8     .05       0  5099.6     .07       0  5112.3     .05       0
Bank Sta=4981.7,4987.8
XS Rating Curve= 0 ,0
Exp/Cntr=0.3,0.1

Type RM Length L Ch R = 1 ,59053   ,892,892,892
BEGIN DESCRIPTION:
TURKEY CREEK 85.0
END DESCRIPTION:
XS GIS Cut Line= 3
      2521974.99     13473925.03        2522275.       13472725.
      2521625.02     13471975.02
#Sta/Elev= 30
  3770.9  183.76    4124  173.76    4142  171.92  4201.3  170.08  4407.4  167.45
  4764.4  166.44  4842.9  165.53  4934.1   166.6  4966.6     167  4976.9  166.17
  4984.7  164.09  4989.8  165.75  4997.6  163.01  5002.2   162.7  5002.7   162.2
  5008.4   162.7  5011.2   162.7    5015  165.13  5021.6  166.59  5086.6  167.74
  5340.7  171.52    5412  171.39  5447.1  173.55  5510.7  172.99  5589.6  175.58
  5659.8  175.58  5709.2  177.61  5788.1  177.81  5851.7  180.02  6000.3  182.36
#Mann= 6 ,-1 , 0
  3770.9     .05       0  4764.4     .07       0  4934.1     .12       0
  5002.2     .05       0  5008.4     .12       0  5086.6     .05       0
Bank Sta=5002.2,5008.4
XS Rating Curve= 0 ,0
Exp/Cntr=0.3,0.1

Type RM Length L Ch R = 1 ,58161   ,901,901,901
BEGIN DESCRIPTION:
TURKEY CREEK 84.0
END DESCRIPTION:
XS GIS Cut Line= 3
      2522393.83     13474089.35        2522925.       13472725.
        2522825.     13472025.01
#Sta/Elev= 30
  3535.9  180.81  3777.7  176.72  3851.3  175.99  4074.2  170.15  4173.7  169.79
  4218.2  168.51  4321.6  168.06    4599  164.58  4731.7  164.72  4914.2  163.85
  4960.6  162.43  4967.8  161.36  4981.8  160.76  4982.3  160.26  4987.9  160.26
  4988.4  160.76  4997.3  162.43  5002.5  162.43  5010.1  164.65  5030.3  166.68
  5080.8  166.69  5086.3  166.71  5330.4  170.78  5353.6  171.43  5470.4  172.39
    5495  173.17  5535.4  173.13  5646.5  174.85  5685.5  175.89  5707.1  176.11
#Mann= 8 ,-1 , 0
  3535.9     .05       0  4981.8     .05       0  4988.4     .05       0
  5080.8     .07       0  5086.3     .05       0  5330.4     .12       0
  5470.4     .07       0  5685.5     .12       0
Bank Sta=4981.8,4988.4
XS Rating Curve= 0 ,0
Exp/Cntr=0.3,0.1

Type RM Length L Ch R = 1 ,57260   ,446,446,446
BEGIN DESCRIPTION:
TURKEY CREEK 83.0
END DESCRIPTION:
XS GIS Cut Line= 3
      2523974.99     13473624.99        2523375.       13472825.
      2523124.99     13472074.96
#Sta/Elev= 30
  4004.8  174.75  4276.7   169.5  4412.1  167.83  4462.1  167.94  4468.3  168.47
  4526.7  166.93  4759.5  162.93  4770.4  162.84  4797.5   162.5  4812.1  160.84
  4826.7  160.03  4882.9  160.65  4947.5  162.26  4962.1  160.76  4968.3  161.02
  4976.7  158.88  4987.8  158.48  4988.3  157.98  4994.2  157.98  4994.7  158.48
  4997.5  159.18  5001.7  161.68  5015.3  162.44  5036.4  162.25  5078.6  163.19
  5141.8  165.59    5184  165.48  5567.9  170.23  5668.9  171.38  5795.4  173.99
#Mann= 6 ,-1 , 0
  4004.8     .05       0  4759.5     .07       0  4770.4     .05       0
  4987.8     .05       0  4994.7     .05       0  5567.9     .07       0
Bank Sta=4987.8,4994.7
XS Rating Curve= 0 ,0
Exp/Cntr=0.3,0.1

Type RM Length L Ch R = 1 ,56814   ,885,885,885
BEGIN DESCRIPTION:
TURKEY CREEK 82.0
END DESCRIPTION:
XS GIS Cut Line= 3
      2524275.02     13473425.03        2523725.       13472625.
        2523625.     13472074.98
#Sta/Elev= 30
  4029.1  173.34  4200.1  169.58  4240.7  168.58    4410  165.97    4431  165.18
  4439.8  162.75  4445.9  164.18  4453.9  163.02  4466.8  165.16  4496.6  164.29
  4502.7  162.46  4511.5  163.28  4517.6  159.35  4532.5  161.15  4547.4  161.34
  4553.4  163.06  4598.1  161.72  4653.3  162.19  4744.6   161.1  4805.8  160.17
  4897.4  161.32  4977.6  159.96    5006   155.9  5006.6  155.79  5007.1  155.29
  5013.6  155.79  5026.6  161.48  5031.7  160.43  5050.8  162.95    5559  170.49
#Mann= 9 ,-1 , 0
  4029.1     .05       0  4200.1     .12       0  4240.7     .05       0
  4653.3     .12       0  4744.6     .05       0  4897.4      .1       0
    5006     .05       0  5006.6     .05       0  5013.6     .05       0
Bank Sta=5006.6,5013.6
XS Rating Curve= 0 ,0
Exp/Cntr=0.3,0.1

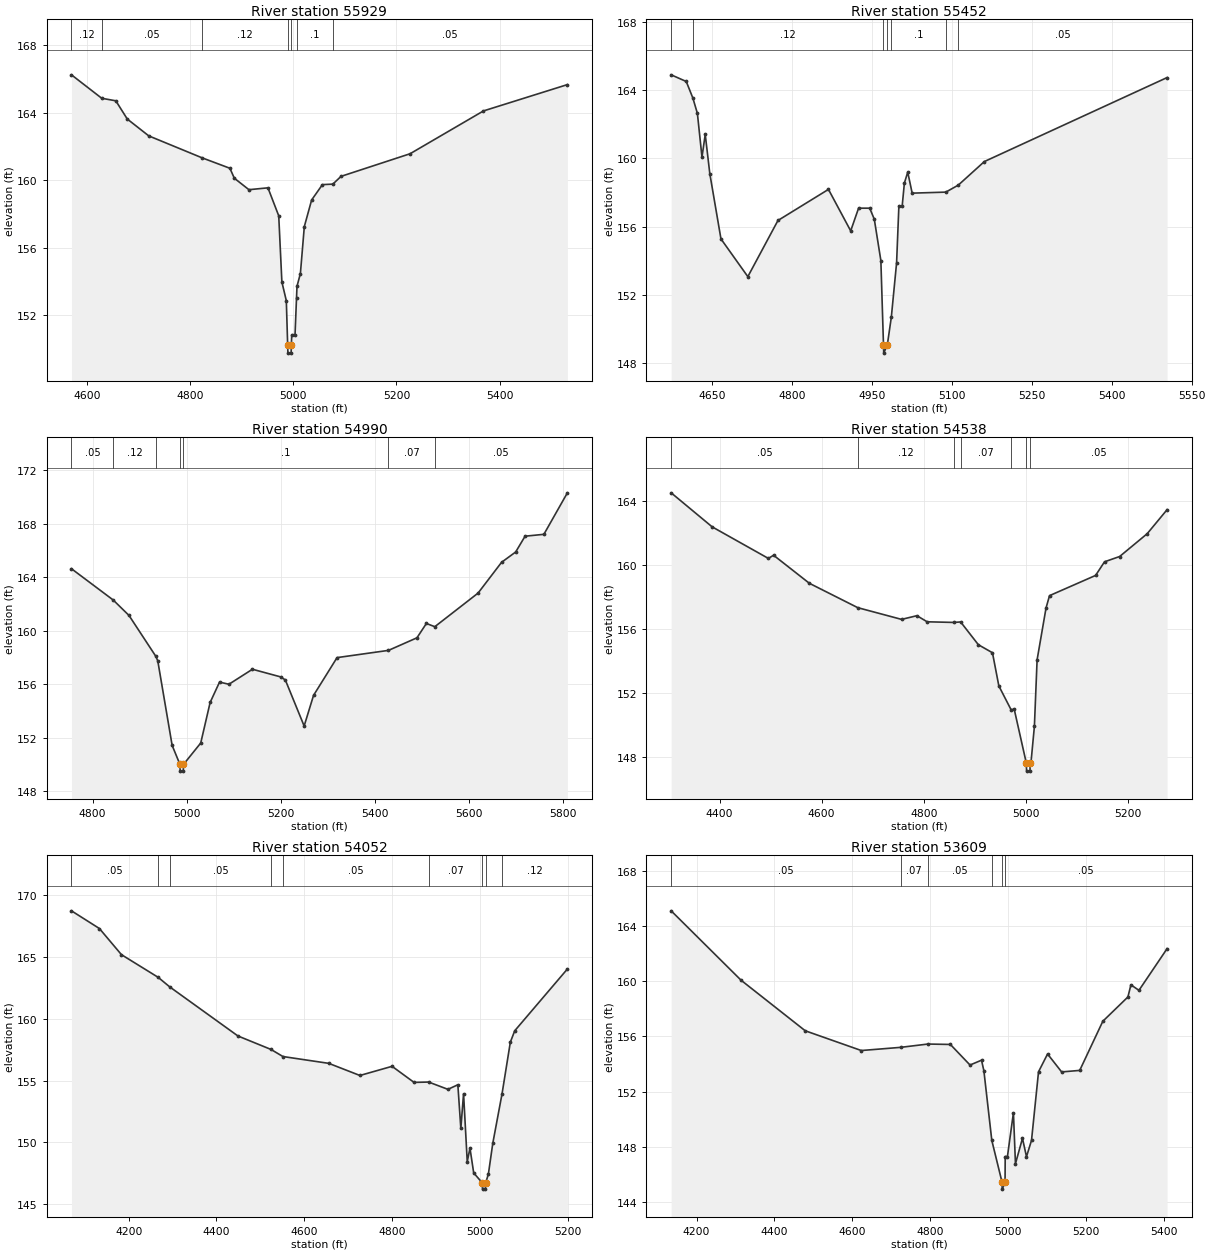
Type RM Length L Ch R = 1 ,55929   ,477,477,477
BEGIN DESCRIPTION:
TURKEY CREEK 81.0
END DESCRIPTION:
XS GIS Cut Line= 3
      2524525.01     13472925.01        2524275.       13472575.
      2523875.03     13472225.03
#Sta/Elev= 30
  4569.8  166.24  4628.5  164.85  4655.8   164.7    4678  163.62  4719.7  162.62
    4823  161.32    4877   160.7  4885.6  160.11  4913.9  159.43  4950.8  159.54
  4971.7  157.88  4977.8  153.96  4986.4  152.85    4989  150.24  4989.5  149.74
  4995.7  149.74  4996.2  150.24  4996.9  150.83  5003.3  150.83  5006.2  153.02
  5007.1   153.7  5013.7  154.46  5021.3  157.24  5035.5  158.82  5056.4  159.73
  5076.6  159.76  5092.5  160.22  5226.3  161.56  5368.7   164.1  5531.4  165.66
#Mann= 7 ,-1 , 0
  4569.8     .12       0  4628.5     .05       0    4823     .12       0
    4989     .05       0  4996.2     .12       0  5006.2      .1       0
  5076.6     .05       0
Bank Sta=4989,4996.2
XS Rating Curve= 0 ,0
Exp/Cntr=0.3,0.1

Type RM Length L Ch R = 1 ,55452   ,462,462,462
BEGIN DESCRIPTION:
TURKEY CREEK 80.0
END DESCRIPTION:
XS GIS Cut Line= 3
      2524875.01     13472675.02        2524625.       13472325.
      2524325.02     13471925.03
#Sta/Elev= 30
  4573.8   164.9  4602.1  164.51  4614.5  163.54    4623  162.64  4631.6  160.08
  4637.7  161.41  4646.3  159.11  4667.2  155.29  4717.6  153.08  4774.1  156.37
  4868.8  158.19  4910.5  155.76  4925.3  157.09  4946.2  157.09  4954.8  156.44
  4967.1  154.02    4972   149.1  4972.5   148.6  4979.3   149.1  4986.7   150.7
  4996.6  153.89  5000.9  157.22  5007.1  157.22  5011.2  158.56  5017.5   159.2
  5025.8  157.97  5088.9  158.03  5112.3  158.44  5161.2  159.82  5503.9  164.74
#Mann= 7 ,-1 , 0
  4573.8     .05       0  4614.5     .12       0    4972     .05       0
  4979.3     .12       0  4986.7      .1       0  5088.9     .12       0
  5112.3     .05       0
Bank Sta=4972,4979.3
XS Rating Curve= 0 ,0
Exp/Cntr=0.3,0.1

Type RM Length L Ch R = 1 ,54990   ,452,452,452
BEGIN DESCRIPTION:
TURKEY CREEK 79.0
END DESCRIPTION:
XS GIS Cut Line= 3
      2525075.01     13472625.03        2525025.       13472375.
        2525025.     13471574.99
#Sta/Elev= 30
  4755.2  164.64  4844.1   162.3  4877.6  161.15  4934.6   158.1  4938.8  157.76
  4969.4  151.44    4986  150.02  4986.5  149.52    4993  149.52  4993.5  150.02
  5030.2  151.62  5050.2  154.65  5070.2  156.17  5090.2  156.01  5140.2  157.13
  5200.2  156.56  5210.2  156.33  5250.2  152.89  5270.2  155.18  5320.2     158
  5429.6  158.54  5490.2  159.48  5510.2  160.55  5528.2  160.31  5620.2  162.82
  5670.2  165.12  5700.2  165.89  5720.2  167.07  5760.2  167.21  5810.2  170.31
#Mann= 7 ,-1 , 0
  4755.2     .05       0  4844.1     .12       0  4934.6      .1       0
    4986     .05       0  4993.5      .1       0  5429.6     .07       0
  5528.2     .05       0
Bank Sta=4986,4993.5
XS Rating Curve= 0 ,0
Exp/Cntr=0.3,0.1

Type RM Length L Ch R = 1 ,54538   ,486,486,486
BEGIN DESCRIPTION:
TURKEY CREEK 78.0
END DESCRIPTION:
XS GIS Cut Line= 3
        2525225.     13472724.95        2525275.       13472025.
        2525375.       13471775.
#Sta/Elev= 30
  4305.3  164.48  4385.5  162.36  4495.7  160.39  4505.8  160.59  4575.9  158.84
  4670.7  157.32  4756.4  156.59  4786.5  156.82  4806.5  156.44  4858.4   156.4
  4872.1  156.43  4906.8  155.01  4934.4  154.51  4946.9  152.44  4970.8  150.96
    4977  150.99  5000.7  147.63  5001.2  147.13  5007.8  147.13  5008.3  147.63
  5009.7  147.63  5016.5  149.92  5021.8  154.07  5039.3   157.3  5046.1  158.07
  5136.3  159.33  5153.8  160.18  5183.4  160.51  5237.3  161.93  5276.3  163.43
#Mann= 7 ,-1 , 0
  4305.3     .05       0  4670.7     .12       0  4858.4    .035       0
  4872.1     .07       0  4970.8     .05       0  5000.7     .05       0
  5008.3     .05       0
Bank Sta=5000.7,5008.3
XS Rating Curve= 0 ,0
Exp/Cntr=0.3,0.1

Type RM Length L Ch R = 1 ,54052   ,443,443,443
BEGIN DESCRIPTION:
TURKEY CREEK 77.0
END DESCRIPTION:
XS GIS Cut Line= 3
      2525174.97     13472875.03        2525725.       13472125.
        2525725.       13471925.
#Sta/Elev= 30
  4069.5  168.71  4133.2  167.28  4183.4  165.17    4267  163.34  4293.3  162.57
  4448.9   158.6  4524.4  157.51  4551.4  156.94  4655.8  156.39  4726.8  155.41
  4800.1  156.15  4850.2  154.85  4883.4  154.88  4927.4  154.29    4950  154.66
  4956.8  151.13    4963  153.94  4971.4  148.45  4977.6  149.54  4986.1  147.54
  5005.8  146.73  5006.3  146.23  5012.9  146.23  5013.4  146.73  5019.6  147.45
  5029.6  149.93  5050.7  153.93  5069.6   158.1  5079.6  159.02  5199.6  164.01
#Mann= 9 ,-1 , 0
  4069.5     .05       0    4267    .035       0  4293.3     .05       0
  4524.4     .07       0  4551.4     .05       0  4883.4     .07       0
  5005.8     .05       0  5013.4     .07       0  5050.7     .12       0
Bank Sta=5005.8,5013.4
XS Rating Curve= 0 ,0
Exp/Cntr=0.3,0.1

Type RM Length L Ch R = 1 ,53609   ,273,273,273
BEGIN DESCRIPTION:
TURKEY CREEK 76.0
END DESCRIPTION:
XS GIS Cut Line= 3
      2525374.96     13472875.03        2526075.       13472375.
        2525975.     13471974.99
#Sta/Elev= 30
  4134.9   165.1  4314.4  160.07    4479  156.41  4622.8  154.98  4723.7  155.21
  4793.9  155.45  4851.4  155.42  4901.8  153.93  4931.3  154.28  4937.4  153.51
  4957.7  148.47    4984  145.44  4984.5  144.94  4991.7  145.44  4992.1   147.3
  4997.8   147.3  5013.2  150.47  5018.4  146.78  5036.4  148.62  5046.7  147.29
  5059.6  148.47  5077.6  153.44  5100.8  154.73  5136.9  153.43  5183.3  153.54
  5242.6   157.1    5307  158.86  5314.7  159.74  5335.3  159.34  5407.5  162.36
#Mann= 6 ,-1 , 0
  4134.9     .05       0  4723.7     .07       0  4793.9     .05       0
  4957.7      .1       0    4984     .05       0  4991.7     .05       0
Bank Sta=4984,4991.7
XS Rating Curve= 0 ,0
Exp/Cntr=0.3,0.1

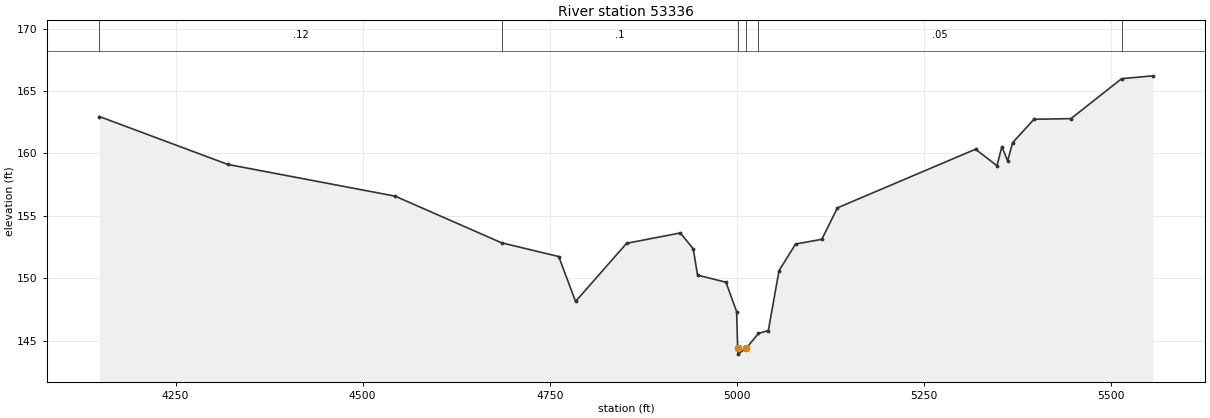
Type RM Length L Ch R = 1 ,53336   ,130,130,130
BEGIN DESCRIPTION:
Mapping XS f616cd1b
END DESCRIPTION:
XS GIS Cut Line= 3
       2526669.9     13472984.53      2526261.91     13472231.49
      2525906.04     13471810.51
#Sta/Elev= 30
  4148.1  162.95  4319.8  159.11  4543.3  156.57  4685.6  152.83    4762  151.73
  4784.5  148.13  4852.7  152.79  4924.6  153.62  4941.8  152.34  4947.5  150.24
  4985.5  149.67  4999.7  147.32  5001.1  144.41  5001.6  143.91  5012.9  144.41
  5028.9  145.57  5042.1   145.8  5056.4   150.6  5078.5  152.73  5113.6  153.11
  5134.4  155.63    5319  160.33  5347.6  159.01  5354.2  160.54  5361.9  159.39
  5368.5  160.85  5397.1  162.73  5446.5  162.78  5514.2  165.98  5555.8  166.21
#Mann= 6 ,-1 , 0
  4148.1     .12       0  4685.6      .1       0  5001.1     .05       0
  5012.9      .1       0  5028.9     .05       0  5514.2     .07       0
Bank Sta=5001.1,5012.9
XS Rating Curve= 0 ,0
Exp/Cntr=0.3,0.1