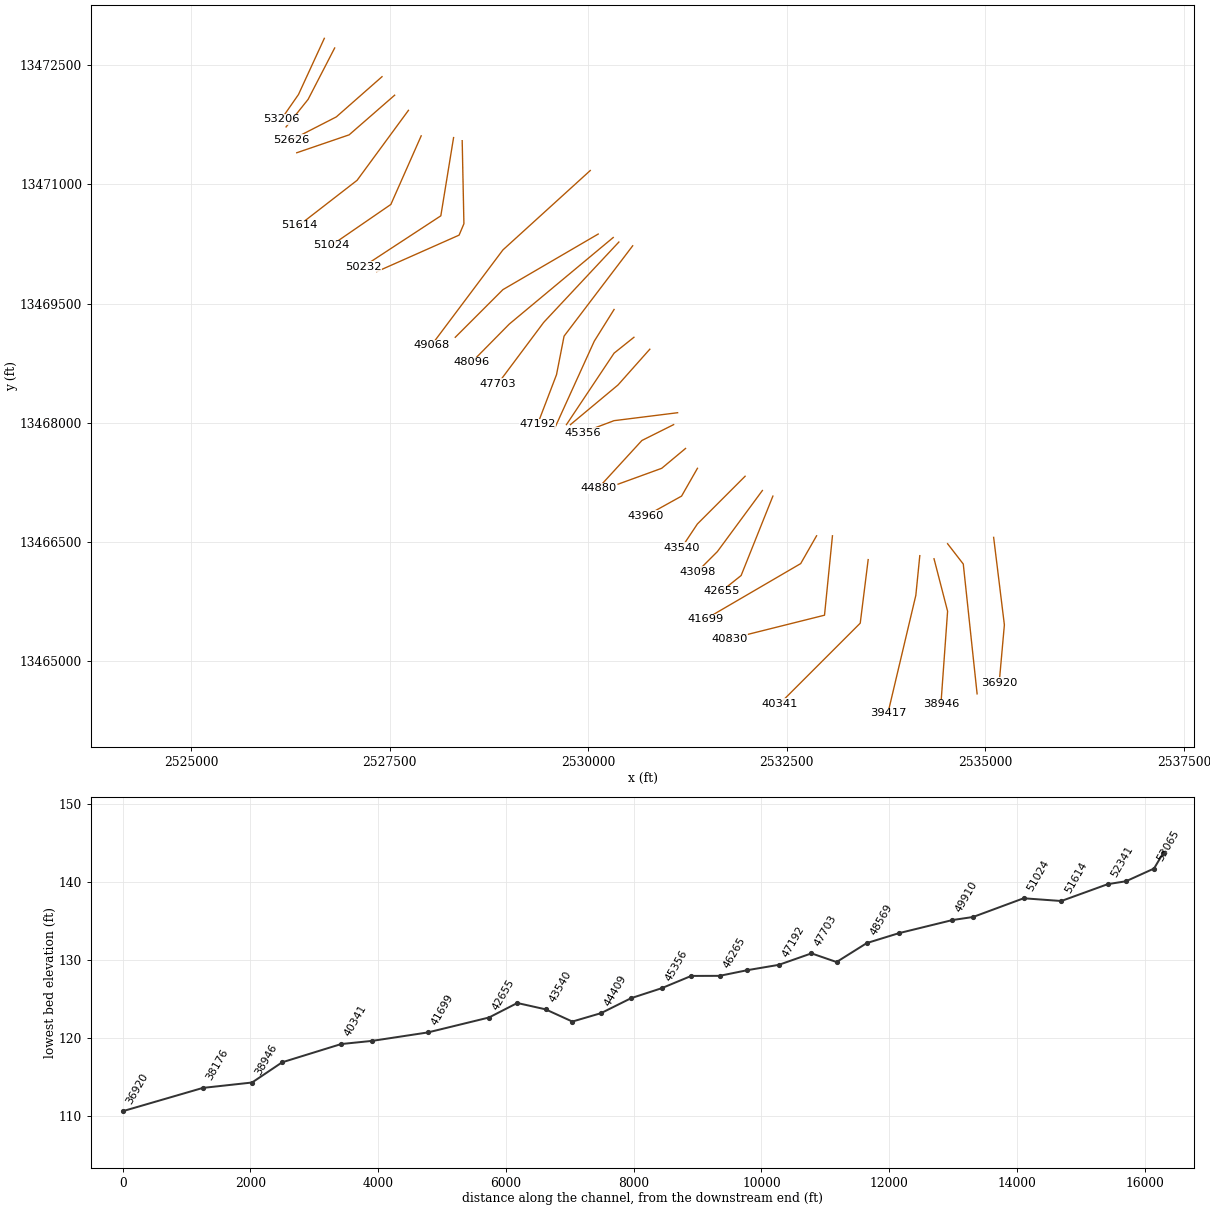
HEC-RAS study TURKEY CREEK.prj: TURKEY CREEK Base Level Engineering

--- TURKEY CREEK.g01 (geometry) --- (continued)

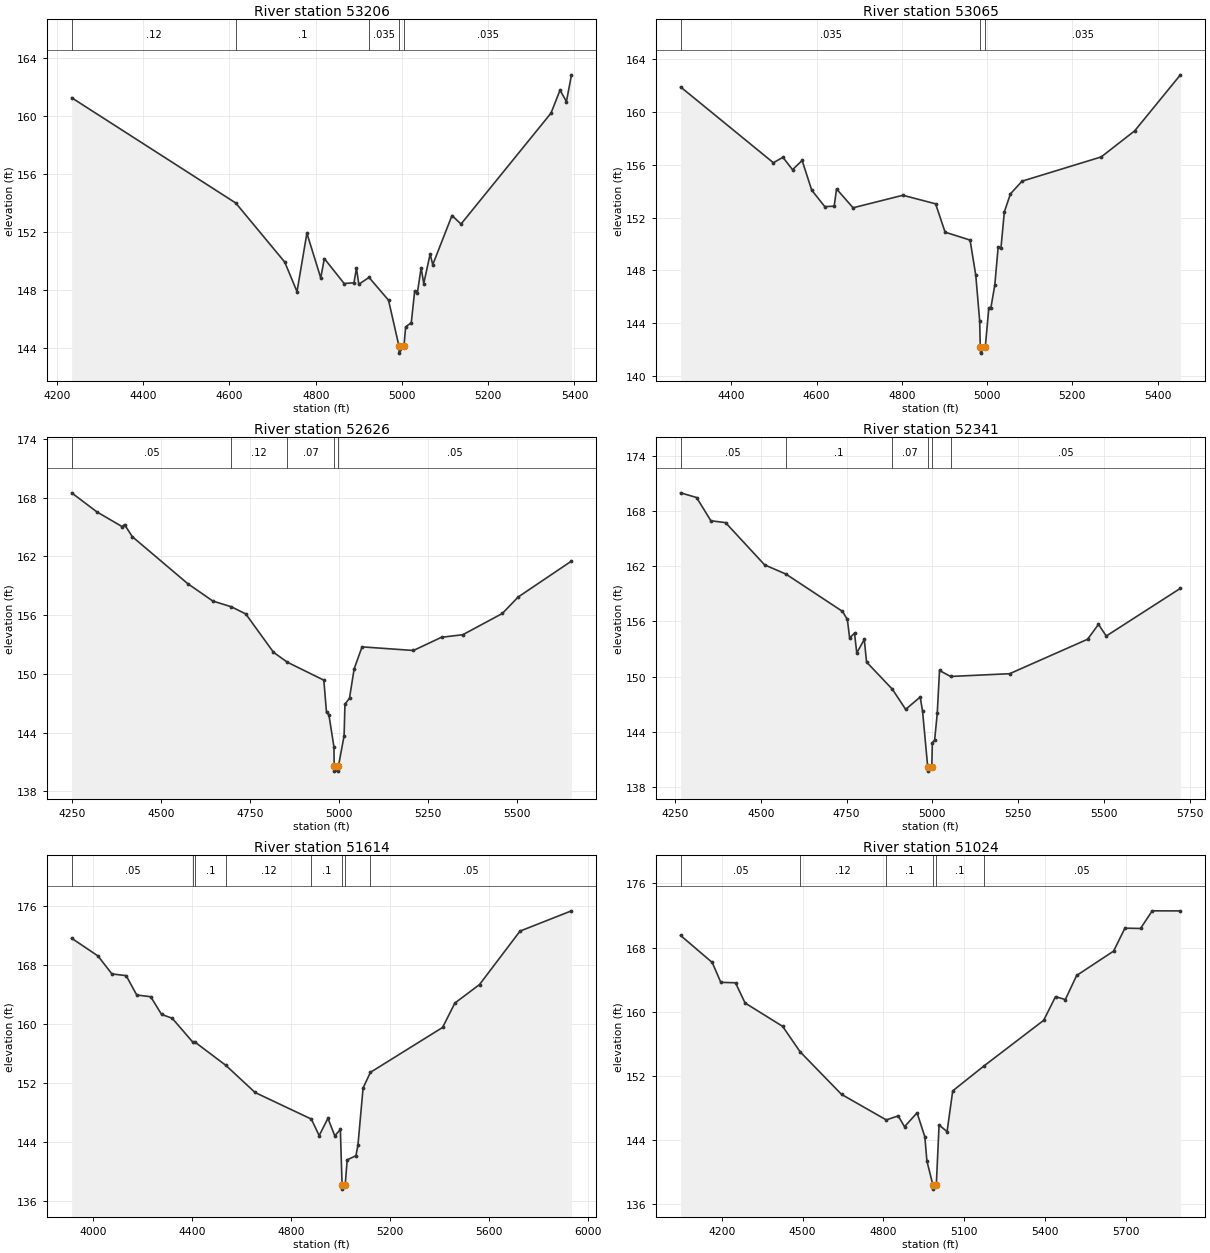
Type RM Length L Ch R = 1 ,53206   ,141,141,141
BEGIN DESCRIPTION:
Mapping XS 5c2cfe70
END DESCRIPTION:
XS GIS Cut Line= 3
      2526676.13     13472839.74      2526350.63     13472132.32
      2526133.66     13471819.89
#Sta/Elev= 30
    4234  161.26  4614.6     154  4728.1  149.93  4756.6  147.89  4779.5  151.92
  4811.6  148.84    4820  150.17  4865.9  148.45  4888.7   148.5  4894.4  149.51
  4899.9   148.4  4923.6  148.87  4968.8   147.3  4992.9  144.15  4993.4  143.65
  5004.7  144.15  5008.5  145.46  5021.6  145.75  5029.5  147.95  5035.6  147.78
  5044.4  149.53  5050.5  148.45  5065.3  150.48  5071.4  149.75    5116  153.14
  5136.9  152.55  5345.6   160.2  5366.5  161.78  5381.4     161  5393.1  162.84
#Mann= 5 ,-1 , 0
    4234     .12       0  4614.6      .1       0  4923.6    .035       0
  4992.9    .035       0  5004.7    .035       0
Bank Sta=4992.9,5004.7
XS Rating Curve= 0 ,0
Exp/Cntr=0.3,0.1

Type RM Length L Ch R = 1 ,53065   ,439,439,439
BEGIN DESCRIPTION:
Mapping XS 1a40ae46
END DESCRIPTION:
XS GIS Cut Line= 3
      2526806.36     13472718.27      2526472.15     13472071.56
       2526194.4     13471724.36
#Sta/Elev= 30
  4280.9  161.91  4498.5  156.16    4521  156.57  4543.5  155.63    4566  156.33
  4588.5  154.08  4619.1  152.83  4641.2  152.86  4646.8  154.17  4685.5  152.74
  4802.4  153.69  4879.2  153.04  4901.4  150.89    4960  150.29  4973.4  147.62
  4982.5  144.17    4984  142.21  4984.5  141.71  4995.8  142.21  5004.1  145.16
  5008.9  145.16    5018  146.87    5026  149.79  5032.4  149.66  5040.4  152.43
  5054.8   153.8    5082  154.76  5267.7   156.6  5346.2  158.58  5453.5  162.83
#Mann= 3 ,-1 , 0
  4280.9    .035       0    4984    .035       0  4995.8    .035       0
Bank Sta=4984,4995.8
XS Rating Curve= 0 ,0
Exp/Cntr=0.3,0.1

Type RM Length L Ch R = 1 ,52626   ,285,285,285
BEGIN DESCRIPTION:
Mapping XS 4fc6fd04
END DESCRIPTION:
XS GIS Cut Line= 3
      2527402.71     13472356.86      2526826.32     13471849.92
      2526260.17     13471559.94
#Sta/Elev= 30
  4249.4   168.5    4320  166.56  4391.1  165.05  4397.8  165.26  4419.5  164.03
  4575.2  159.23  4645.9  157.45  4698.1  156.86  4738.4  156.13  4816.2  152.22
  4854.7  151.21  4957.6  149.37  4965.1  146.07  4971.8  145.84    4986  142.55
  4986.7  140.58  4987.2  140.08  4998.1  140.08  4998.6  140.58  5014.5  143.69
  5016.9   146.9  5029.7  147.54  5042.7  150.52  5064.9  152.77  5209.1   152.4
  5288.1  153.75  5347.9  154.01  5458.9  156.18  5503.3  157.86  5653.1  161.53
#Mann= 5 ,-1 , 0
  4249.4     .05       0  4698.1     .12       0  4854.7     .07       0
  4986.7     .05       0  4998.6     .05       0
Bank Sta=4986.7,4998.6
XS Rating Curve= 0 ,0
Exp/Cntr=0.3,0.1

Type RM Length L Ch R = 1 ,52341   ,727,727,727
BEGIN DESCRIPTION:
Mapping XS 16dff6f3
END DESCRIPTION:
XS GIS Cut Line= 3
      2527561.58     13472123.66      2526988.65     13471624.51
      2526328.96     13471398.83
#Sta/Elev= 30
  4266.2  169.99  4312.8  169.48  4354.5  166.95  4397.2  166.75  4511.2  162.15
  4573.3  161.15  4738.1  157.09  4752.3  156.21    4759   154.2  4773.2  154.72
  4779.8  152.57  4801.7  154.04  4808.3  151.58  4883.6  148.62  4922.3  146.43
  4964.6  147.77  4971.6  146.24  4986.5  140.21    4987  139.71  4998.5  140.21
  5000.1  142.79  5006.8  143.09  5014.4  145.99    5021  150.66  5053.2  150.01
  5225.4  150.31  5452.7  154.06  5484.4  155.68  5507.1  154.41  5723.3   159.6
#Mann= 6 ,-1 , 0
  4266.2     .05       0  4573.3      .1       0  4883.6     .07       0
  4986.5     .05       0  4998.5     .07       0  5053.2     .05       0
Bank Sta=4986.5,4998.5
XS Rating Curve= 0 ,0
Exp/Cntr=0.3,0.1

Type RM Length L Ch R = 1 ,51614   ,590,590,590
BEGIN DESCRIPTION:
Mapping XS 337e5b15
END DESCRIPTION:
XS GIS Cut Line= 3
       2527735.2     13471932.71      2527088.47     13471051.59
      2526354.93     13470482.99
#Sta/Elev= 30
  3913.6  171.58    4020  169.18  4076.4  166.74    4134  166.51  4176.7  163.88
  4233.3  163.65    4277  161.25  4320.1  160.73  4404.5  157.45  4412.4  157.49
  4537.4  154.33  4655.2  150.66  4882.9  147.05  4914.4  144.81  4949.9  147.16
  4977.6  144.78  5000.1  145.64  5007.1  138.05  5007.6  137.55  5019.5  138.05
  5027.7  141.52    5063  142.08  5071.2  143.51    5092  151.27  5121.6  153.39
  5413.4  159.48  5463.2  162.79  5562.8   165.3  5726.6  172.55  5934.7   175.3
#Mann= 8 ,-1 , 0
  3913.6     .05       0  4404.5     .12       0  4412.4      .1       0
  4537.4     .12       0  4882.9      .1       0  5007.1     .05       0
  5019.5      .1       0  5121.6     .05       0
Bank Sta=5007.1,5019.5
XS Rating Curve= 0 ,0
Exp/Cntr=0.3,0.1

Type RM Length L Ch R = 1 ,51024   ,792,792,792
BEGIN DESCRIPTION:
Mapping XS d75ae960
END DESCRIPTION:
XS GIS Cut Line= 3
      2527895.77      13471611.5      2527513.82     13470747.77
      2526762.93     13470231.26
#Sta/Elev= 30
  4047.1  169.52  4164.6  166.15  4196.4  163.68    4251  163.62  4286.6   161.1
    4426  158.19  4491.1  155.01  4644.7  149.71  4810.7  146.53  4855.2  147.03
  4878.5  145.68  4925.1  147.41  4953.9  144.43  4961.7  141.39    4984   138.4
  4984.5   137.9  4996.5   138.4  5006.8  145.89  5036.5  145.07  5057.5  150.15
  5173.4  153.25  5395.1  158.94  5439.2  161.89  5475.6  161.53  5517.5  164.53
  5654.8  167.57  5696.8  170.43  5754.7  170.39  5798.2  172.59  5902.9  172.58
#Mann= 6 ,-1 , 0
  4047.1     .05       0  4491.1     .12       0  4810.7      .1       0
    4984     .05       0  4996.5      .1       0  5173.4     .05       0
Bank Sta=4984,4996.5
XS Rating Curve= 0 ,0
Exp/Cntr=0.3,0.1

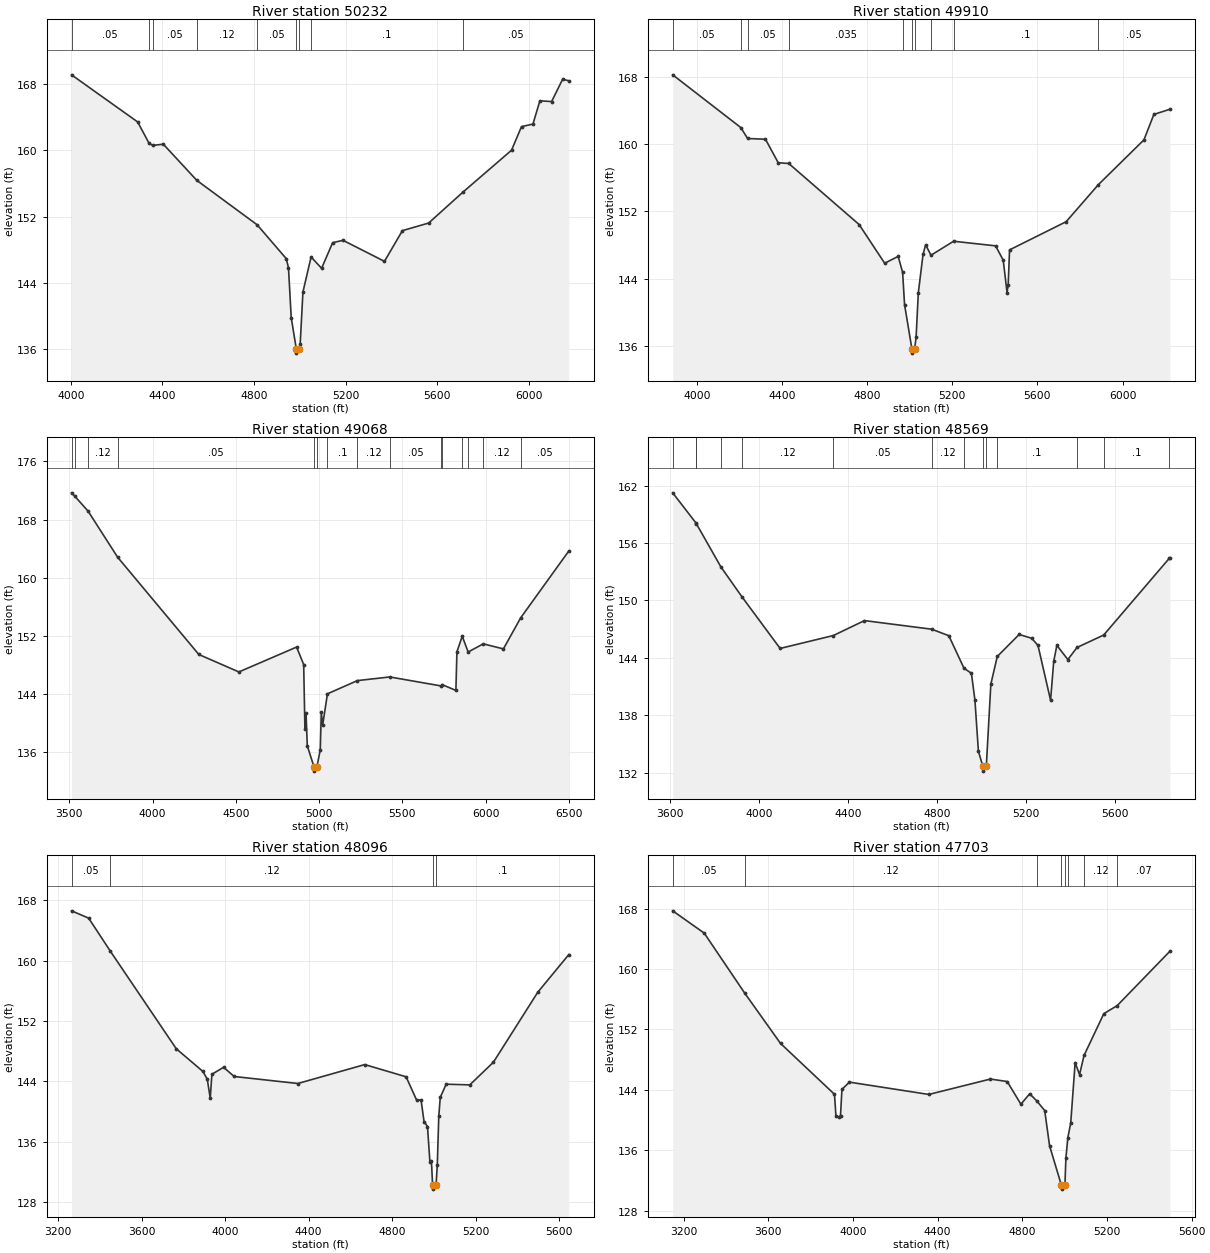
Type RM Length L Ch R = 1 ,50232   ,322,322,322
BEGIN DESCRIPTION:
Mapping XS 695e9a25
END DESCRIPTION:
XS GIS Cut Line= 3
      2528303.75     13471589.78      2528143.16     13470604.54
      2527162.22     13469962.16
#Sta/Elev= 30
  4003.2  169.13  4291.7  163.44  4341.7  160.86  4357.4   160.6  4403.9  160.75
  4549.9  156.38  4813.4  151.01  4940.2  146.93  4950.3  145.82  4962.2   139.8
  4984.5     136    4985   135.5  4997.1     136  5001.4   136.6  5013.4  142.89
    5049  147.12  5094.9  145.75  5143.1  148.85  5188.4  149.13  5369.3  146.59
  5447.6   150.3  5562.2  151.22    5712  154.96    5924  160.02  5967.5  162.87
  6017.5  163.18  6047.7  165.99    6099   165.9  6147.1   168.6    6174  168.41
#Mann= 9 ,-1 , 0
  4003.2     .05       0  4341.7    .035       0  4357.4     .05       0
  4549.9     .12       0  4813.4     .05       0  4984.5     .05       0
  4997.1     .05       0    5049      .1       0    5712     .05       0
Bank Sta=4984.5,4997.1
XS Rating Curve= 0 ,0
Exp/Cntr=0.3,0.1

Type RM Length L Ch R = 1 ,49910   ,842,842,842
BEGIN DESCRIPTION:
Mapping XS 17a0dfe3
END DESCRIPTION:
XS GIS Cut Line= 4
      2528412.26     13471550.68      2528433.96     13470504.72
       2528373.2     13470361.49      2527335.91     13469901.44
#Sta/Elev= 30
  3886.5  168.29  4206.6     162  4238.2   160.7  4322.3  160.61  4382.3  157.81
  4431.7  157.72  4762.4  150.44  4882.4  145.83  4945.8  146.64  4966.7  144.75
  4975.8   140.9  5010.4  135.61  5010.9  135.11    5023  135.61  5030.1     137
  5040.4  142.27  5062.7  146.88  5074.9  148.03    5100  146.78  5206.2  148.45
  5403.5   147.9  5439.5  146.19  5457.4  142.33  5462.8  143.27  5469.2  147.42
  5735.2  150.78  5886.2  155.19  6100.7  160.54  6147.3  163.57    6223  164.19
#Mann= 10 ,-1 , 0
  3886.5     .05       0  4206.6    .035       0  4238.2     .05       0
  4431.7    .035       0  4966.7     .05       0  5010.4     .05       0
    5023     .05       0    5100    .035       0  5206.2      .1       0
  5886.2     .05       0
Bank Sta=5010.4,5023
XS Rating Curve= 0 ,0
Exp/Cntr=0.3,0.1

Type RM Length L Ch R = 1 ,49068   ,499,499,499
BEGIN DESCRIPTION:
TURKEY CREEK 66.0
END DESCRIPTION:
XS GIS Cut Line= 3
      2530024.97     13471174.98        2528925.       13470175.
      2528024.98     13468974.98
#Sta/Elev= 30
  3512.8  171.69  3531.8  171.24    3612  169.18  3789.6  162.84  4277.4  149.46
  4517.9  147.06  4864.6  150.48  4907.1  148.08  4914.6  139.17  4921.3  141.35
  4928.8   136.9  4970.3  133.92  4970.8  133.42  4985.8  133.92  5006.7  136.36
  5012.9  141.51  5021.2  139.77  5049.8  144.05  5229.8  145.87  5424.3  146.37
  5733.6  145.13  5736.9  145.33  5821.2  144.52  5827.5  149.84  5859.5  151.97
  5894.8   149.8  5985.4  150.92  6106.7  150.23  6210.6  154.51  6499.4  163.69
#Mann= 15 ,-1 , 0
  3512.8     .07       0  3531.8     .05       0    3612     .12       0
  3789.6     .05       0  4970.3     .05       0  4985.8     .05       0
  5049.8      .1       0  5229.8     .12       0  5424.3     .05       0
  5733.6     .12       0  5736.9      .1       0  5859.5     .12       0
  5894.8      .1       0  5985.4     .12       0  6210.6     .05       0
Bank Sta=4970.3,4985.8
XS Rating Curve= 0 ,0
Exp/Cntr=0.3,0.1

Type RM Length L Ch R = 1 ,48569   ,473,473,473
BEGIN DESCRIPTION:
TURKEY CREEK 65.0
END DESCRIPTION:
XS GIS Cut Line= 3
      2530125.04     13470375.02        2528925.       13469675.
      2528325.01     13469075.01
#Sta/Elev= 30
  3610.7  161.24  3715.3  158.09  3716.7  158.03  3827.5   153.5  3922.4  150.37
  4094.1  144.98  4333.7  146.33  4473.6  147.89    4776  146.99  4853.2  146.31
  4921.3  142.92  4954.9  142.38  4970.6  139.61  4986.3  134.25  5006.3  132.66
  5006.8  132.16  5021.9  132.66  5042.4  141.26  5071.3  144.14  5169.7  146.44
  5226.3  146.04  5254.5  145.29  5311.1  139.57  5325.3  143.63  5339.4   145.3
  5388.9  143.82  5430.1  145.08  5550.1  146.38  5846.2  154.42  5848.5  154.42
#Mann= 14 ,-1 , 0
  3610.7     .12       0  3715.3     .05       0  3716.7     .12       0
  3827.5     .05       0  3922.4     .12       0  4333.7     .05       0
    4776     .12       0  4921.3     .05       0  5006.3     .05       0
  5021.9     .05       0  5071.3      .1       0  5430.1     .12       0
  5550.1      .1       0  5846.2     .05       0
Bank Sta=5006.3,5021.9
XS Rating Curve= 0 ,0
Exp/Cntr=0.3,0.1

Type RM Length L Ch R = 1 ,48096   ,393,393,393
BEGIN DESCRIPTION:
Mapping XS 55197b41
END DESCRIPTION:
XS GIS Cut Line= 3
      2530314.14     13470331.55      2529005.14      13469241.3
      2528530.37      13468759.6
#Sta/Elev= 30
  3265.1  166.62  3347.1  165.65  3451.6  161.24  3766.3  148.34  3893.9  145.33
  3914.7  144.31    3929  141.77  3936.8  144.95  3992.8  145.88  4043.6  144.66
  4348.2  143.73  4668.4  146.24  4866.3  144.62  4916.8  141.52  4937.9  141.56
  4952.2  138.69  4968.7  138.03  4980.3  133.32  4987.4  133.48  4993.3  130.23
  4993.8  129.73  5009.7  130.23  5015.7  132.98  5022.7  139.36  5029.8  141.89
  5058.1  143.64  5171.2  143.55  5284.4  146.56  5496.5  155.83    5645  160.82
#Mann= 4 ,-1 , 0
  3265.1     .05       0  3451.6     .12       0  4993.3     .05       0
  5009.7      .1       0
Bank Sta=4993.3,5009.7
XS Rating Curve= 0 ,0
Exp/Cntr=0.3,0.1

Type RM Length L Ch R = 1 ,47703   ,511,511,511
BEGIN DESCRIPTION:
Mapping XS cb9df427
END DESCRIPTION:
XS GIS Cut Line= 3
      2530385.44     13470274.66      2529439.28      13469263.4
      2528862.01     13468490.81
#Sta/Elev= 30
  3148.3   167.7  3297.1  164.75  3488.5   156.8  3657.6  150.14  3912.6   143.4
  3919.5  140.51  3933.6  140.34    3941  140.59  3947.8  144.06  3983.2  145.01
  4358.1  143.38  4649.3  145.42  4728.6  145.09  4793.2  142.09  4834.8  143.47
  4867.3  142.55  4905.7  141.25  4928.7  136.58  4984.8  131.34  4985.3  130.84
  5001.2  131.34  5005.8  134.93    5015  137.65  5028.7  139.61  5049.5  147.59
  5070.4  146.01  5091.5  148.54    5185  154.08  5248.4  155.15  5497.6  162.36
#Mann= 8 ,-1 , 0
  3148.3     .05       0  3488.5     .12       0  4867.3    .045       0
  4984.8    .045       0  5001.2    .045       0    5015      .1       0
  5091.5     .12       0  5248.4     .07       0
Bank Sta=4984.8,5001.2
XS Rating Curve= 0 ,0
Exp/Cntr=0.3,0.1

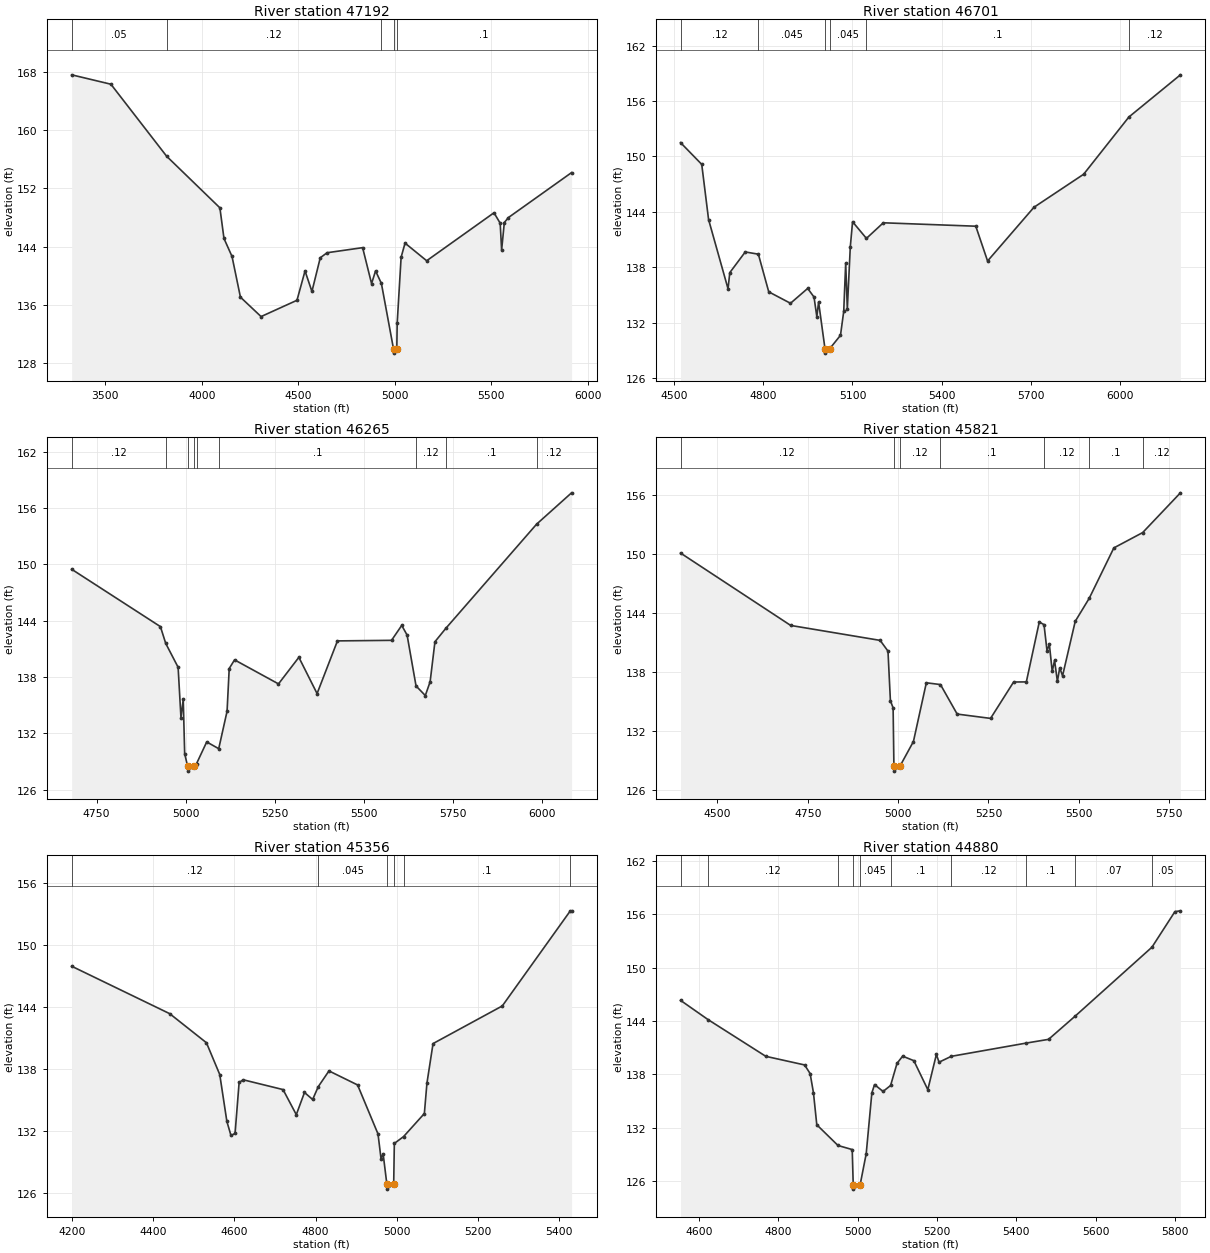
Type RM Length L Ch R = 1 ,47192   ,491,491,491
BEGIN DESCRIPTION:
Mapping XS 971fb684
END DESCRIPTION:
XS GIS Cut Line= 4
      2530559.11     13470226.98      2529695.36     13469089.79
      2529599.87     13468603.68       2529361.4      13467979.3
#Sta/Elev= 30
  3325.2   167.6  3528.6  166.31  3817.5  156.42  4093.7  149.33  4114.9  145.12
  4156.6  142.65  4200.2  137.06  4307.2  134.39  4493.4  136.63  4535.1  140.66
  4570.9  137.84  4614.1  142.47  4649.4  143.16  4833.7  143.86  4880.1  138.92
  4900.8  140.67  4931.1  138.94  4994.4  129.87  4994.9  129.37  5010.9  129.87
  5012.9  133.47  5033.3  142.54  5053.7  144.48  5165.8  142.06  5514.8  148.65
  5546.9  147.22  5554.4  143.54  5568.4  147.31  5589.9     148    5917  154.17
#Mann= 5 ,-1 , 0
  3325.2     .05       0  3817.5     .12       0  4931.1    .045       0
  4994.4    .045       0  5010.9      .1       0
Bank Sta=4994.4,5010.9
XS Rating Curve= 0 ,0
Exp/Cntr=0.3,0.1

Type RM Length L Ch R = 1 ,46701   ,436,436,436
BEGIN DESCRIPTION:
TURKEY CREEK 61.0
END DESCRIPTION:
XS GIS Cut Line= 3
      2530324.98     13469424.96        2530075.       13469025.
      2529574.98     13467924.96
#Sta/Elev= 30
  4522.2   151.5  4593.5  149.14  4616.5  143.16  4681.9  135.66  4687.8  137.41
  4739.7  139.65  4783.8  139.41  4818.7  135.33  4891.8  134.09  4949.6   135.7
  4970.9  134.76  4980.3  132.63  4986.2  134.23  5007.6  129.19  5008.1  128.69
  5024.1  129.19  5059.8  130.62  5070.7  133.22  5077.3  138.45  5082.8   133.5
  5092.7  140.17  5100.4  142.92    5147  141.12  5203.7  142.81  5514.5  142.44
  5554.1  138.67    5710  144.49    5877  148.07    6029  154.27  6202.2  158.84
#Mann= 6 ,-1 , 0
  4522.2     .12       0  4783.8    .045       0  5007.6    .045       0
  5024.1    .045       0    5147      .1       0    6029     .12       0
Bank Sta=5007.6,5024.1
XS Rating Curve= 0 ,0
Exp/Cntr=0.3,0.1

Type RM Length L Ch R = 1 ,46265   ,444,444,444
BEGIN DESCRIPTION:
TURKEY CREEK 60.0
END DESCRIPTION:
XS GIS Cut Line= 3
      2530574.98     13469074.98        2530325.       13468875.
        2529725.     13467974.99
#Sta/Elev= 30
    4680  149.46  4928.9  143.35  4943.8  141.56  4978.5  139.02  4986.5  133.66
  4992.9  135.61  4996.9  129.81  5005.3  128.46  5005.8  127.96    5022  128.46
  5030.1  128.75  5058.7  131.07  5092.4  130.35  5115.8  134.34  5121.8  138.89
  5136.8  139.81    5260  137.25  5317.1  140.08  5368.2  136.22  5425.3  141.83
    5577  141.89  5605.6  143.48  5620.6  142.45  5645.7  137.03  5671.7  136.01
  5685.2  137.48  5698.7  141.74  5729.5  143.18  5983.7  154.26  6081.8   157.6
#Mann= 9 ,-1 , 0
    4680     .12       0  4943.8    .045       0  5005.3    .045       0
    5022    .045       0  5030.1     .12       0  5092.4      .1       0
  5645.7     .12       0  5729.5      .1       0  5983.7     .12       0
Bank Sta=5005.3,5022
XS Rating Curve= 0 ,0
Exp/Cntr=0.3,0.1

Type RM Length L Ch R = 1 ,45821   ,465,465,465
BEGIN DESCRIPTION:
TURKEY CREEK 59.0
END DESCRIPTION:
XS GIS Cut Line= 3
      2530774.98     13468924.97        2530375.       13468475.
      2529774.98     13467974.98
#Sta/Elev= 30
  4398.1  150.12  4702.9  142.76  4950.4  141.24  4972.1  140.15  4978.8  135.11
  4986.3  134.38  4988.5  128.45    4989  127.95  5005.2  128.45  5042.5  130.96
  5078.2  136.93  5117.3  136.75  5163.5  133.75  5255.9  133.31  5319.7  137.01
  5354.9  137.02  5390.7  143.11  5403.8  142.84  5412.1  140.19  5418.6  140.84
  5426.5  138.09    5433   139.2  5440.8  137.07  5447.3  138.45  5455.1  137.64
  5490.2  143.18  5528.9  145.52    5597  150.64  5676.8   152.2  5781.2  156.24
#Mann= 7 ,-1 , 0
  4398.1     .12       0  4988.5    .045       0  5005.2     .12       0
  5117.3      .1       0  5403.8     .12       0  5528.9      .1       0
  5676.8     .12       0
Bank Sta=4988.5,5005.2
XS Rating Curve= 0 ,0
Exp/Cntr=0.3,0.1

Type RM Length L Ch R = 1 ,45356   ,476,476,476
BEGIN DESCRIPTION:
TURKEY CREEK 58.0
END DESCRIPTION:
XS GIS Cut Line= 3
      2531125.04       13468125.        2530325.       13468025.
      2529924.97     13467874.99
#Sta/Elev= 30
  4198.3  147.98  4440.2  143.38  4530.9  140.56  4563.7  137.48  4581.3  132.93
  4591.4  131.57  4601.5  131.77  4611.5  136.71  4621.6  136.97  4719.9  136.02
  4752.6  133.59  4772.8  135.74  4792.9  135.06  4806.9  136.31  4833.2  137.83
  4903.8  136.47  4954.2  131.72  4961.7  129.31  4966.8   129.8    4976  126.87
  4976.5  126.37  4992.9  126.87  4994.5   130.8  5017.2  131.46  5068.6   133.7
  5074.9  136.63    5090  140.48  5260.9  144.13  5428.4  153.33  5431.8  153.35
#Mann= 6 ,-1 , 0
  4198.3     .12       0  4806.9    .045       0    4976    .045       0
  4992.9    .045       0  5017.2      .1       0  5428.4     .12       0
Bank Sta=4976,4992.9
XS Rating Curve= 0 ,0
Exp/Cntr=0.3,0.1

Type RM Length L Ch R = 1 ,44880   ,471,471,471
BEGIN DESCRIPTION:
TURKEY CREEK 57.0
END DESCRIPTION:
XS GIS Cut Line= 3
      2531075.01       13467975.        2530675.       13467775.
      2530124.97     13467174.97
#Sta/Elev= 30
  4552.9  146.34  4622.1  144.18  4768.1  140.04    4866  139.07  4879.9   138.1
  4888.3  135.94  4896.7  132.34  4950.2  130.01  4986.1  129.55  4988.6   125.6
  4989.1   125.1  5006.1   125.6  5021.4  129.09  5035.6  135.92  5042.4  136.86
  5063.9  136.09  5082.9  136.76  5099.1  139.25  5113.3  140.06  5141.6  139.55
  5176.8  136.29  5198.4  140.25  5205.1  139.38    5236  140.04    5425  141.53
  5481.4  141.95  5548.7  144.57  5742.3  152.32  5800.2  156.32  5814.1  156.41
#Mann= 10 ,-1 , 0
  4552.9     .07       0  4622.1     .12       0  4950.2    .045       0
  4988.6    .045       0  5006.1    .045       0  5082.9      .1       0
    5236     .12       0    5425      .1       0  5548.7     .07       0
  5742.3     .05       0
Bank Sta=4988.6,5006.1
XS Rating Curve= 0 ,0
Exp/Cntr=0.3,0.1

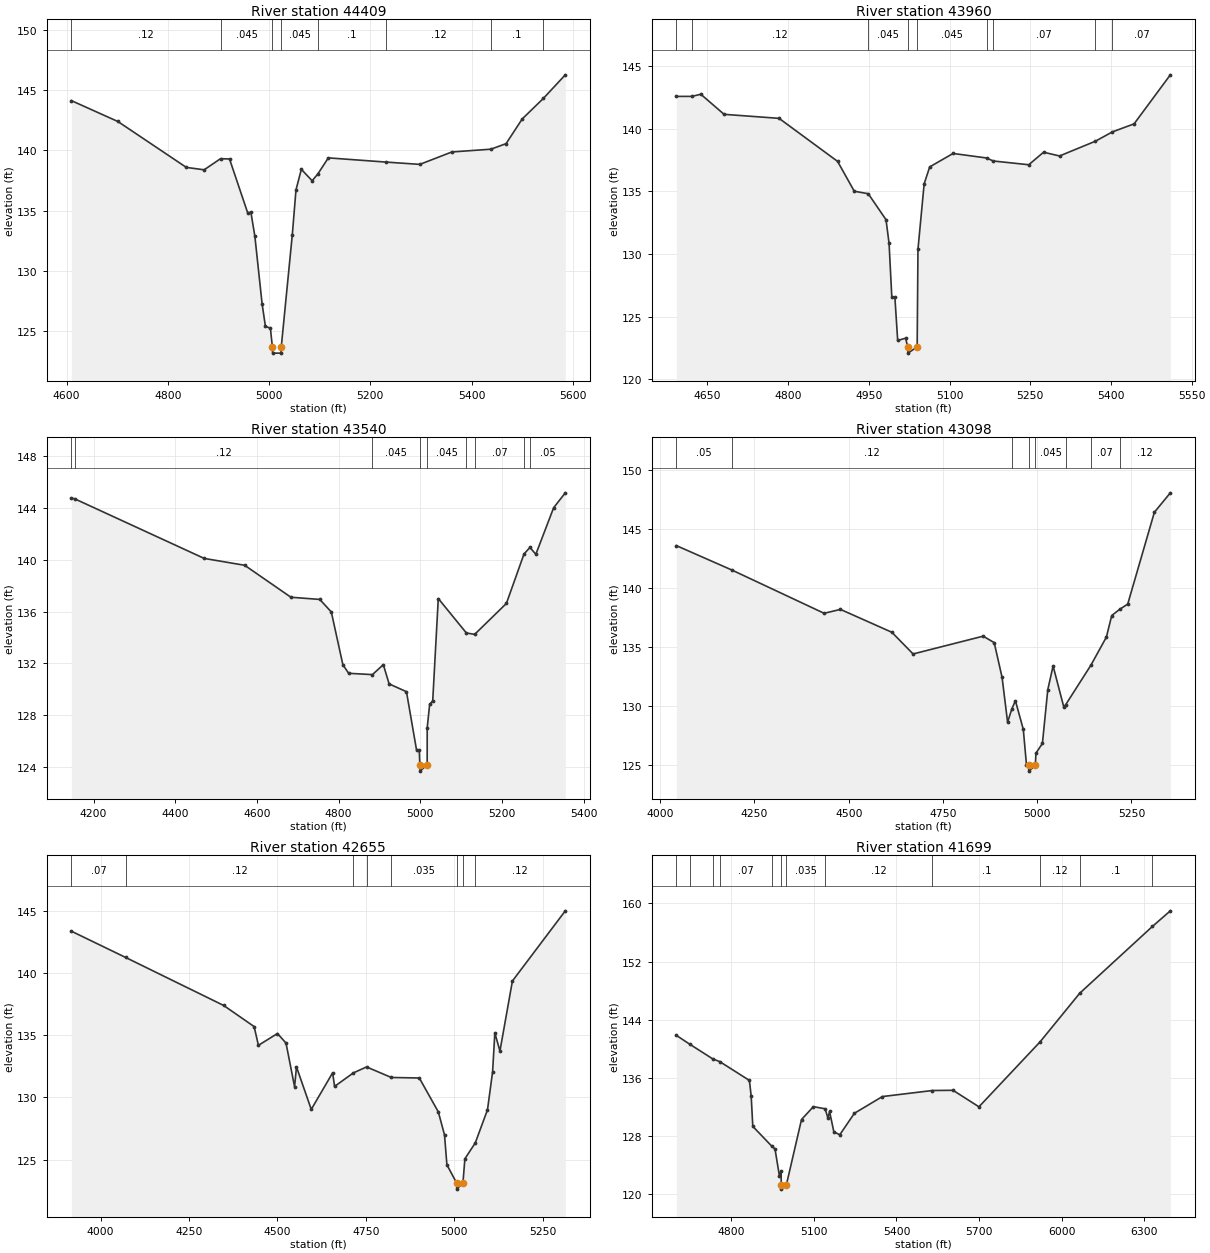
Type RM Length L Ch R = 1 ,44409   ,449,449,449
BEGIN DESCRIPTION:
TURKEY CREEK 56.0
END DESCRIPTION:
XS GIS Cut Line= 3
      2531224.99     13467674.99        2530925.       13467425.
      2530375.04     13467225.01
#Sta/Elev= 30
  4609.5  144.13  4701.3   142.4  4836.6  138.59  4871.8  138.39  4904.1  139.31
  4921.9  139.29  4957.7  134.83  4964.2  134.85    4972  132.87  4986.3  127.26
  4992.8  125.41  5002.7  125.24  5006.6  123.68  5007.1  123.18  5023.6  123.18
  5024.1  123.68  5045.9  132.98  5053.2  136.72  5063.8  138.43  5085.1  137.48
  5096.3  138.04  5117.1  139.38  5231.2  139.03  5297.9  138.84  5361.1  139.87
  5438.2   140.1  5468.2  140.56  5500.1  142.61  5541.8  144.31  5585.2  146.27
#Mann= 8 ,-1 , 0
  4609.5     .12       0  4904.1    .045       0  5006.6    .045       0
  5024.1    .045       0  5096.3      .1       0  5231.2     .12       0
  5438.2      .1       0  5541.8     .12       0
Bank Sta=5006.6,5024.1
XS Rating Curve= 0 ,0
Exp/Cntr=0.3,0.1

Type RM Length L Ch R = 1 ,43960   ,420,420,420
BEGIN DESCRIPTION:
TURKEY CREEK 55.0
END DESCRIPTION:
XS GIS Cut Line= 3
      2531375.02     13467425.04        2531175.       13467075.
      2530725.04     13466825.02
#Sta/Elev= 30
  4592.5  142.57  4620.9  142.57  4637.9  142.74  4681.1  141.14  4783.3  140.82
    4892  137.39    4923  135.01    4949  134.81    4982  132.74  4987.7  130.85
  4992.8  126.55  4998.5  126.55  5003.7  123.11  5018.5  123.29  5022.3   122.6
  5022.8   122.1  5039.9   122.6  5041.4  130.38  5052.9   135.6  5063.2  136.95
  5106.6  138.02  5168.9  137.66  5181.2  137.42  5247.3  137.12  5274.8  138.12
  5304.5  137.82  5370.8  138.99  5402.7  139.74    5443  140.38  5510.4  144.29
#Mann= 9 ,-1 , 0
  4592.5     .07       0  4620.9     .12       0    4949    .045       0
  5022.3    .045       0  5039.9    .045       0  5168.9     .12       0
  5181.2     .07       0  5370.8     .12       0  5402.7     .07       0
Bank Sta=5022.3,5039.9
XS Rating Curve= 0 ,0
Exp/Cntr=0.3,0.1

Type RM Length L Ch R = 1 ,43540   ,442,442,442
BEGIN DESCRIPTION:
TURKEY CREEK 54.0
END DESCRIPTION:
XS GIS Cut Line= 3
      2531974.97     13467324.97        2531375.       13466725.
      2531175.02     13466425.03
#Sta/Elev= 30
  4145.8  144.78  4154.4  144.71    4471  140.11    4570  139.58  4683.2  137.11
  4753.9  136.94  4782.1  135.97  4810.4  131.89  4824.6  131.23  4882.7  131.13
  4909.4   131.9  4923.6  130.41    4966  129.81  4990.7   125.3  4997.3   125.3
  4998.8  124.17  4999.3  123.67  5016.7  124.17  5016.8  127.02  5022.8  128.83
  5030.3  129.11  5043.9  137.01  5112.6  134.35  5132.9  134.24  5210.6  136.63
  5253.7  140.45  5268.2  140.96  5282.7  140.43  5326.3  144.03  5354.8  145.18
#Mann= 9 ,-1 , 0
  4145.8     .07       0  4154.4     .12       0  4882.7    .045       0
  4998.8    .045       0  5016.7    .045       0  5112.6     .12       0
  5132.9     .07       0  5253.7     .12       0  5268.2     .05       0
Bank Sta=4998.8,5016.7
XS Rating Curve= 0 ,0
Exp/Cntr=0.3,0.1

Type RM Length L Ch R = 1 ,43098   ,443,443,443
BEGIN DESCRIPTION:
TURKEY CREEK 53.0
END DESCRIPTION:
XS GIS Cut Line= 3
      2532192.64     13467145.34        2531625.       13466375.
      2531375.03     13466125.03
#Sta/Elev= 30
  4042.9  143.61  4190.1  141.54  4434.8  137.87  4478.1   138.2  4614.5  136.26
  4670.8  134.42  4856.7  135.93    4886  135.38  4906.9  132.43  4921.5  128.63
  4932.9  129.77  4942.3  130.45  4963.2  128.02  4971.6  125.02  4977.3  124.98
  4977.8  124.48  4995.2  124.98  4996.7     126  5013.9  126.83  5028.1  131.38
  5042.2   133.4  5070.5  129.93  5075.5  130.11  5142.4  133.46  5183.6  135.85
  5197.8  137.68    5219  138.21  5240.2  138.65  5310.9  146.44  5353.3  148.09
#Mann= 8 ,-1 , 0
  4042.9     .05       0  4190.1     .12       0  4932.9    .045       0
  4977.3    .045       0  4995.2    .045       0  5075.5     .12       0
  5142.4     .07       0    5219     .12       0
Bank Sta=4977.3,4995.2
XS Rating Curve= 0 ,0
Exp/Cntr=0.3,0.1

Type RM Length L Ch R = 1 ,42655   ,956,956,956
BEGIN DESCRIPTION:
TURKEY CREEK 52.0
END DESCRIPTION:
XS GIS Cut Line= 3
      2532325.01     13467075.03        2531925.       13466075.
      2531675.02     13465875.02
#Sta/Elev= 30
  3917.3  143.39  4070.5  141.28  4348.1  137.41  4434.3  135.71  4446.4   134.2
  4500.3  135.15  4524.5  134.38  4548.7  130.86  4554.1  132.46  4595.9  129.04
  4656.4  131.99  4661.8  130.89    4715  131.98  4752.3  132.46  4822.4  131.61
  4901.5  131.57  4955.3  128.84  4972.8  126.99  4979.6  124.58    5007  123.12
  5007.5  122.62    5025  123.12  5030.4  125.06  5059.8  126.34  5094.4  129.01
  5108.8  132.06  5115.2   135.2  5129.6  133.74  5164.9  139.38  5314.5  145.03
#Mann= 8 ,-1 , 0
  3917.3     .07       0  4070.5     .12       0    4715    .035       0
  4752.3     .12       0  4822.4    .035       0    5007    .035       0
    5025    .035       0  5059.8     .12       0
Bank Sta=5007,5025
XS Rating Curve= 0 ,0
Exp/Cntr=0.3,0.1

Type RM Length L Ch R = 1 ,41699   ,869,869,869
BEGIN DESCRIPTION:
TURKEY CREEK 51.0
END DESCRIPTION:
XS GIS Cut Line= 3
      2532875.01     13466575.02        2532675.       13466225.
      2531474.98     13465524.99
#Sta/Elev= 30
  4601.5  141.85  4650.2  140.63  4734.2   138.6  4758.1  138.26  4866.4  135.66
  4872.9  133.47  4878.7  129.34    4947  126.64  4959.3  126.23  4975.1  122.57
  4981.6  123.22  4981.9  121.21  4982.4  120.71    5000  121.21  5055.5  130.28
  5098.5  132.05  5141.1  131.76  5151.4  130.48  5157.2  131.39  5172.9  128.58
  5194.4  128.19  5247.3  131.14    5349  133.44  5530.2  134.27  5605.4   134.3
  5699.3  132.03  5921.6  140.98  6065.1  147.65  6328.7  156.83  6393.9  158.98
#Mann= 12 ,-1 , 0
  4601.5     .12       0  4650.2     .07       0  4734.2     .12       0
  4758.1     .07       0    4947    .035       0  4981.9    .035       0
    5000    .035       0  5141.1     .12       0  5530.2      .1       0
  5921.6     .12       0  6065.1      .1       0  6328.7     .12       0
Bank Sta=4981.9,5000
XS Rating Curve= 0 ,0
Exp/Cntr=0.3,0.1

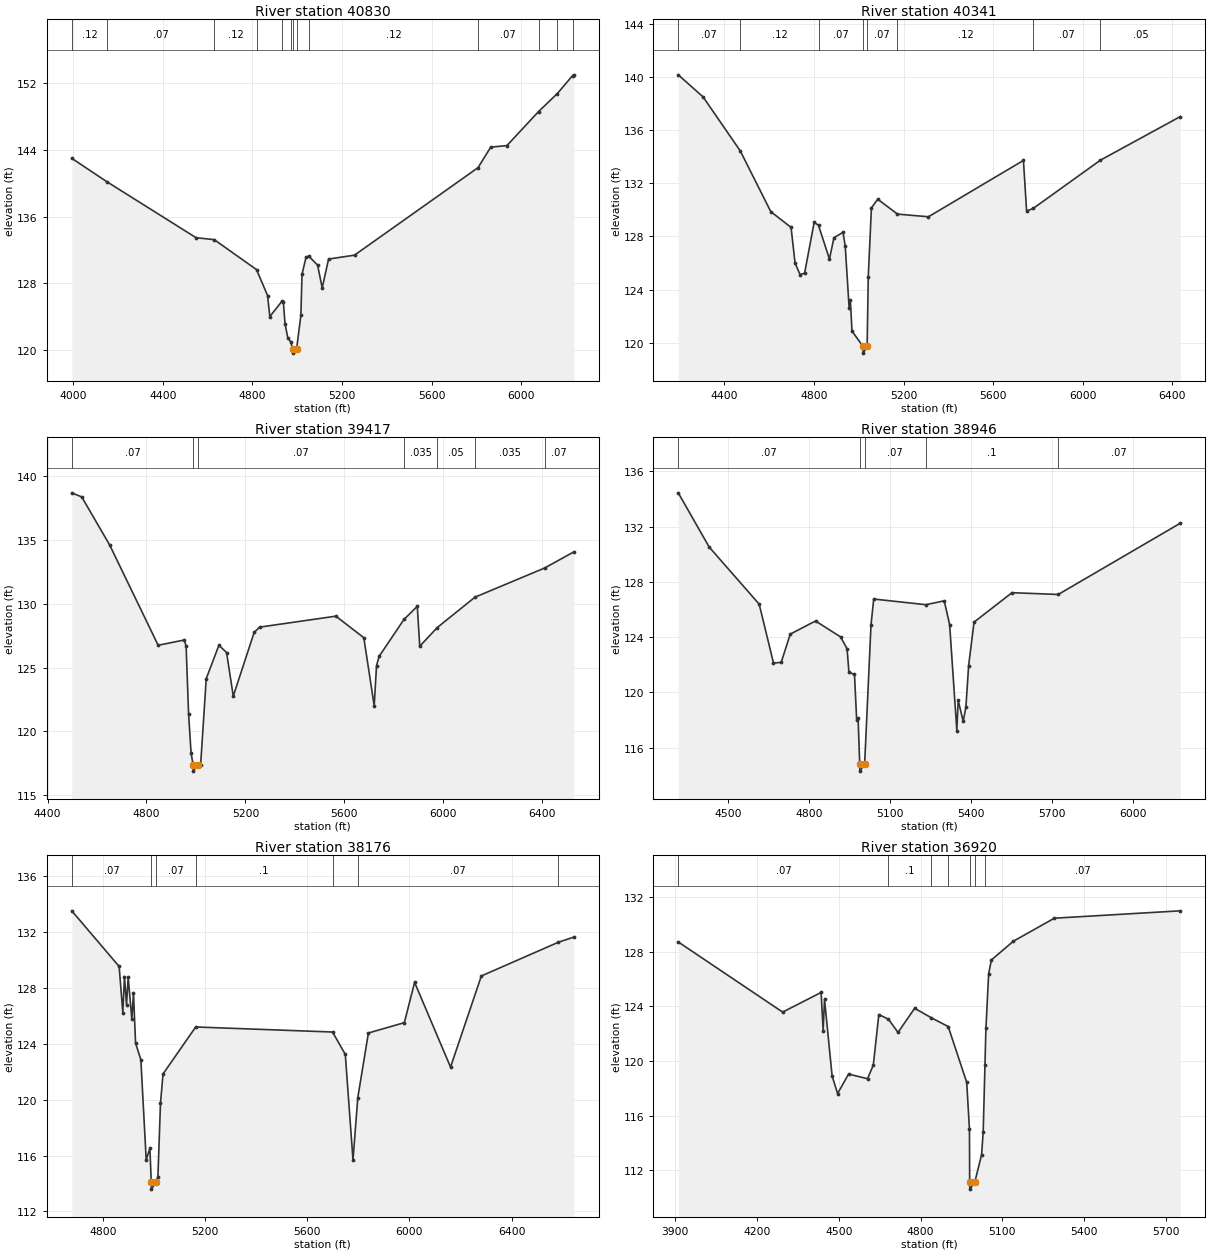
Type RM Length L Ch R = 1 ,40830   ,489,489,489
BEGIN DESCRIPTION:
TURKEY CREEK 50.0
END DESCRIPTION:
XS GIS Cut Line= 3
        2533075.     13466574.96        2532975.       13465575.
      2531774.98     13465274.99
#Sta/Elev= 30
  3993.2  143.01  4150.5  140.19  4548.4  133.48  4629.4  133.25  4818.3  129.65
  4867.5  126.54  4877.5  124.02  4931.8  125.86  4937.8  125.81  4945.4  123.18
  4957.9  121.44  4971.2  120.98    4979  120.13  4979.5  119.63  4997.1  120.13
  5016.2  124.16  5021.3  129.09  5039.4  131.16  5051.8  131.26  5090.9  130.19
  5111.5  127.45  5139.9  130.92  5255.8  131.39  5807.3  141.89    5864  144.35
  5936.2  144.54  6077.5  148.62  6161.3  150.78  6229.5  152.94  6235.1  153.03
#Mann= 13 ,-1 , 0
  3993.2     .12       0  4150.5     .07       0  4629.4     .12       0
  4818.3     .07       0  4931.8    .035       0  4971.2     .07       0
    4979     .05       0  4997.1     .07       0  5051.8     .12       0
  5807.3     .07       0  6077.5     .12       0  6161.3      .1       0
  6229.5     .12       0
Bank Sta=4979,4997.1
XS Rating Curve= 0 ,0
Exp/Cntr=0.3,0.1

Type RM Length L Ch R = 1 ,40341   ,924,924,924
BEGIN DESCRIPTION:
TURKEY CREEK 49.0
END DESCRIPTION:
XS GIS Cut Line= 3
        2533525.     13466275.04        2533425.       13465475.
      2532409.57     13464459.57
#Sta/Elev= 30
  4193.5  140.16  4304.4   138.5  4470.4  134.44  4606.7  129.87  4697.4  128.68
  4715.1  126.01  4737.7  125.12  4757.9  125.24  4800.7  129.07    4820  128.83
  4868.8   126.3  4888.9   127.9  4929.2  128.31  4939.3  127.28  4956.9  122.58
    4962  123.23  4969.5  120.88    5019  119.72  5019.5  119.22  5037.1  119.72
  5042.2  124.97  5056.3  130.15  5084.6   130.8  5172.7  129.68  5310.9  129.48
  5735.2  133.72  5749.3  129.91  5779.1  130.11  6079.1  133.74  6435.8  137.02
#Mann= 8 ,-1 , 0
  4193.5     .07       0  4470.4     .12       0    4820     .07       0
    5019     .05       0  5037.1     .07       0  5172.7     .12       0
  5779.1     .07       0  6079.1     .05       0
Bank Sta=5019,5037.1
XS Rating Curve= 0 ,0
Exp/Cntr=0.3,0.1

Type RM Length L Ch R = 1 ,39417   ,471,471,471
BEGIN DESCRIPTION:
TURKEY CREEK 48.0
END DESCRIPTION:
XS GIS Cut Line= 3
        2534175.     13466324.96        2534125.       13465825.
      2533773.07     13464338.75
#Sta/Elev= 30
    4498   138.7  4538.2  138.38  4651.2  134.61  4847.2  126.75  4952.7  127.16
  4960.3  126.69  4970.3  121.36  4980.4  118.27  4988.8  117.38  4989.3  116.88
    5007  117.38    5019  117.38  5041.6  124.13  5092.9  126.75  5123.8  126.18
  5150.9  122.76  5235.4  127.76  5257.4  128.17  5565.7  129.03  5678.7  127.34
  5720.7  122.01  5730.1  125.15  5740.4  125.87  5840.9  128.77  5894.9   129.8
  5904.8  126.67  5975.8  128.14  6128.3  130.52  6410.2  132.81  6527.8  134.07
#Mann= 7 ,-1 , 0
    4498     .07       0  4988.8     .05       0    5007     .07       0
  5840.9    .035       0  5975.8     .05       0  6128.3    .035       0
  6410.2     .07       0
Bank Sta=4988.8,5007
XS Rating Curve= 0 ,0
Exp/Cntr=0.3,0.1

Type RM Length L Ch R = 1 ,38946   ,770,770,770
BEGIN DESCRIPTION:
TURKEY CREEK 47.0
END DESCRIPTION:
XS GIS Cut Line= 3
       2534354.1     13466285.98        2534525.       13465625.
       2534440.9     13464454.33
#Sta/Elev= 30
  4316.8  134.44  4431.4  130.51  4616.1  126.38    4669  122.12  4697.4  122.16
    4731  124.21  4824.4  125.16  4916.9  124.01  4941.1  123.15  4947.9  121.45
  4968.5  121.29  4976.6  117.98  4981.8  118.14  4987.8  114.79  4988.3  114.29
    5006  114.79  5029.6  124.89  5039.6  126.75  5232.3  126.34  5300.3  126.62
  5320.3   124.9  5346.9  117.23  5351.9  119.42  5370.5  117.89  5380.5  118.94
  5390.5  121.93  5410.6  125.08  5550.9  127.21  5721.8  127.08  6173.2  132.24
#Mann= 5 ,-1 , 0
  4316.8     .07       0  4987.8     .05       0    5006     .07       0
  5232.3      .1       0  5721.8     .07       0
Bank Sta=4987.8,5006
XS Rating Curve= 0 ,0
Exp/Cntr=0.3,0.1

Type RM Length L Ch R = 1 ,38176   ,1256,1256,1256
BEGIN DESCRIPTION:
TURKEY CREEK 46.0
END DESCRIPTION:
XS GIS Cut Line= 3
      2534525.01     13466474.99      2534722.53     13466219.55
      2534896.63      13464584.6
#Sta/Elev= 30
  4677.1  133.51  4862.7  129.53  4877.2  126.22  4883.5  128.81  4891.7  126.79
    4898  128.77  4912.5  125.75  4918.9  127.64    4927  124.05  4947.8  122.86
  4968.7  115.69  4983.2  116.52  4988.5   114.1    4989   113.6  5006.8   114.1
  5014.6  114.47  5024.7  119.75  5034.7  121.84  5162.6   125.2  5698.8  124.84
  5748.8  123.24  5778.9  115.68  5797.7  120.14  5839.3  124.77  5980.1  125.51
  6020.3  128.39  6161.1  122.33  6281.8  128.85  6583.2  131.26  6644.2  131.63
#Mann= 7 ,-1 , 0
  4677.1     .07       0  4988.5     .05       0  5006.8     .07       0
  5162.6      .1       0  5698.8     .12       0  5797.7     .07       0
  6583.2     .05       0
Bank Sta=4988.5,5006.8
XS Rating Curve= 0 ,0
Exp/Cntr=0.3,0.1

Type RM Length L Ch R = 1 ,36920   ,464,464,464
BEGIN DESCRIPTION:
TURKEY CREEK 45.0
END DESCRIPTION:
XS GIS Cut Line= 3
      2535104.96      13466555.1      2535240.14     13465453.53
        2535175.     13464724.97
#Sta/Elev= 30
  3911.5  128.72  4294.4  123.58  4435.5  125.02    4443  122.23    4448  124.51
  4475.8  118.91  4495.9  117.61  4536.2  119.04  4605.7   118.7  4626.9  119.69
  4647.1   123.4  4682.4  123.06  4717.6  122.09  4778.5  123.86  4838.4  123.18
  4901.6  122.52  4969.5  118.43  4979.5  114.99  4980.3  111.11  4980.8  110.61
  4998.9  111.11  5023.9  113.12  5029.9  114.79  5036.4  119.72  5039.9  122.38
    5050   126.4    5060   127.4  5140.3  128.77  5290.9  130.46  5752.8     131
#Mann= 7 ,-1 , 0
  3911.5     .07       0  4682.4      .1       0  4838.4     .07       0
  4901.6    .035       0  4980.3    .035       0  4998.9    .035       0
  5036.4     .07       0
Bank Sta=4980.3,4998.9
XS Rating Curve= 0 ,0
Exp/Cntr=0.3,0.1