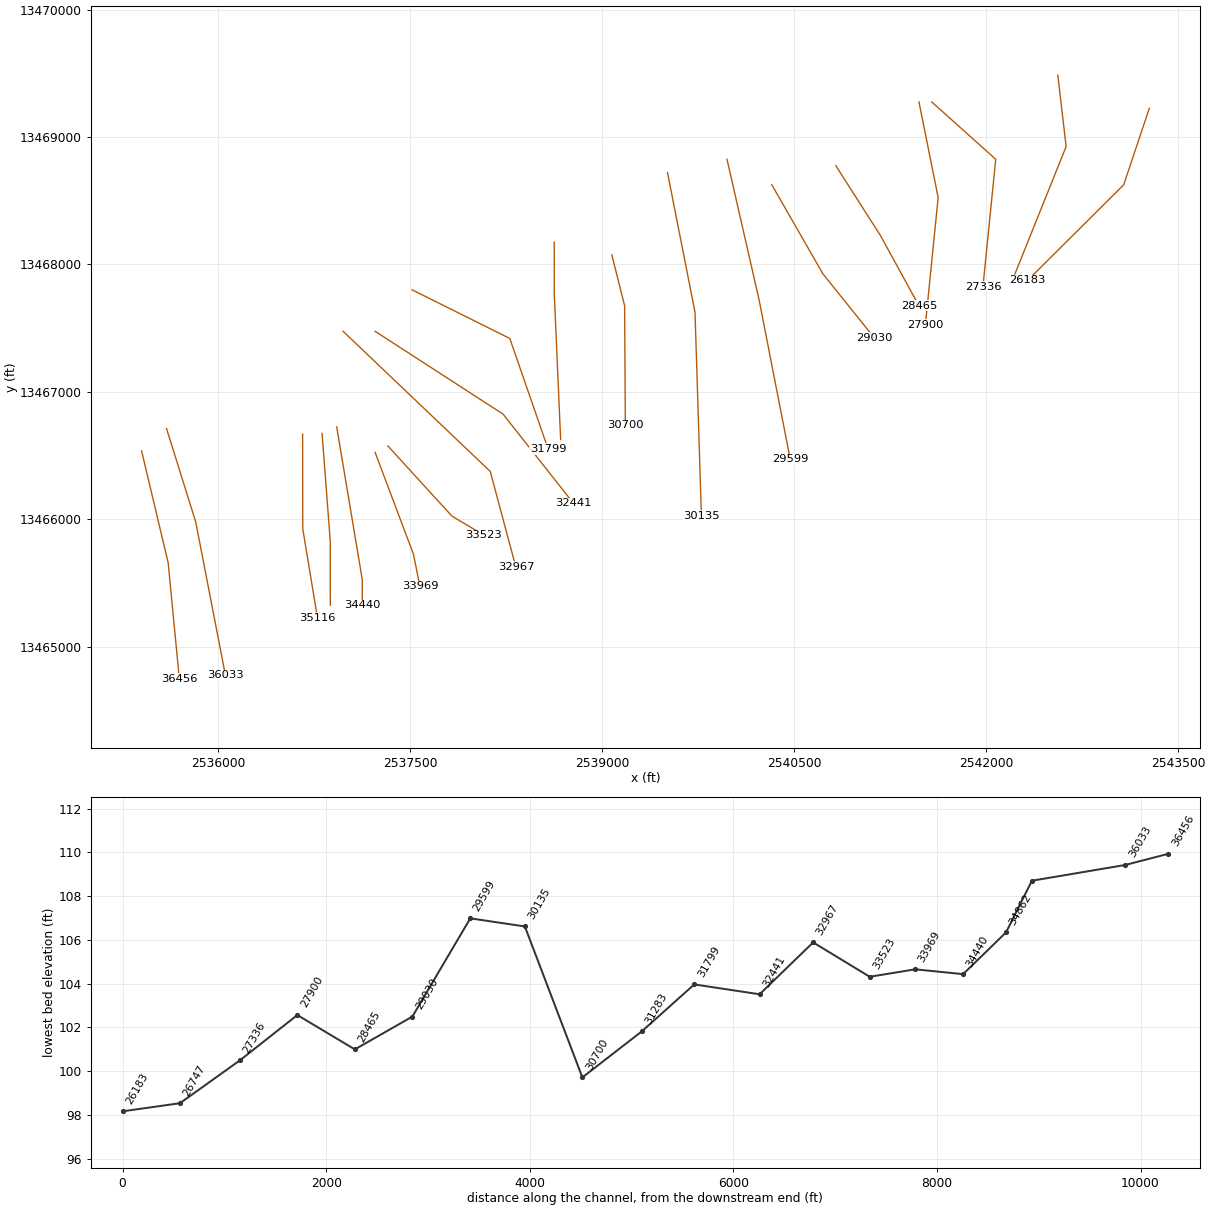
HEC-RAS study TURKEY CREEK.prj: TURKEY CREEK Base Level Engineering

--- TURKEY CREEK.g01 (geometry) --- (continued)

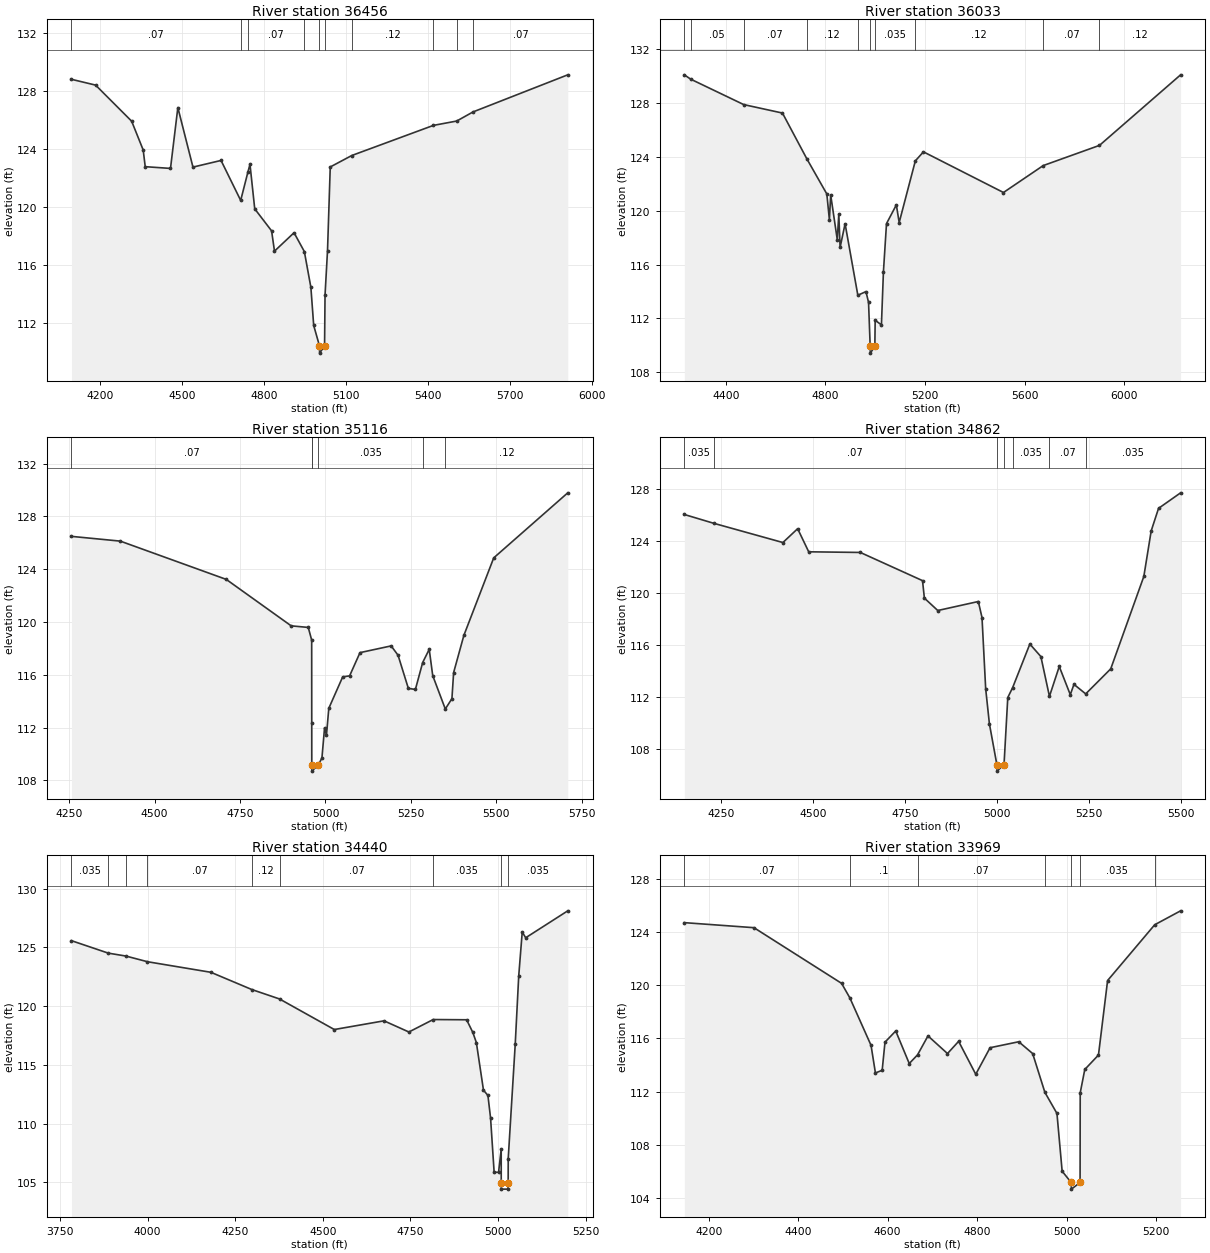
Type RM Length L Ch R = 1 ,36456   ,423,423,423
BEGIN DESCRIPTION:
TURKEY CREEK 44.0
END DESCRIPTION:
XS GIS Cut Line= 3
      2535400.11     13466537.69      2535608.05     13465658.45
      2535695.22     13464749.72
#Sta/Elev= 30
  4096.5  128.83  4184.8  128.43  4316.7  125.94    4359  123.95  4366.4   122.8
  4458.9  122.68  4485.8  126.88  4541.1  122.77  4643.9  123.23  4715.8  120.47
  4742.5  122.45  4749.8  122.96  4767.2  119.89  4828.9  118.37  4839.5  116.97
  4911.1  118.24  4948.8  116.94  4972.7  114.47    4983  111.84  5004.2  110.43
  5004.7  109.93  5022.8  110.43  5024.5  113.93  5033.6  117.01  5043.6  122.78
  5122.3  123.57  5421.2  125.65  5506.4  125.95  5566.3  126.58  5912.9  129.14
#Mann= 10 ,-1 , 0
  4096.5     .07       0  4715.8      .1       0  4742.5     .07       0
  4948.8    .035       0  5004.2    .035       0  5022.8    .035       0
  5122.3     .12       0  5421.2     .07       0  5506.4     .12       0
  5566.3     .07       0
Bank Sta=5004.2,5022.8
XS Rating Curve= 0 ,0
Exp/Cntr=0.3,0.1

Type RM Length L Ch R = 1 ,36033   ,917,917,917
BEGIN DESCRIPTION:
TURKEY CREEK 43.0
END DESCRIPTION:
XS GIS Cut Line= 3
      2535595.41     13466711.34      2535823.23     13465979.26
      2536055.49     13464775.57
#Sta/Elev= 30
  4233.3  130.09  4258.7  129.77  4471.8  127.88  4627.4  127.25  4725.3  123.85
  4805.5  121.24  4815.8  119.33    4821  121.17  4847.4  117.85  4853.6  119.74
  4858.8  117.27  4878.8  119.03    4930  113.72  4962.6  113.99    4973  113.19
  4979.6  109.92  4980.1  109.42  4998.3  109.92  4999.6  111.86  5024.7  111.52
  5032.8  115.48  5045.1  119.04  5084.6  120.43    5096  119.12  5160.9   123.7
  5193.4  124.37  5514.7  121.35  5674.3  123.35  5900.2  124.85  6225.9  130.09
#Mann= 10 ,-1 , 0
  4233.3     .07       0  4258.7     .05       0  4471.8     .07       0
  4725.3     .12       0    4930    .035       0  4979.6    .035       0
  4998.3    .035       0  5160.9     .12       0  5674.3     .07       0
  5900.2     .12       0
Bank Sta=4979.6,4998.3
XS Rating Curve= 0 ,0
Exp/Cntr=0.3,0.1

Type RM Length L Ch R = 1 ,35116   ,254,254,254
BEGIN DESCRIPTION:
TURKEY CREEK 42.0
END DESCRIPTION:
XS GIS Cut Line= 3
      2536658.79     13466667.92      2536659.84     13465924.62
      2536774.99     13465225.03
#Sta/Elev= 30
  4256.7  126.49  4399.6  126.13  4709.6  123.23  4899.6  119.71  4949.6  119.59
  4959.6  118.63  4959.8  112.34  4959.9   109.2  4960.4   108.7  4979.4   109.2
  4989.6  109.69  4997.3  111.99  5002.8  111.41  5009.7  113.46  5050.3  115.84
  5070.6  115.92    5101  117.68  5192.2  118.19  5212.4  117.48  5242.5  114.97
  5263.1  114.89  5284.4  116.93  5303.6  117.93  5313.8  115.94  5350.6  113.41
    5370  114.19    5375  116.17    5405  118.99  5492.3  124.86    5709  129.79
#Mann= 6 ,-1 , 0
  4256.7     .07       0  4959.8    .035       0  4959.9    .035       0
  4979.4    .035       0  5284.4      .1       0  5350.6     .12       0
Bank Sta=4959.9,4979.4
XS Rating Curve= 0 ,0
Exp/Cntr=0.3,0.1

Type RM Length L Ch R = 1 ,34862   ,422,422,422
BEGIN DESCRIPTION:
TURKEY CREEK 41.0
END DESCRIPTION:
XS GIS Cut Line= 3
      2536810.69      13466672.3        2536875.       13465825.
        2536875.     13465325.04
#Sta/Elev= 30
  4150.3  126.01  4229.7  125.34  4418.4  123.86  4458.5  124.92  4488.6  123.15
    4629   123.1  4798.1  120.94  4803.2   119.6  4839.6  118.65  4949.9  119.34
  4959.9  118.11  4969.9  112.65    4980  109.97  5000.3  106.84  5000.8  106.34
  5019.8  106.84    5030  111.98  5043.2  112.74    5090  116.08    5120  115.12
  5143.3  112.07    5170  114.36    5200   112.2    5210  112.99  5241.9  112.26
    5310  114.18    5400  121.26    5420  124.75    5440  126.48    5500  127.67
#Mann= 7 ,-1 , 0
  4150.3    .035       0  4229.7     .07       0  5000.3     .05       0
  5019.8     .07       0  5043.2    .035       0  5143.3     .07       0
  5241.9    .035       0
Bank Sta=5000.3,5019.8
XS Rating Curve= 0 ,0
Exp/Cntr=0.3,0.1

Type RM Length L Ch R = 1 ,34440   ,471,471,471
BEGIN DESCRIPTION:
TURKEY CREEK 40.0
END DESCRIPTION:
XS GIS Cut Line= 3
        2536925.     13466725.01        2537125.       13465525.
        2537125.     13465324.96
#Sta/Elev= 30
  3782.6  125.57  3887.7  124.51  3938.3  124.26  3999.4  123.78  4180.5  122.88
  4297.6  121.41  4376.5  120.61  4532.8  118.01  4674.7  118.75  4745.7   117.8
  4815.1  118.86  4910.5  118.84  4928.2  117.76  4938.3   116.9  4958.6  112.85
  4971.3   112.4  4978.9  110.46    4989  105.87  5001.7  105.86  5009.2  107.83
  5009.3  104.93  5009.8  104.43  5028.6  104.43  5029.1  104.93  5029.2  107.02
  5049.2  116.74  5059.2  122.56  5069.2   126.3  5079.2  125.82  5199.2  128.11
#Mann= 9 ,-1 , 0
  3782.6    .035       0  3887.7     .07       0  3938.3    .035       0
  3999.4     .07       0  4297.6     .12       0  4376.5     .07       0
  4815.1    .035       0  5009.3    .035       0  5029.1    .035       0
Bank Sta=5009.3,5029.1
XS Rating Curve= 0 ,0
Exp/Cntr=0.3,0.1

Type RM Length L Ch R = 1 ,33969   ,446,446,446
BEGIN DESCRIPTION:
TURKEY CREEK 39.0
END DESCRIPTION:
XS GIS Cut Line= 3
        2537225.       13466525.        2537525.       13465725.
      2537575.01     13465474.95
#Sta/Elev= 30
  4145.6  124.72  4301.3  124.34  4497.1  120.15  4515.7  119.05    4563  115.48
  4572.8   113.4  4587.9   113.6  4594.2  115.72  4618.2  116.56  4648.4  114.11
  4666.9  114.76  4690.3  116.19  4733.9  114.86  4758.8  115.78  4797.1   113.3
  4829.1   115.3  4893.2  115.75  4924.3  114.86  4951.6  111.94  4978.6  110.35
  4990.2     106  5010.4  105.15  5010.9  104.65  5030.3  105.15  5030.6   111.9
  5040.8  113.66  5071.4  114.75  5091.8  120.36  5197.1  124.56    5255  125.61
#Mann= 7 ,-1 , 0
  4145.6     .07       0  4515.7      .1       0  4666.9     .07       0
  4951.6    .035       0  5010.4    .035       0  5030.3    .035       0
  5197.1     .12       0
Bank Sta=5010.4,5030.3
XS Rating Curve= 0 ,0
Exp/Cntr=0.3,0.1

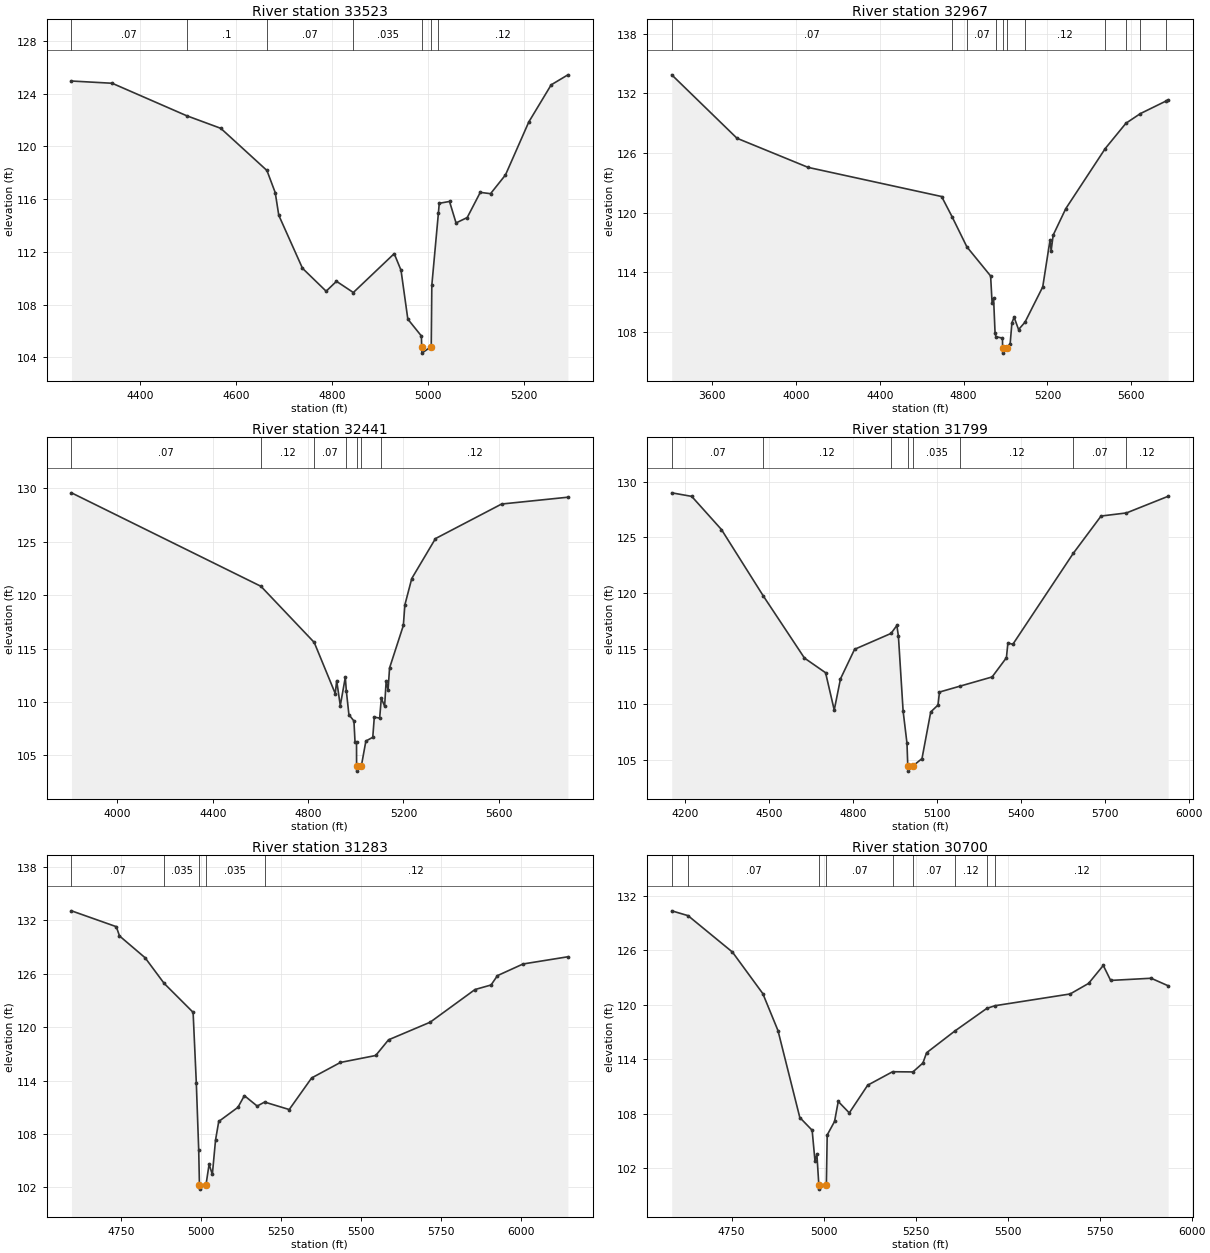
Type RM Length L Ch R = 1 ,33523   ,556,556,556
BEGIN DESCRIPTION:
TURKEY CREEK 38.0
END DESCRIPTION:
XS GIS Cut Line= 3
        2537325.       13466575.        2537825.       13466025.
      2538074.96     13465875.02
#Sta/Elev= 30
  4256.2  124.96    4341  124.79    4496  122.33  4567.4  121.37  4663.6  118.17
  4680.9  116.49  4688.3  114.77  4737.7  110.75    4787  109.01  4808.6  109.76
  4843.7  108.91  4928.9  111.86  4943.1   110.6  4957.3  106.89  4985.6  105.61
  4986.1  104.81  4986.6  104.31  5006.1  104.81  5007.3  109.46    5021  114.93
  5022.8  115.68  5044.2  115.82  5057.8  114.19  5081.1   114.6  5108.3  116.51
  5129.7  116.41  5160.8  117.83  5209.4  121.85  5256.1  124.67    5291  125.43
#Mann= 7 ,-1 , 0
  4256.2     .07       0    4496      .1       0  4663.6     .07       0
  4843.7    .035       0  4986.1    .035       0  5006.1    .035       0
    5021     .12       0
Bank Sta=4986.1,5006.1
XS Rating Curve= 0 ,0
Exp/Cntr=0.3,0.1

Type RM Length L Ch R = 1 ,32967   ,526,526,526
BEGIN DESCRIPTION:
TURKEY CREEK 37.0
END DESCRIPTION:
XS GIS Cut Line= 3
        2536975.       13467475.        2538125.       13466375.
        2538325.     13465624.99
#Sta/Elev= 30
  3408.2  133.87  3719.4  127.49  4058.8  124.56  4695.3  121.63  4745.1   119.6
  4815.7  116.57    4929  113.64  4935.9  110.96  4943.1  111.41  4950.1  107.93
  4954.3  107.53  4985.6  107.39  4986.1  106.38  4986.6  105.88  5006.2  106.38
  5022.2  106.83  5030.6  108.94    5041  109.49  5062.3  108.25  5092.8  108.99
  5177.5  112.54  5212.4  117.27  5217.6  116.17  5227.3  117.75  5287.4  120.41
  5475.8  126.46  5574.3     129  5643.2  129.97    5767  131.25  5775.8  131.35
#Mann= 11 ,-1 , 0
  3408.2     .07       0  4745.1     .12       0  4815.7     .07       0
  4954.3    .035       0  4986.1    .035       0  5006.2    .035       0
  5092.8     .12       0  5475.8    .035       0  5574.3     .12       0
  5643.2    .035       0    5767     .12       0
Bank Sta=4986.1,5006.2
XS Rating Curve= 0 ,0
Exp/Cntr=0.3,0.1

Type RM Length L Ch R = 1 ,32441   ,642,642,642
BEGIN DESCRIPTION:
TURKEY CREEK 36.0
END DESCRIPTION:
XS GIS Cut Line= 3
      2537224.98     13467475.01        2538225.       13466825.
      2538774.98     13466125.03
#Sta/Elev= 30
  3807.4  129.59  4602.3  120.83  4825.9  115.57  4914.1  110.78  4920.1  111.99
  4935.2  109.65  4956.3   112.3  4960.5  111.05  4971.4   108.8  4992.5  108.21
  4997.1  106.21  5003.3  106.21  5003.6  104.01  5004.1  103.51  5023.7  104.01
  5042.6  106.33  5071.5  106.68  5077.9  108.57  5100.4  108.48  5107.3  110.33
  5121.2   109.6  5127.6  111.94  5135.7  111.13    5142  113.18  5199.8  117.16
  5206.2  119.09  5235.1  121.56  5334.5   125.3    5612  128.54  5890.3  129.18
#Mann= 7 ,-1 , 0
  3807.4     .07       0  4602.3     .12       0  4825.9     .07       0
  4960.5    .035       0  5003.6    .035       0  5023.7    .035       0
  5107.3     .12       0
Bank Sta=5003.6,5023.7
XS Rating Curve= 0 ,0
Exp/Cntr=0.3,0.1

Type RM Length L Ch R = 1 ,31799   ,516,516,516
BEGIN DESCRIPTION:
Mapping XS 46ca1858
END DESCRIPTION:
XS GIS Cut Line= 3
      2537513.82     13467800.72      2538277.71     13467418.78
      2538577.18     13466550.74
#Sta/Elev= 30
  4152.7  129.02    4224   128.7  4330.3  125.71  4478.9  119.76  4626.5  114.14
  4701.9  112.82  4732.8  109.46  4755.1  112.27  4805.4  114.93  4935.6  116.36
  4956.4  117.08  4961.9  116.12  4978.7  109.37  4992.5  106.47  4995.3  104.46
  4995.8  103.96  5015.4  104.46  5046.1  105.09  5077.3  109.29  5103.2  109.91
  5108.5  111.08  5182.9  111.62  5296.4  112.44  5347.5  114.17  5352.8   115.5
  5370.4  115.38  5585.8  123.56  5685.4  126.93  5776.1  127.21    5925  128.71
#Mann= 8 ,-1 , 0
  4152.7     .07       0  4478.9     .12       0  4935.6    .035       0
  4995.3    .035       0  5015.4    .035       0  5182.9     .12       0
  5585.8     .07       0  5776.1     .12       0
Bank Sta=4995.3,5015.4
XS Rating Curve= 0 ,0
Exp/Cntr=0.3,0.1

Type RM Length L Ch R = 1 ,31283   ,583,583,583
BEGIN DESCRIPTION:
TURKEY CREEK 35.0
END DESCRIPTION:
XS GIS Cut Line= 3
        2538625.     13468175.02        2538625.       13467775.
        2538675.     13466625.01
#Sta/Elev= 30
  4595.6  133.07  4735.6  131.29  4745.6  130.25  4825.6   127.8  4885.1  124.92
  4975.6  121.67  4985.6  113.76  4993.1   106.2  4995.4  102.31  4995.9  101.81
  5015.9  102.31  5025.6   104.6  5035.7  103.46  5045.7  107.33  5055.7  109.41
  5115.7     111  5135.8  112.31  5175.8  111.14    5199  111.59  5275.9  110.75
    5346   114.3    5436  116.04  5546.1  116.82  5586.2  118.58  5716.3  120.56
  5856.4  124.23  5906.5  124.74  5926.5  125.79  6006.6   127.1  6146.7  127.91
#Mann= 5 ,-1 , 0
  4595.6     .07       0  4885.1    .035       0  4995.4    .035       0
  5015.9    .035       0    5199     .12       0
Bank Sta=4995.4,5015.9
XS Rating Curve= 0 ,0
Exp/Cntr=0.3,0.1

Type RM Length L Ch R = 1 ,30700   ,565,565,565
BEGIN DESCRIPTION:
TURKEY CREEK 34.0
END DESCRIPTION:
XS GIS Cut Line= 3
        2539075.       13468075.        2539175.       13467675.
      2539180.48     13466738.73
#Sta/Elev= 30
  4587.6  130.34  4631.8  129.81  4752.5   125.8    4835  121.23  4876.2  117.16
  4935.5  107.59    4969  106.19  4976.7  102.82  4981.9  103.54  4987.1  100.21
  4987.6   99.71  5007.6  100.21  5009.9  105.67  5029.9  107.16  5039.9  109.36
  5069.9   108.1  5119.9  111.15  5187.5  112.63  5242.8  112.61  5269.9  113.59
  5279.9  114.72  5356.6  117.11  5443.8  119.61  5466.2   119.9  5669.9  121.19
  5719.9  122.35  5759.9  124.33  5779.9  122.68  5889.9  122.92  5936.2  122.09
#Mann= 9 ,-1 , 0
  4587.6     .05       0  4631.8     .07       0  4987.1     .05       0
  5007.6     .07       0  5187.5     .12       0  5242.8     .07       0
  5356.6     .12       0  5443.8     .07       0  5466.2     .12       0
Bank Sta=4987.1,5007.6
XS Rating Curve= 0 ,0
Exp/Cntr=0.3,0.1

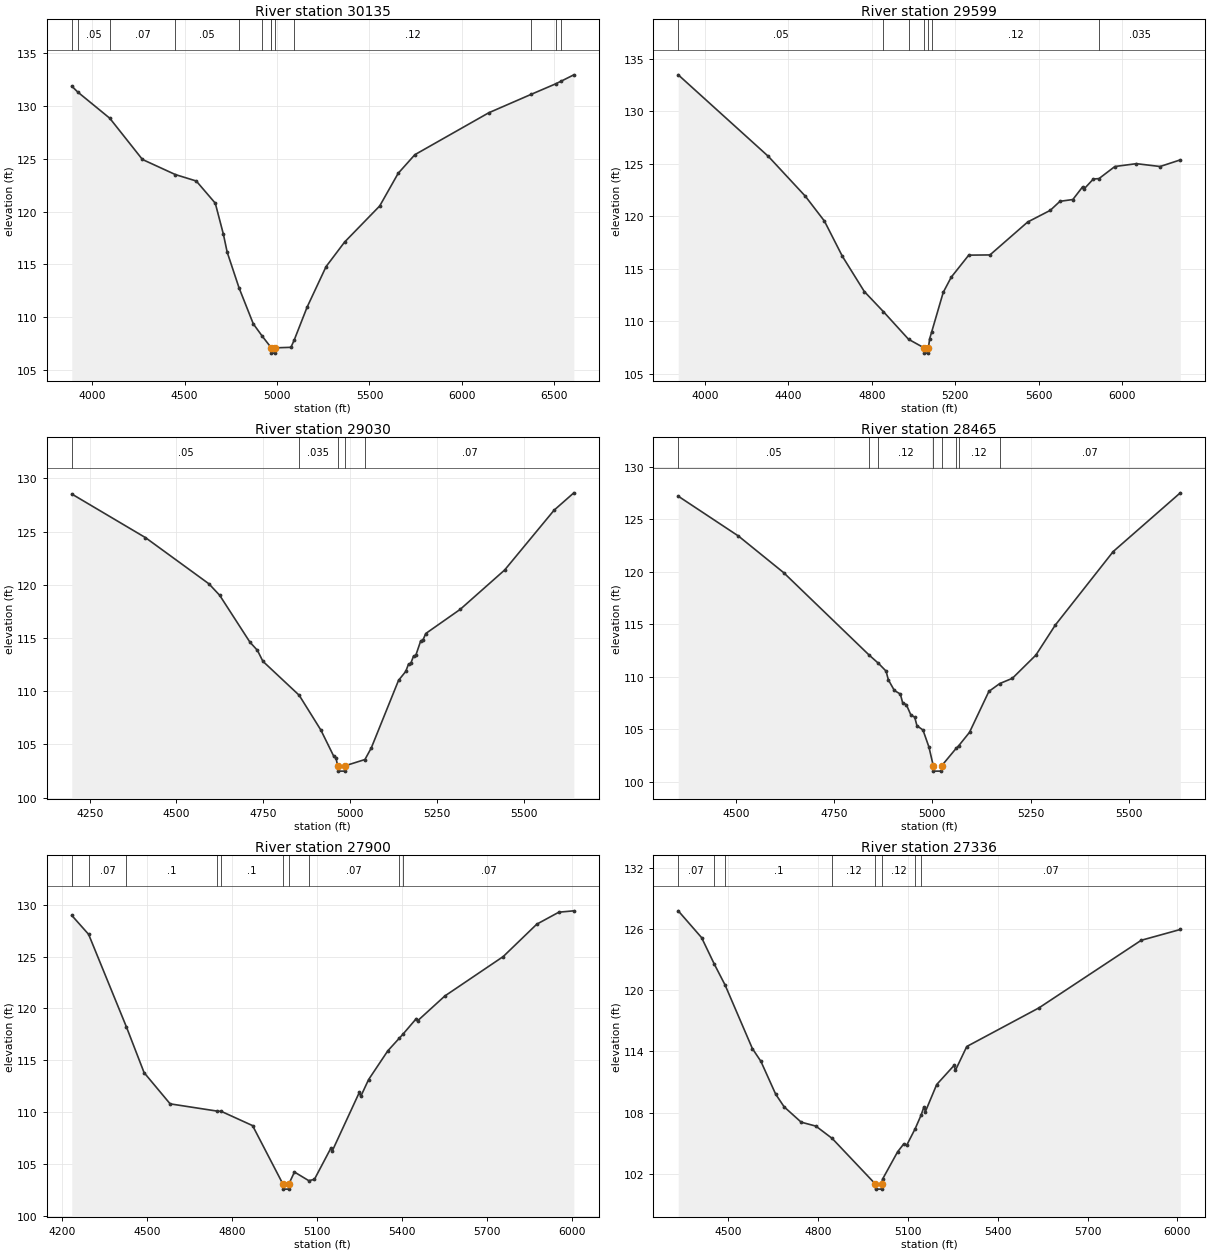
Type RM Length L Ch R = 1 ,30135   ,536,536,536
BEGIN DESCRIPTION:
TURKEY CREEK 33.0
END DESCRIPTION:
XS GIS Cut Line= 3
      2539510.04     13468720.11        2539725.       13467625.
        2539775.     13466024.99
#Sta/Elev= 30
  3889.1  131.88  3921.5  131.32  4094.8  128.84  4271.4  124.94  4449.7  123.51
  4562.8   122.9  4665.7   120.8  4709.6  117.86    4730  116.17  4794.4  112.78
  4871.4  109.38  4920.8  108.19  4964.9   107.2  4969.1  107.11  4969.6  106.61
  4989.2  106.61  4989.7  107.11  5075.1  107.16    5093  107.86  5162.7  110.97
  5265.2   114.8  5365.3  117.12  5555.4  120.54  5655.4  123.63  5745.5  125.39
  6145.7  129.36  6374.6   131.1  6506.7  132.09  6538.3  132.36  6605.9  132.95
#Mann= 13 ,-1 , 0
  3889.1     .07       0  3921.5     .05       0  4094.8     .07       0
  4449.7     .05       0  4794.4     .07       0  4920.8     .12       0
  4964.9     .07       0  4969.1     .05       0  4989.7     .07       0
    5093     .12       0  6374.6    .035       0  6506.7     .07       0
  6538.3    .035       0
Bank Sta=4969.1,4989.7
XS Rating Curve= 0 ,0
Exp/Cntr=0.3,0.1

Type RM Length L Ch R = 1 ,29599   ,569,569,569
BEGIN DESCRIPTION:
TURKEY CREEK 32.0
END DESCRIPTION:
XS GIS Cut Line= 3
      2539974.99     13468825.04        2540225.       13467725.
      2540469.38     13466469.15
#Sta/Elev= 30
  3871.9  133.45  4304.2  125.69  4481.6   121.9  4572.9  119.54    4659  116.19
  4764.1  112.84    4856  110.92  4976.2   108.3  5050.7  107.48  5051.2  106.98
    5071  106.98  5071.5  107.48  5077.5  108.35  5087.7  109.03  5142.6  112.76
  5180.8   114.2  5264.9   116.3  5366.7  116.32  5547.4  119.45  5655.8  120.56
  5702.3  121.42  5764.1  121.59  5810.7  122.79  5815.8  122.55  5862.3  123.54
  5889.4  123.58  5965.6  124.73  6068.9     125  6182.4  124.73  6279.4  125.36
#Mann= 7 ,-1 , 0
  3871.9     .05       0    4856    .035       0  4976.2     .07       0
  5050.7     .05       0  5071.5     .07       0  5087.7     .12       0
  5889.4    .035       0
Bank Sta=5050.7,5071.5
XS Rating Curve= 0 ,0
Exp/Cntr=0.3,0.1

Type RM Length L Ch R = 1 ,29030   ,565,565,565
BEGIN DESCRIPTION:
TURKEY CREEK 31.0
END DESCRIPTION:
XS GIS Cut Line= 3
      2540324.99     13468625.01        2540725.       13467925.
      2541125.03     13467424.96
#Sta/Elev= 30
  4198.4  128.53  4410.8  124.43  4593.6  120.09  4624.6  119.01  4711.7  114.61
  4733.3  113.84  4749.1  112.81  4853.6  109.62  4916.1  106.35  4953.5  103.87
  4959.3  103.76  4964.6  102.99  4965.1  102.49  4985.2  102.49  4985.7  102.99
  5043.1  103.58  5061.5  104.68  5139.9  111.02  5160.7  111.86  5168.7  112.55
  5175.1  112.61  5183.1   113.3  5189.5  113.36  5203.9  114.74  5210.3  114.81
  5218.3  115.42  5317.6  117.69  5445.7  121.39  5588.1  127.01    5645  128.64
#Mann= 5 ,-1 , 0
  4198.4     .05       0  4853.6    .035       0  4964.6     .05       0
  4985.7    .035       0  5043.1     .07       0
Bank Sta=4964.6,4985.7
XS Rating Curve= 0 ,0
Exp/Cntr=0.3,0.1

Type RM Length L Ch R = 1 ,28465   ,565,565,565
BEGIN DESCRIPTION:
TURKEY CREEK 30.0
END DESCRIPTION:
XS GIS Cut Line= 3
      2540824.98     13468775.03        2541175.       13468225.
      2541475.02     13467674.96
#Sta/Elev= 30
  4352.7  127.21    4506  123.41  4621.1  119.92  4839.6  112.03  4862.3  111.28
  4881.9  110.53  4887.8  109.69  4903.1  108.68  4918.3  108.34  4924.2   107.5
  4933.5  107.33  4945.4  106.32  4954.7  106.15  4960.6  105.32  4975.9  104.91
  4991.1  103.29  5002.2  101.49  5002.7  100.99  5022.8  100.99  5023.3  101.49
  5060.1  103.15  5066.9  103.41  5094.4  104.69  5143.7  108.59  5171.3  109.34
  5203.5  109.84  5263.3  112.05  5312.7  114.91  5460.3  121.93  5631.2  127.53
#Mann= 8 ,-1 , 0
  4352.7     .05       0  4839.6    .035       0  4862.3     .12       0
  5002.2     .05       0  5023.3     .12       0  5060.1      .1       0
  5066.9     .12       0  5171.3     .07       0
Bank Sta=5002.2,5023.3
XS Rating Curve= 0 ,0
Exp/Cntr=0.3,0.1

Type RM Length L Ch R = 1 ,27900   ,564,564,564
BEGIN DESCRIPTION:
TURKEY CREEK 29.0
END DESCRIPTION:
XS GIS Cut Line= 3
      2541474.99     13469275.04        2541625.       13468525.
        2541525.     13467524.98
#Sta/Elev= 30
  4235.1  128.98  4294.5  127.15    4428   118.2  4490.1   113.8  4581.9  110.79
  4747.6  110.09  4762.6  110.06  4872.5  108.69  4979.2  103.06  4979.7  102.56
  4999.9  102.56  5000.4  103.06  5020.1  104.21  5070.4  103.38  5090.4   103.5
  5148.2   106.5  5153.3  106.24  5248.7  111.89  5253.8  111.51  5281.4  113.13
  5349.2  115.91  5389.8  117.13  5402.1   117.5  5449.7  119.02  5454.8  118.82
  5550.2   121.2  5756.2  125.01  5874.3  128.13  5952.2  129.29    6005  129.42
#Mann= 10 ,-1 , 0
  4235.1     .05       0  4294.5     .07       0    4428      .1       0
  4747.6    .035       0  4762.6      .1       0  4979.2     .05       0
  5000.4      .1       0  5070.4     .07       0  5389.8     .12       0
  5402.1     .07       0
Bank Sta=4979.2,5000.4
XS Rating Curve= 0 ,0
Exp/Cntr=0.3,0.1

Type RM Length L Ch R = 1 ,27336   ,589,589,589
BEGIN DESCRIPTION:
TURKEY CREEK 28.0
END DESCRIPTION:
XS GIS Cut Line= 3
      2541575.02     13469274.98        2542075.       13468825.
        2541975.     13467825.04
#Sta/Elev= 30
  4332.3  127.79  4410.4  125.16  4452.7  122.57  4488.9  120.51    4580  114.28
  4608.4  113.03  4657.8  109.81  4686.2  108.56    4743  107.06  4792.3  106.67
  4846.8  105.46    4991  100.99  4991.5  100.49  5011.7  100.49  5012.2  100.99
    5015  101.47  5065.3  104.15  5085.4  104.91  5095.4  104.78  5124.2  106.43
  5144.1  107.77  5153.2  108.56  5158.2   108.1  5195.9  110.75  5253.7  112.62
  5258.7  112.16  5296.4  114.48  5537.6  118.27  5879.3   124.9  6009.9  125.96
#Mann= 8 ,-1 , 0
  4332.3     .07       0  4452.7     .12       0  4488.9      .1       0
  4846.8     .12       0    4991     .05       0  5012.2     .12       0
  5124.2      .1       0  5144.1     .07       0
Bank Sta=4991,5012.2
XS Rating Curve= 0 ,0
Exp/Cntr=0.3,0.1

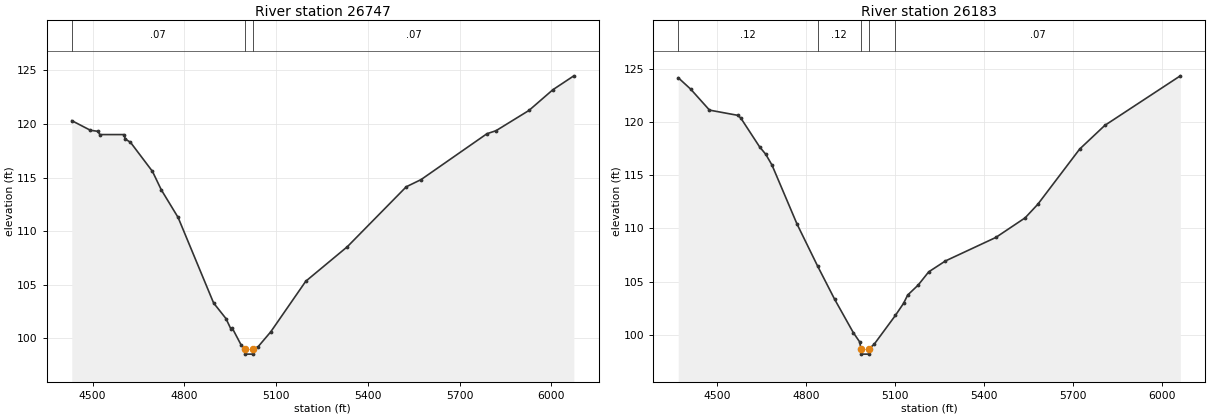
Type RM Length L Ch R = 1 ,26747   ,564,564,564
BEGIN DESCRIPTION:
TURKEY CREEK 27.0
END DESCRIPTION:
XS GIS Cut Line= 3
      2542560.02      13469485.6        2542625.       13468925.
        2542225.     13467924.99
#Sta/Elev= 30
  4431.8  120.31  4492.8  119.41    4518  119.31  4523.3  119.01  4601.9  119.01
    4607  118.59  4623.7  118.29  4695.7  115.57  4724.4  113.86  4779.4  111.28
  4895.5   103.3  4935.8  101.85  4951.8  100.89  4956.8  100.94  4986.1   99.35
  4997.6   99.03  4998.1   98.53  5023.8   98.53  5024.3   99.03  5040.6   99.21
  5082.3  100.61  5196.8  105.33  5332.7  108.55  5525.3  114.14  5573.7  114.81
  5789.1  119.09  5818.7  119.37  5926.4  121.26  6004.5  123.19  6073.2  124.49
#Mann= 3 ,-1 , 0
  4431.8     .07       0  4997.6     .05       0  5024.3     .07       0
Bank Sta=4997.6,5024.3
XS Rating Curve= 0 ,0
Exp/Cntr=0.3,0.1

Type RM Length L Ch R = 1 ,26183   ,591,591,591
BEGIN DESCRIPTION:
TURKEY CREEK 26.0
END DESCRIPTION:
XS GIS Cut Line= 3
        2543275.     13469224.99        2543075.       13468625.
        2542325.       13467875.
#Sta/Elev= 30
  4367.6   124.2  4409.8  123.12    4473  121.15  4567.9  120.66  4578.4  120.41
  4641.7   117.7  4662.7  116.99  4683.8  115.97  4768.1  110.42  4837.7  106.45
  4894.6  103.35  4957.9  100.19    4979   99.33    4984   98.66  4984.5   98.16
  5010.3   98.16  5010.8   98.66  5028.3   99.09    5100  101.81  5127.3  102.94
  5141.5  103.73  5176.8  104.67  5212.2  105.91  5268.7  106.94  5438.4  109.15
  5537.4     111  5579.9  112.27  5721.3  117.48  5806.1  119.71  6060.7  124.38
#Mann= 5 ,-1 , 0
  4367.6     .12       0  4837.7     .12       0    4984     .05       0
  5010.8     .12       0    5100     .07       0
Bank Sta=4984,5010.8
XS Rating Curve= 0 ,0
Exp/Cntr=0.3,0.1