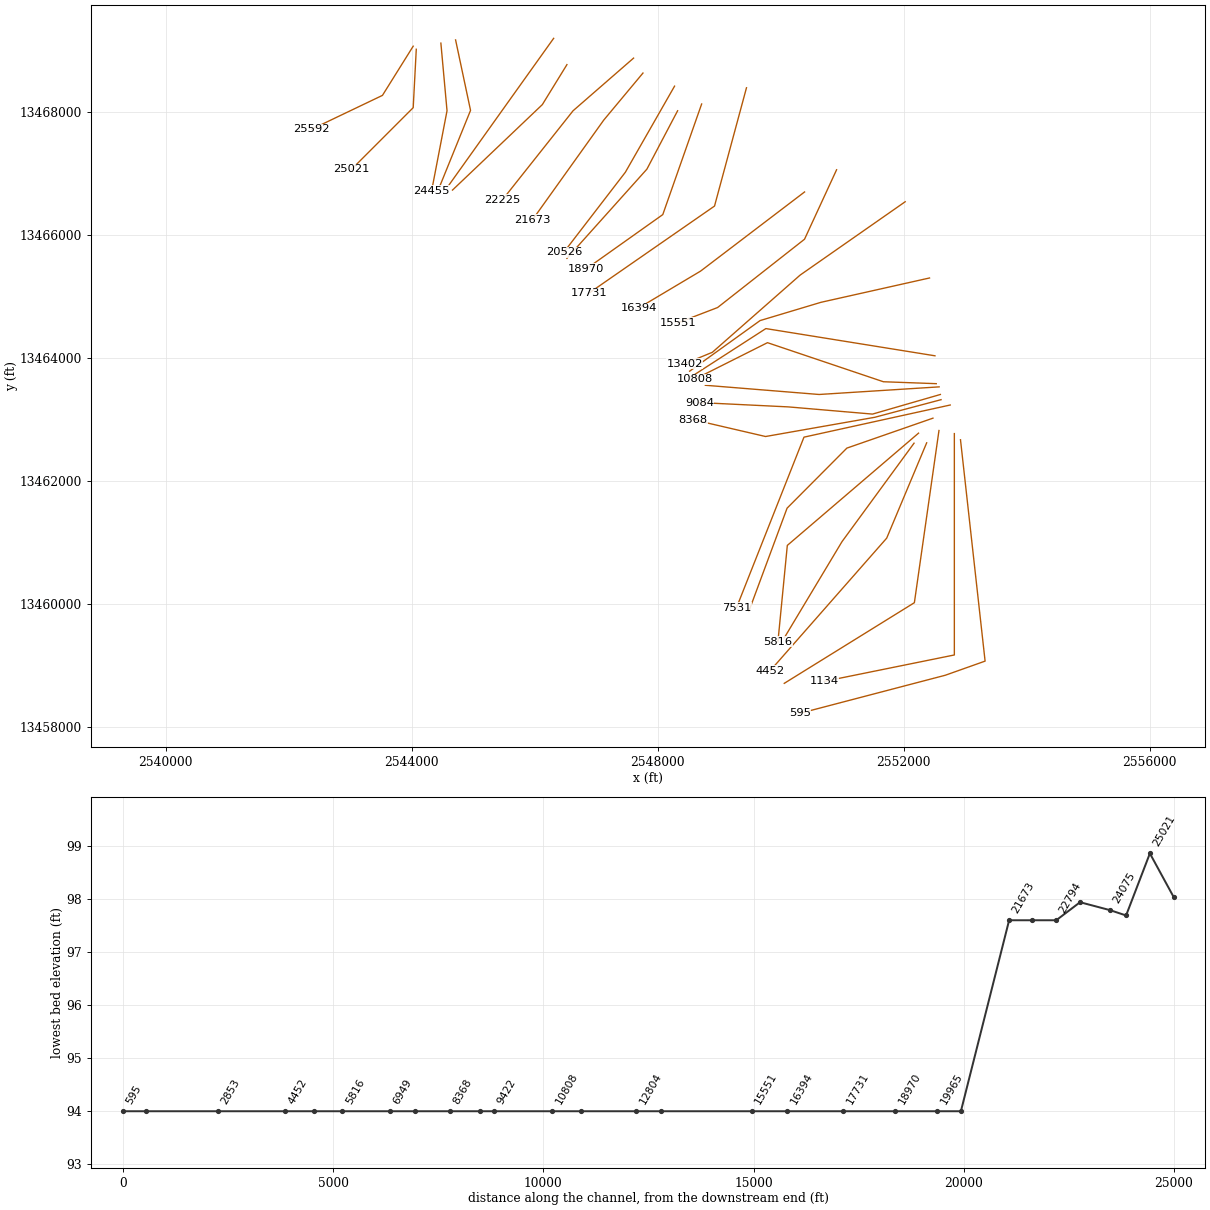
HEC-RAS study TURKEY CREEK.prj: TURKEY CREEK Base Level Engineering

--- TURKEY CREEK.g01 (geometry) --- (continued)

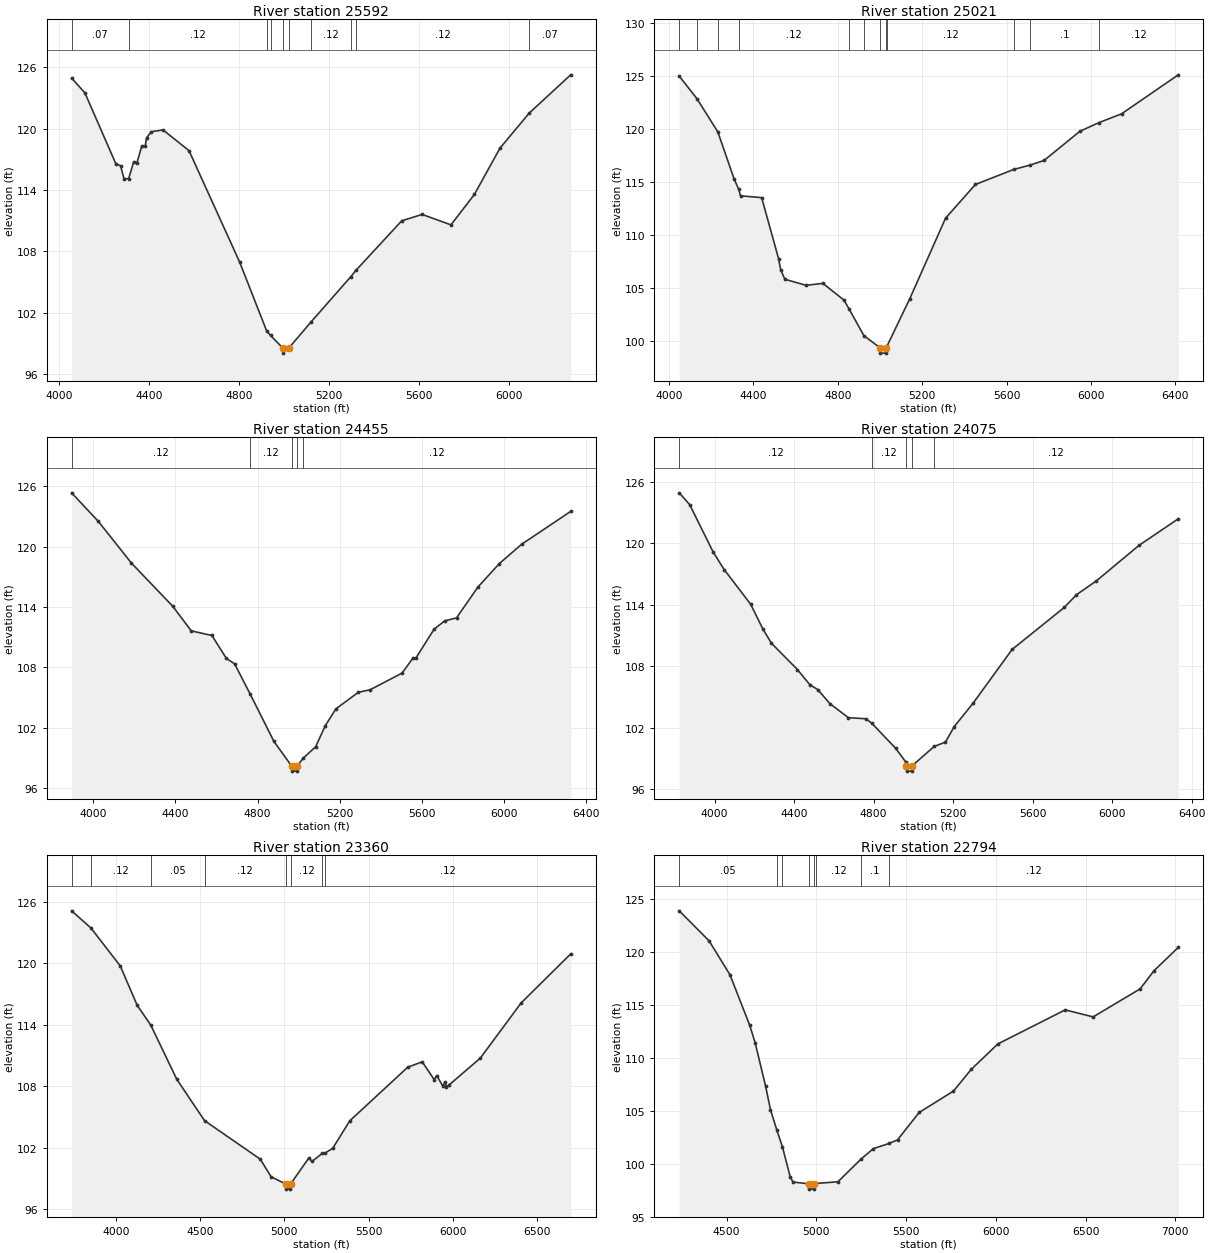
Type RM Length L Ch R = 1 ,25592   ,571,571,571
BEGIN DESCRIPTION:
TURKEY CREEK 25.0
END DESCRIPTION:
XS GIS Cut Line= 3
      2544024.98     13469074.96        2543525.       13468275.
      2542375.01       13467725.
#Sta/Elev= 30
  4056.9  124.94  4115.8   123.5  4253.2  116.57  4274.4  116.36  4289.8   115.1
  4310.4   115.1  4332.2   116.7  4347.5  116.67  4368.8  118.29  4384.1  118.29
    4390   119.1  4411.2  119.69  4463.1  119.87  4578.7  117.84  4803.9  106.93
  4923.5  100.22  4941.1   99.76  4995.4   98.53  4995.9   98.03  5022.3   98.53
  5120.6  101.07  5296.6  105.48  5322.2  106.17  5524.3  110.98    5615   111.6
  5742.9  110.58  5847.2  113.56  5960.6  118.08  6090.5  121.51    6275  125.26
#Mann= 10 ,-1 , 0
  4056.9     .07       0  4310.4     .12       0  4923.5    .033       0
  4941.1      .1       0  4995.4     .05       0  5022.3      .1       0
  5120.6     .12       0  5296.6     .07       0  5322.2     .12       0
  6090.5     .07       0
Bank Sta=4995.4,5022.3
XS Rating Curve= 0 ,0
Exp/Cntr=0.3,0.1

Type RM Length L Ch R = 1 ,25021   ,566,566,566
BEGIN DESCRIPTION:
TURKEY CREEK 24.0
END DESCRIPTION:
XS GIS Cut Line= 3
        2544075.     13469025.03        2544025.       13468075.
      2543024.97     13467074.97
#Sta/Elev= 30
  4048.1  124.96  4132.1  122.83    4231   119.7  4308.5  115.25  4329.9   114.3
  4338.5  113.68  4438.7  113.51  4518.8  107.77  4528.8  106.72  4548.8  105.82
    4649  105.25  4729.1  105.43  4829.2  103.85  4853.9  102.99  4923.3  100.51
  5000.1   99.36  5000.6   98.86  5026.6   98.86  5027.1   99.36  5032.5    99.5
  5140.9  103.99  5310.6  111.58    5452  114.75  5634.5  116.17  5710.1  116.57
  5777.3  117.01    5947  119.76  6038.1  120.58    6145  121.41  6413.7  125.08
#Mann= 12 ,-1 , 0
  4048.1     .07       0  4132.1     .12       0    4231     .07       0
  4329.9     .12       0  4853.9     .12       0  4923.3    .033       0
  5000.1    .033       0  5027.1    .033       0  5032.5     .12       0
  5634.5     .07       0  5710.1      .1       0  6038.1     .12       0
Bank Sta=5000.1,5027.1
XS Rating Curve= 0 ,0
Exp/Cntr=0.3,0.1

Type RM Length L Ch R = 1 ,24455   ,380,380,380
BEGIN DESCRIPTION:
TURKEY CREEK 23.0
END DESCRIPTION:
XS GIS Cut Line= 3
        2544475.     13469124.95        2544575.       13468025.
        2544325.     13466725.01
#Sta/Elev= 30
  3895.5  125.37    4026  122.52  4186.6  118.38  4387.5  114.09  4477.8  111.64
  4578.3  111.18  4648.5   108.9  4688.7  108.36  4763.4  105.39  4879.5  100.66
  4966.3   98.19  4966.8   97.69    4993   97.69  4993.5   98.19  5021.1   98.95
    5083  100.12  5129.8  102.21  5181.8  103.89  5290.7  105.53  5347.7  105.78
  5503.6  107.44  5555.5  108.91  5570.3  108.93  5659.4  111.81  5711.3  112.64
  5768.3  112.93  5872.2  115.99  5976.1  118.32    6085  120.25  6323.8  123.52
#Mann= 5 ,-1 , 0
  3895.5     .12       0  4763.4     .12       0  4966.3     .05       0
  4993.5     .12       0  5021.1     .12       0
Bank Sta=4966.3,4993.5
XS Rating Curve= 0 ,0
Exp/Cntr=0.3,0.1

Type RM Length L Ch R = 1 ,24075   ,715,715,715
BEGIN DESCRIPTION:
Mapping XS 6ca4708f
END DESCRIPTION:
XS GIS Cut Line= 3
      2544714.34     13469176.58       2544957.4     13468030.76
      2544454.02     13466789.68
#Sta/Elev= 30
  3822.4  124.91  3875.1  123.75  3993.5  119.12  4048.9  117.42  4181.8  114.05
  4243.1  111.64  4286.3  110.25  4416.9  107.69  4479.8   106.2  4519.1  105.74
  4580.5  104.36  4673.3     103  4762.3  102.89  4791.9  102.44  4911.3  100.01
  4960.9   98.71  4965.5   98.29    4966   97.79  4992.3   97.79  4992.8   98.29
  5105.2   100.2  5161.8  100.62    5205  102.11  5301.4  104.43    5497  109.65
  5759.5  113.74  5820.1  114.97  5920.3  116.32  6134.6  119.78    6333  122.38
#Mann= 5 ,-1 , 0
  3822.4     .12       0  4791.9     .12       0  4965.5     .05       0
  4992.8     .12       0  5105.2     .12       0
Bank Sta=4965.5,4992.8
XS Rating Curve= 0 ,0
Exp/Cntr=0.3,0.1

Type RM Length L Ch R = 1 ,23360   ,566,566,566
BEGIN DESCRIPTION:
TURKEY CREEK 21.0
END DESCRIPTION:
XS GIS Cut Line= 3
      2546308.94      13469202.6        2545575.       13468175.
      2544588.87     13466792.31
#Sta/Elev= 30
  3737.6  125.11  3851.8  123.44  4025.9  119.74  4126.6  115.89  4207.4  113.95
  4361.4  108.67  4526.1  104.63  4856.6  100.87  4921.7   99.14  5008.3   98.44
  5008.8   97.94  5036.2   97.94  5036.7   98.44  5144.2  100.96  5165.1  100.66
  5224.5  101.42  5243.8  101.49  5286.8  101.92  5387.6   104.6  5731.8  109.84
  5817.8  110.37  5889.1  108.63  5903.9  109.03  5939.5  108.01  5954.3  108.42
  5960.4  107.94  5975.1  108.08    6162  110.72  6405.4  116.13  6698.7   120.9
#Mann= 8 ,-1 , 0
  3737.6     .07       0  3851.8     .12       0  4207.4     .05       0
  4526.1     .12       0  5008.3     .05       0  5036.7     .12       0
  5224.5      .1       0  5243.8     .12       0
Bank Sta=5008.3,5036.7
XS Rating Curve= 0 ,0
Exp/Cntr=0.3,0.1

Type RM Length L Ch R = 1 ,22794   ,569,569,569
BEGIN DESCRIPTION:
TURKEY CREEK 20.0
END DESCRIPTION:
XS GIS Cut Line= 3
        2546525.     13468775.01        2546125.       13468125.
      2544664.13     13466735.18
#Sta/Elev= 30
  4236.8  123.84    4403  121.01    4519  117.82  4629.1  113.06  4659.5   111.4
  4717.9   107.3    4745  105.08  4780.8  103.14  4811.2   101.6  4855.1   98.74
  4870.5   98.27  4956.8    98.1  4957.3    97.6  4984.8    97.6  4985.3    98.1
  5001.2   98.14  5120.3   98.29  5249.8  100.44  5318.2  101.42  5406.5  101.91
  5452.8  102.25    5573  104.83  5763.9  106.84    5863  108.89  6011.4  111.29
  6386.4   114.5  6542.1  113.84  6803.8  116.48  6881.4   118.2  7016.4  120.39
#Mann= 8 ,-1 , 0
  4236.8     .05       0  4780.8     .12       0  4811.2    .035       0
  4956.8    .035       0  4985.3    .035       0  5001.2     .12       0
  5249.8      .1       0  5406.5     .12       0
Bank Sta=4956.8,4985.3
XS Rating Curve= 0 ,0
Exp/Cntr=0.3,0.1

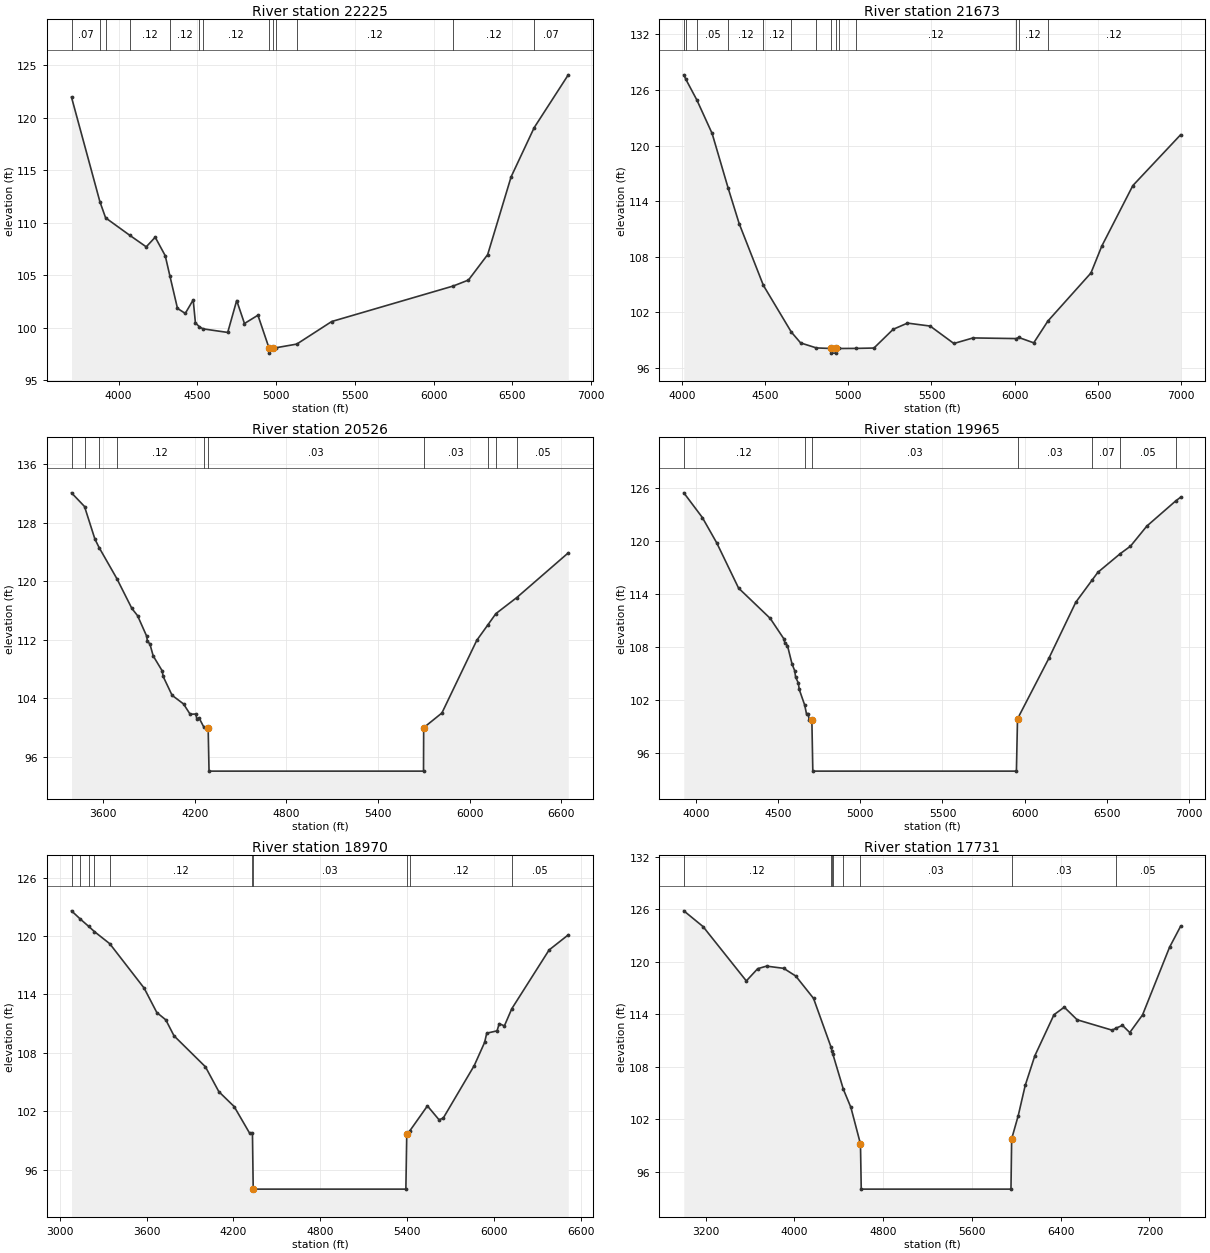
Type RM Length L Ch R = 1 ,22225   ,552,552,552
BEGIN DESCRIPTION:
TURKEY CREEK 19.0
END DESCRIPTION:
XS GIS Cut Line= 3
      2547608.57     13468881.02        2546625.       13468025.
      2545474.99     13466574.99
#Sta/Elev= 30
  3700.8  121.97  3881.1  112.02  3917.4  110.48  4070.8  108.82  4175.4  107.72
  4232.3  108.64  4295.9  106.88    4325  104.99  4373.8  101.86  4423.2  101.38
  4473.5  102.67  4487.7  100.48    4513  100.11  4536.4   99.91  4692.8   99.57
  4749.8  102.61  4799.2  100.42  4884.6  101.21  4954.8    98.1  4955.3    97.6
  4983.3    98.1  5002.1   98.12  5131.3   98.46  5353.2  100.61  6124.7  103.99
  6221.7  104.56  6343.5  106.98  6492.5  114.39  6638.9  119.07  6855.4   124.1
#Mann= 13 ,-1 , 0
  3700.8     .07       0  3881.1     .05       0  3917.4     .07       0
  4070.8     .12       0    4325     .12       0    4513     .07       0
  4536.4     .12       0  4954.8     .05       0  4983.3     .12       0
  5002.1    .033       0  5131.3     .12       0  6124.7     .12       0
  6638.9     .07       0
Bank Sta=4954.8,4983.3
XS Rating Curve= 0 ,0
Exp/Cntr=0.3,0.1

Type RM Length L Ch R = 1 ,21673   ,1147,1147,1147
BEGIN DESCRIPTION:
TURKEY CREEK 18.0
END DESCRIPTION:
XS GIS Cut Line= 3
      2547761.37     13468637.98        2547125.       13467875.
      2545965.63     13466252.97
#Sta/Elev= 30
  4010.9  127.63  4022.5  127.17  4089.5  124.91  4181.2   121.3  4277.8  115.39
  4343.9  111.57  4489.4  104.91  4657.5   99.87  4713.5    98.7  4808.4   98.16
  4898.3    98.1  4898.8    97.6  4926.6    97.6  4927.1    98.1  4941.5    98.1
    5044   98.11  5154.3   98.15  5269.8  100.17  5355.9  100.84  5492.3  100.52
  5634.8   98.64  5750.3   99.24  6009.5   99.17  6025.1   99.29  6115.2   98.71
  6200.2  101.06  6459.3  106.25  6524.4  109.15  6711.2  115.68  6998.2  121.16
#Mann= 14 ,-1 , 0
  4010.9     .05       0  4022.5     .07       0  4089.5     .05       0
  4277.8     .12       0  4489.4     .12       0  4657.5    .035       0
  4808.4    .033       0  4898.3    .035       0  4927.1    .033       0
  4941.5    .035       0    5044     .12       0  6009.5    .033       0
  6025.1     .12       0  6200.2     .12       0
Bank Sta=4898.3,4927.1
XS Rating Curve= 0 ,0
Exp/Cntr=0.3,0.1

Type RM Length L Ch R = 1 ,20526   ,561,561,561
BEGIN DESCRIPTION:
TURKEY CREEK 17.0
END DESCRIPTION:
XS GIS Cut Line= 3
      2548274.99     13468424.98        2547475.       13467025.
      2546474.97     13465724.96
#Sta/Elev= 30
  3392.5  132.06  3477.7  130.19  3545.8  125.73  3573.7  124.56  3689.1  120.34
  3787.7  116.25  3825.1  115.26  3884.1  112.48  3889.9  111.74  3905.7   111.4
  3927.3  109.76  3986.4  107.71  3992.1  106.97  4051.1  104.37    4126  103.19
  4169.2  101.78  4206.6  101.81  4212.4  101.18  4228.2  101.25  4257.1  100.09
  4287.2   99.92    4293      94  5697.3      94 5698.39  99.941  5817.7  101.95
  6046.1  111.89    6120  114.04  6171.2  115.54  6308.1  117.74  6645.1  123.85
#Mann= 10 ,-1 , 0
  3392.5     .07       0  3477.7     .12       0  3573.7     .07       0
  3689.1     .12       0  4257.1     .12       0  4287.2     .03       0
 5698.39     .03       0    6120     .07       0  6171.2     .12       0
  6308.1     .05       0
Bank Sta=4287.2,5698.39
XS Rating Curve= 0 ,0
Exp/Cntr=0.3,0.1

Type RM Length L Ch R = 1 ,19965   ,995,995,995
BEGIN DESCRIPTION:
TURKEY CREEK 16.0
END DESCRIPTION:
XS GIS Cut Line= 3
      2548324.98     13468024.97        2547825.       13467075.
      2546525.03     13465625.03
#Sta/Elev= 30
  3927.2  125.46  4039.9  122.67    4128  119.78  4260.2  114.69  4452.9  111.26
  4535.4  108.96  4541.1  108.53  4557.4   108.2  4585.1  106.13  4601.5  105.35
  4607.2  104.62  4623.6  103.96  4629.2  103.23  4662.4  101.46  4673.3  100.47
    4684  100.47  4689.7   99.74    4706   99.74  4711.7      94  5949.8      94
  5956.5   99.91  6147.9  106.78  6310.8  113.09  6412.2  115.65  6445.4  116.48
  6581.8  118.59  6643.5  119.43  6742.9   121.7  6917.6  124.53  6948.1  124.96
#Mann= 7 ,-1 , 0
  3927.2     .12       0  4662.4     .12       0    4706     .03       0
  5956.5     .03       0  6412.2     .07       0  6581.8     .05       0
  6917.6    .035       0
Bank Sta=4706,5956.5
XS Rating Curve= 0 ,0
Exp/Cntr=0.3,0.1

Type RM Length L Ch R = 1 ,18970   ,1239,1239,1239
BEGIN DESCRIPTION:
Mapping XS 9c86c893
END DESCRIPTION:
XS GIS Cut Line= 3
      2548715.66     13468134.96       2548083.7     13466336.32
      2546840.62     13465454.36
#Sta/Elev= 30
  3081.4  122.59  3143.2  121.73  3201.1  120.98  3240.1  120.45  3345.7  119.21
    3583  114.65  3670.6  112.14  3732.6  111.39  3789.3  109.75  4006.1  106.57
  4099.1  104.01  4204.9  102.48  4310.9   99.76    4331   99.76  4336.3      94
  5390.5      94  5396.6   99.62  5418.4     100  5539.3  102.55  5619.3  101.13
  5648.3  101.29  5862.9   106.7  5934.2  109.07    5949  110.02  6020.3  110.26
  6035.1     111  6070.8  110.77  6122.2  112.54  6379.6  118.57    6512  120.12
#Mann= 10 ,-1 , 0
  3081.4     .12       0  3143.2     .07       0  3201.1     .12       0
  3240.1     .07       0  3345.7     .12       0    4331     .03       0
  4336.3     .03       0  5396.6     .03       0  5418.4     .12       0
  6122.2     .05       0
Bank Sta=4336.3,5396.6
XS Rating Curve= 0 ,0
Exp/Cntr=0.3,0.1

Type RM Length L Ch R = 1 ,17731   ,1337,1337,1337
BEGIN DESCRIPTION:
TURKEY CREEK 15.0
END DESCRIPTION:
XS GIS Cut Line= 3
      2549444.82     13468398.85        2548925.       13466475.
      2546883.37     13465059.27
#Sta/Elev= 30
  3003.8   125.8  3177.2     124  3567.2  117.79  3669.8  119.19  3749.6  119.48
  3903.9  119.23  4012.6  118.35  4172.8   115.8  4329.4  110.27  4339.5  109.75
  4345.7  109.49    4442   105.4  4509.8  103.33    4596   99.16    4603      94
  5952.5      94  5958.6   99.74    6018   102.4  6080.8  105.85  6167.3  109.23
  6340.2  113.93  6432.8  114.79    6549  113.35  6865.1  112.16  6896.6  112.38
  6957.6  112.71  7023.2  111.89  7138.4  113.91  7381.8  121.64  7481.1  124.03
#Mann= 8 ,-1 , 0
  3003.8     .12       0  4329.4    .035       0  4339.5     .12       0
  4345.7    .035       0    4442     .12       0    4596     .03       0
  5958.6     .03       0  6896.6     .05       0
Bank Sta=4596,5958.6
XS Rating Curve= 0 ,0
Exp/Cntr=0.3,0.1

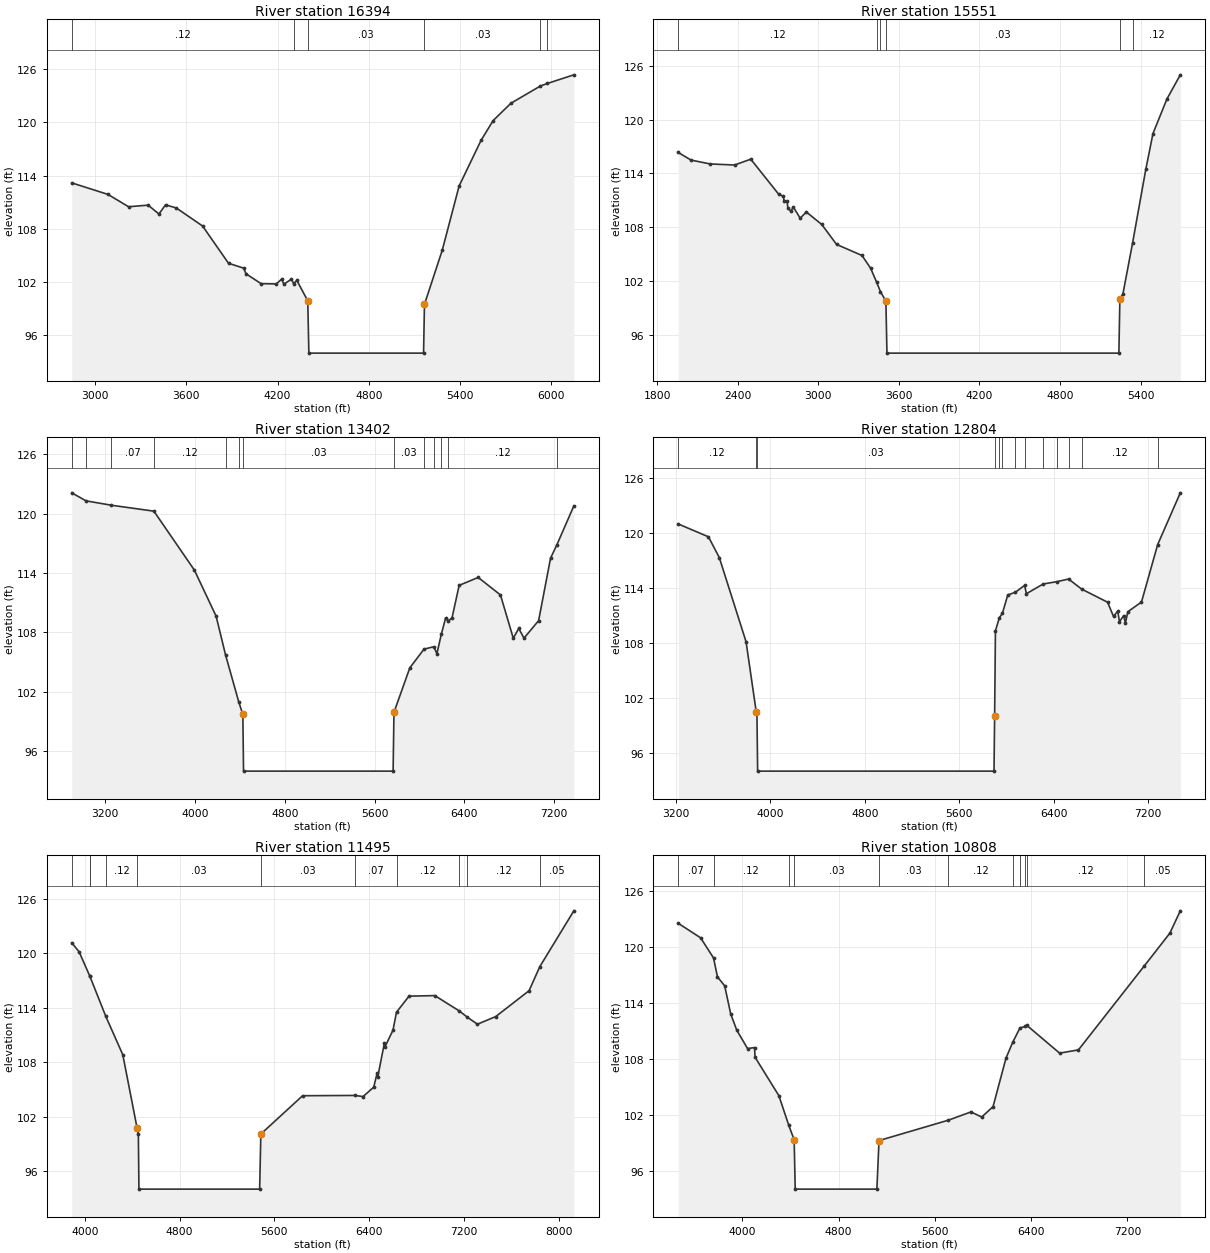
Type RM Length L Ch R = 1 ,16394   ,843,843,843
BEGIN DESCRIPTION:
TURKEY CREEK 14.0
END DESCRIPTION:
XS GIS Cut Line= 3
      2550389.24     13466704.36      2548698.28     13465417.27
      2547688.92     13464816.11
#Sta/Elev= 30
  2847.4  113.19  3085.5  111.89  3220.7   110.5  3349.5  110.68  3420.3  109.68
  3463.9  110.72  3534.6  110.36  3707.1  108.33  3877.6  104.13  3977.4  103.58
    3992  102.95  4091.8  101.83  4191.6   101.8  4226.9  102.34  4241.5  101.77
  4291.4  102.34  4305.6  101.83  4326.7   102.2  4398.5   99.89  4405.7      94
  5159.6      94  5165.5    99.5  5282.3  105.59  5393.3  112.84  5537.3  117.98
  5617.2  120.22    5734  122.17  5927.4  124.11  5973.9   124.4  6147.3  125.37
#Mann= 6 ,-1 , 0
  2847.4     .12       0  4305.6    .033       0  4398.5     .03       0
  5165.5     .03       0  5927.4     .07       0  5973.9     .05       0
Bank Sta=4398.5,5165.5
XS Rating Curve= 0 ,0
Exp/Cntr=0.3,0.1

Type RM Length L Ch R = 1 ,15551   ,2149,2149,2149
BEGIN DESCRIPTION:
TURKEY CREEK 13.0
END DESCRIPTION:
XS GIS Cut Line= 4
      2550910.09     13467065.49      2550388.58     13465935.67
        2548975.       13464825.      2548325.01     13464575.01
#Sta/Elev= 30
  1957.6  116.34  2052.5  115.49  2195.7  115.06  2376.7  114.94  2497.8  115.59
  2707.1  111.66  2739.9  111.48  2745.4  110.99  2768.4  110.89  2773.9  110.14
  2796.8   109.8  2814.3  110.27  2865.7  109.02  2911.5  109.71  3026.3  108.32
  3136.6   106.1  3325.9  104.87  3390.1  103.45    3434  101.93  3462.9  100.86
  3503.9   99.78  3511.7      94  5238.6      94  5246.1  100.04  5268.6  100.58
  5340.2  106.22    5439  114.45  5492.5  118.44  5596.5  122.29  5696.1  124.98
#Mann= 6 ,-1 , 0
  1957.6     .12       0    3434     .12       0  3462.9    .033       0
  3503.9     .03       0  5246.1     .03       0  5340.2     .12       0
Bank Sta=3503.9,5246.1
XS Rating Curve= 0 ,0
Exp/Cntr=0.3,0.1

Type RM Length L Ch R = 1 ,13402   ,598,598,598
BEGIN DESCRIPTION:
Mapping XS c1550b6a
END DESCRIPTION:
XS GIS Cut Line= 4
      2552025.55     13466545.22      2550317.18     13465352.48
       2548890.1     13464097.28       2548438.8     13463910.53
#Sta/Elev= 30
  2902.5  122.09  3029.4  121.28  3254.5  120.84    3634  120.24  3994.7  114.29
  4188.3  109.64  4273.3  105.69  4390.9  100.95  4426.5   99.72  4432.6      94
    5765      94  5772.6   99.93    5914  104.43  6040.2  106.31    6128  106.56
    6155  105.85  6194.4  107.81  6232.8  109.46  6255.8  109.16  6289.7  109.46
  6353.3  112.75  6523.1  113.55  6721.4  111.78  6835.2  107.42  6884.5   108.4
  6930.9  107.42  7061.2  109.19  7167.6   115.5  7223.1  116.82    7375  120.77
#Mann= 13 ,-1 , 0
  2902.5     .07       0  3029.4     .12       0  3254.5     .07       0
    3634     .12       0  4273.3     .12       0  4390.9    .033       0
  4426.5     .03       0  5772.6     .03       0  6040.2     .07       0
    6128    .033       0  6194.4     .07       0  6255.8     .12       0
  7223.1     .05       0
Bank Sta=4426.5,5772.6
XS Rating Curve= 0 ,0
Exp/Cntr=0.3,0.1

Type RM Length L Ch R = 1 ,12804   ,1309,1309,1309
BEGIN DESCRIPTION:
Mapping XS aa1c4852
END DESCRIPTION:
XS GIS Cut Line= 4
      2552421.36     13465305.61      2550655.72     13464909.78
      2549666.14      13464612.9      2548520.33       13463790.
#Sta/Elev= 30
  3219.1  120.98    3475  119.58  3566.8  117.32  3793.8  108.12  3880.6   100.4
  3885.7   100.4  3891.7      94  5894.2      94  5899.4  100.02  5906.3  109.31
  5938.9  110.73  5964.9  111.21  6010.7  113.23  6074.1  113.52  6153.2  114.27
  6168.7  113.37  6311.4  114.43    6430  114.69  6525.8  114.97  6636.8  113.87
  6856.2  112.44  6906.6  110.88  6942.2  111.47  6956.9  110.32  6992.5  110.97
  7007.3  110.16  7028.1   111.4  7143.5  112.46  7280.6  118.73  7472.4  124.38
#Mann= 13 ,-1 , 0
  3219.1     .12       0  3880.6     .12       0  3885.7     .03       0
  5899.4     .03       0  5938.9     .07       0  5964.9     .12       0
  6074.1     .07       0  6153.2     .12       0  6311.4     .07       0
    6430     .12       0  6525.8     .07       0  6636.8     .12       0
  7280.6     .05       0
Bank Sta=3880.6,5899.4
XS Rating Curve= 0 ,0
Exp/Cntr=0.3,0.1

Type RM Length L Ch R = 1 ,11495   ,687,687,687
BEGIN DESCRIPTION:
Mapping XS c8c3c76b
END DESCRIPTION:
XS GIS Cut Line= 3
      2552509.91     13464039.98      2549759.89     13464482.69
      2548541.14     13463696.23
#Sta/Elev= 30
  3890.8  121.14  3952.7  120.15  4041.6  117.51  4041.7  117.51  4178.3  113.02
  4321.2  108.81  4442.7  100.68  4452.5  100.06  4457.5      94  5475.9      94
    5486  100.07  5838.4  104.29  6278.3  104.32  6348.3   104.2  6438.1  105.23
    6467  106.77    6472  106.34  6528.8  110.12  6533.9   109.7  6600.8  111.51
  6630.5  113.49  6736.1  115.26  6953.8  115.32  7161.3  113.62  7229.1  112.93
  7313.5  112.17  7467.5  113.01    7749  115.86  7839.9  118.52  8126.7  124.66
#Mann= 11 ,-1 , 0
  3890.8     .07       0  4041.6     .12       0  4041.7     .07       0
  4178.3     .12       0  4442.7     .03       0    5486     .03       0
  6278.3     .07       0  6630.5     .12       0  7161.3     .07       0
  7229.1     .12       0  7839.9     .05       0
Bank Sta=4442.7,5486
XS Rating Curve= 0 ,0
Exp/Cntr=0.3,0.1

Type RM Length L Ch R = 1 ,10808   ,1386,1386,1386
BEGIN DESCRIPTION:
Mapping XS 66dd1c39
END DESCRIPTION:
XS GIS Cut Line= 4
      2552530.69     13463586.86      2551671.35     13463618.11
      2549785.93     13464253.53      2548603.85     13463659.88
#Sta/Elev= 30
  3466.7  122.58  3652.5  121.02  3760.2  118.85  3792.6  116.82  3852.6  115.86
  3902.7  112.84  3952.7   111.1  4042.8  109.11  4100.6  109.22  4105.6  108.17
  4302.9  104.05  4384.8  100.88    4430    99.3  4438.8      94  5117.4      94
  5135.3   99.22  5711.1  101.41  5899.3   102.3  5988.4  101.75  6082.9  102.87
  6190.6  108.09  6246.5  109.79  6306.4  111.33  6351.9  111.49  6362.4  111.62
  6636.1  108.62  6792.4  108.97  7340.6  118.01  7551.7  121.51    7639  123.92
#Mann= 11 ,-1 , 0
  3466.7     .07       0  3760.2     .12       0  4384.8     .03       0
    4430     .03       0  5135.3     .03       0  5711.1     .12       0
  6246.5     .07       0  6306.4     .12       0  6351.9     .07       0
  6362.4     .12       0  7340.6     .05       0
Bank Sta=4430,5135.3
XS Rating Curve= 0 ,0
Exp/Cntr=0.3,0.1

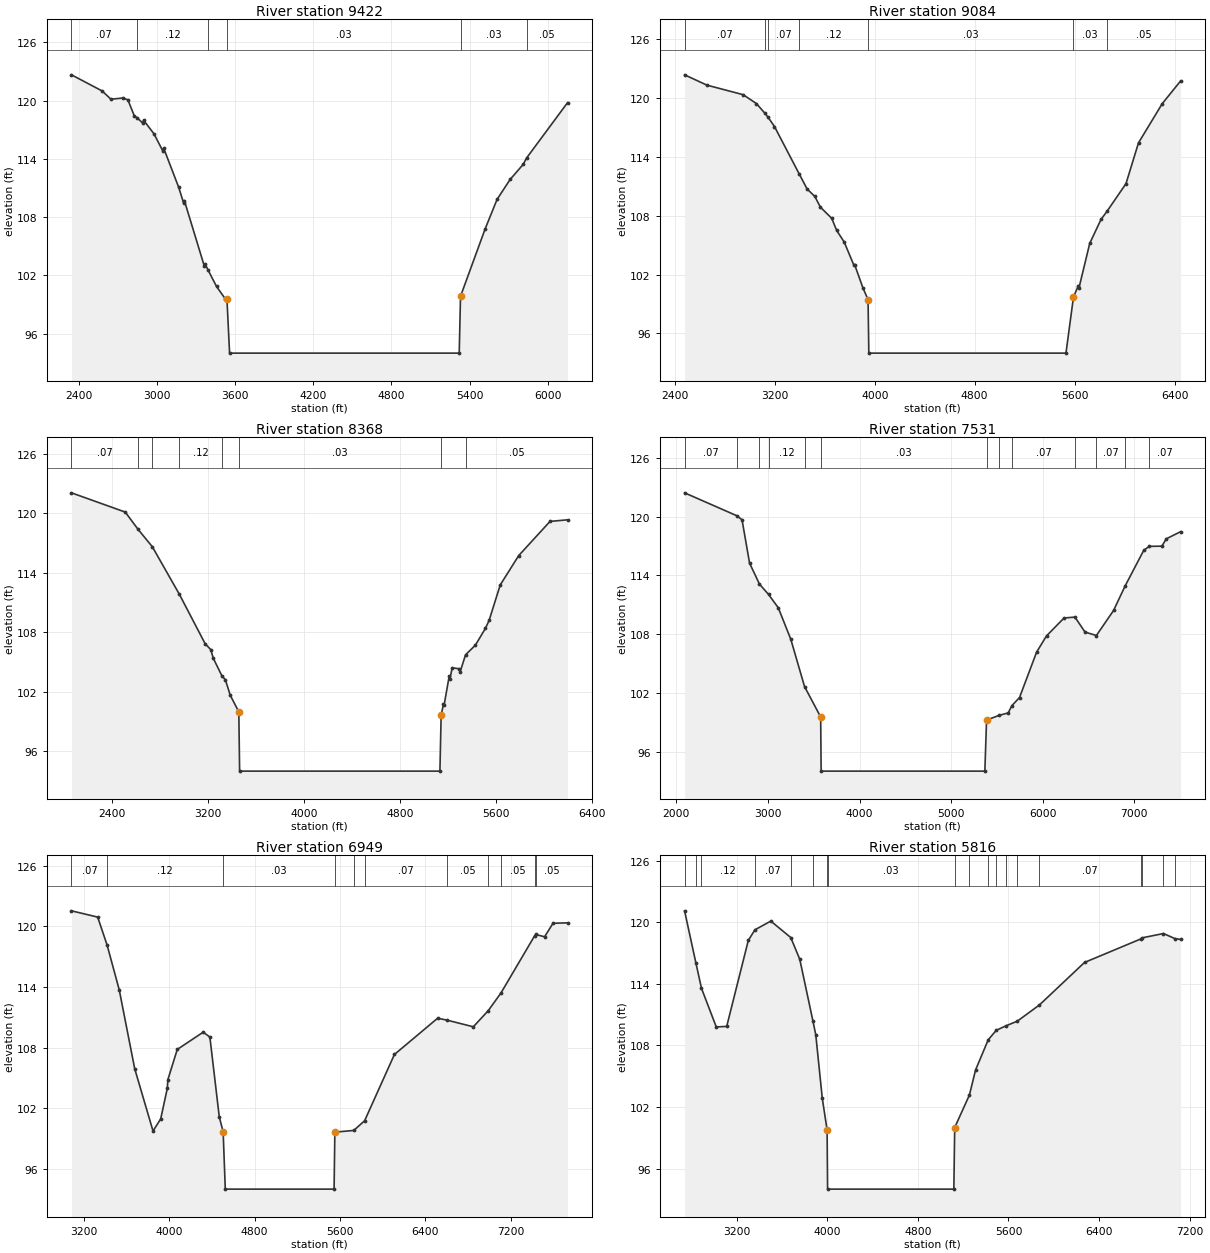
Type RM Length L Ch R = 1 ,9422    ,338,338,338
BEGIN DESCRIPTION:
Mapping XS 1615db5d
END DESCRIPTION:
XS GIS Cut Line= 3
      2552577.64     13463534.78      2550625.37     13463410.97
      2548775.52     13463560.82
#Sta/Elev= 30
  2340.6  122.65  2576.4  120.99  2643.8  120.14  2735.6  120.26  2774.1  120.08
  2824.2   118.4  2844.5  118.24  2889.7  117.66  2894.7  117.98  2974.5  116.58
  3043.9  114.78  3048.9  115.11  3164.9  111.06    3203  109.43    3208  109.71
  3362.2  102.93  3367.2   103.2  3389.3  102.58  3455.5  100.86  3521.4   99.61
  3535.6   99.54  3555.7      94  5320.5      94  5330.5   99.85  5519.7  106.79
  5611.5  109.83  5711.8  111.88  5812.1  113.43  5838.3  114.09  6152.7  119.78
#Mann= 6 ,-1 , 0
  2340.6     .07       0  2844.5     .12       0  3389.3    .033       0
  3535.6     .03       0  5330.5     .03       0  5838.3     .05       0
Bank Sta=3535.6,5330.5
XS Rating Curve= 0 ,0
Exp/Cntr=0.3,0.1

Type RM Length L Ch R = 1 ,9084    ,716,716,716
BEGIN DESCRIPTION:
Mapping XS 82ee7de1
END DESCRIPTION:
XS GIS Cut Line= 4
      2552597.55     13463410.96      2551494.27     13463092.07
      2550125.31     13463209.16      2548678.31     13463279.48
#Sta/Elev= 30
  2477.6  122.32  2656.6  121.27  2946.3   120.3  3052.4   119.4  3121.3   118.4
  3146.2     118  3197.3  117.06  3397.5  112.18  3458.7   110.7  3520.7  109.94
  3564.7  108.86  3655.4  107.72  3695.6  106.48  3755.8   105.3  3833.8  102.92
  3838.8  103.01  3906.3  100.61  3946.5   99.44  3952.6      94  5530.9      94
    5591   99.71  5630.7  100.88  5635.7  100.67  5721.2  105.17  5811.3   107.6
  5859.5  108.43  6011.5  111.25  6111.6   115.4  6301.8  119.39  6448.7   121.7
#Mann= 7 ,-1 , 0
  2477.6     .07       0  3121.3     .12       0  3146.2     .07       0
  3397.5     .12       0  3946.5     .03       0    5591     .03       0
  5859.5     .05       0
Bank Sta=3946.5,5591
XS Rating Curve= 0 ,0
Exp/Cntr=0.3,0.1

Type RM Length L Ch R = 1 ,8368    ,837,837,837
BEGIN DESCRIPTION:
Mapping XS d0dc79c7
END DESCRIPTION:
XS GIS Cut Line= 4
      2552608.88     13463326.45      2551530.72     13463039.98
      2549754.68     13462727.48      2548568.59      13463003.2
#Sta/Elev= 30
  2060.5  122.04  2509.1   120.1  2616.5  118.35  2734.7  116.61  2959.2  111.84
    3176  106.82  3222.5  106.24  3242.8  105.38    3315   103.6  3344.2   103.2
  3384.9  101.64    3456   99.97  3462.8      94  5133.1      94  5143.3   99.61
  5162.9  100.77  5168.1  100.65  5210.7  103.58  5215.8  103.25  5235.7  104.41
  5295.9  104.31  5301.1  103.98  5346.9  105.72  5428.9  106.69  5512.9  108.39
  5543.7   109.2  5636.1  112.76  5790.4  115.72  6051.2  119.16  6197.1  119.32
#Mann= 8 ,-1 , 0
  2060.5     .07       0  2616.5     .12       0  2734.7     .07       0
  2959.2     .12       0    3315    .033       0    3456     .03       0
  5143.3     .03       0  5346.9     .05       0
Bank Sta=3456,5143.3
XS Rating Curve= 0 ,0
Exp/Cntr=0.3,0.1

Type RM Length L Ch R = 1 ,7531    ,582,582,582
BEGIN DESCRIPTION:
Mapping XS cd5b23e1
END DESCRIPTION:
XS GIS Cut Line= 3
       2552758.1     13463239.86      2550379.68     13462717.07
      2549282.72     13459944.27
#Sta/Elev= 30
  2089.4  122.44  2662.2  120.09  2717.1  119.68  2799.1  115.26  2906.8  113.12
  3006.8  112.05  3112.4   110.7  3248.9  107.49  3399.6  102.64  3575.7   99.53
  3580.8      94  5368.7      94  5387.2   99.21  5520.9   99.69  5623.7   99.95
  5664.4   100.7  5747.2  101.52  5933.8  106.16  6041.9  107.82  6233.8  109.65
  6352.5  109.74  6462.6  108.21  6586.7  107.86  6774.4  110.42  6900.8  112.93
  7104.3  116.57  7164.6  116.97  7301.6  116.99  7350.3  117.74  7506.5  118.47
#Mann= 13 ,-1 , 0
  2089.4     .07       0  2662.2     .12       0  2906.8     .07       0
  3006.8     .12       0  3399.6    .033       0  3575.7     .03       0
  5387.2     .03       0  5520.9     .12       0  5664.4     .07       0
  6352.5     .05       0  6586.7     .07       0  6900.8     .05       0
  7164.6     .07       0
Bank Sta=3575.7,5387.2
XS Rating Curve= 0 ,0
Exp/Cntr=0.3,0.1

Type RM Length L Ch R = 1 ,6949    ,1133,1133,1133
BEGIN DESCRIPTION:
Mapping XS 40ed17d8
END DESCRIPTION:
XS GIS Cut Line= 4
      2552477.12     13463025.83      2551077.27     13462538.86
      2550105.05      13461562.3      2549482.37     13459883.49
#Sta/Elev= 30
  3082.7  121.55  3328.5  120.93  3417.9  118.12  3530.7  113.72  3675.6  105.92
  3847.3   99.75  3919.2  100.95  3981.4  103.98  3986.6  104.84  4074.7  107.83
  4318.2  109.54  4380.4  109.05  4468.4  101.16  4504.8   99.66  4524.9      94
    5545      94  5552.1   99.64  5729.6   99.81  5831.2  100.77  6110.6  107.33
  6515.9  110.92  6607.3  110.72  6850.3  110.07  6989.8  111.66  7109.7  113.42
  7424.2  119.06    7435  119.21  7518.5  118.98  7597.5  120.32  7733.4  120.36
#Mann= 11 ,-1 , 0
  3082.7     .07       0  3417.9     .12       0  4504.8     .03       0
  5552.1     .03       0  5729.6     .12       0  5831.2     .07       0
  6607.3     .05       0  6989.8     .07       0  7109.7     .05       0
  7424.2     .07       0    7435     .05       0
Bank Sta=4504.8,5552.1
XS Rating Curve= 0 ,0
Exp/Cntr=0.3,0.1

Type RM Length L Ch R = 1 ,5816    ,675,675,675
BEGIN DESCRIPTION:
Mapping XS a6d1a505
END DESCRIPTION:
XS GIS Cut Line= 3
      2552242.59     13462782.18      2550108.85     13460956.65
       2549956.1     13459389.87
#Sta/Elev= 30
  2738.3  121.11    2839     116  2887.4  113.57  3018.3   109.8  3110.5  109.85
  3301.5  118.23  3359.7  119.26  3500.2  120.11  3676.3  118.51    3756  116.39
  3871.5  110.42  3897.6  109.02  3954.7  102.87  3997.5   99.75  4001.7      94
  5117.2      94  5124.8     100  5254.6  103.16  5309.2  105.61    5421  108.55
  5491.9  109.47  5578.3  109.91  5677.7  110.36  5873.2  111.94  6271.5  116.08
  6770.7  118.38  6781.3  118.48  6969.4   118.9  7068.8  118.41  7120.6  118.32
#Mann= 19 ,-1 , 0
  2738.3     .12       0    2839     .07       0  2887.4     .12       0
  3359.7     .07       0  3676.3     .12       0  3871.5    .033       0
  3997.5    .033       0  4001.7     .03       0  5124.8     .03       0
  5254.6     .12       0    5421     .07       0  5491.9     .12       0
  5578.3     .07       0  5677.7     .05       0  5873.2     .07       0
  6770.7     .12       0  6781.3     .07       0  6969.4     .05       0
  7068.8     .07       0
Bank Sta=3997.5,5124.8
XS Rating Curve= 0 ,0
Exp/Cntr=0.3,0.1

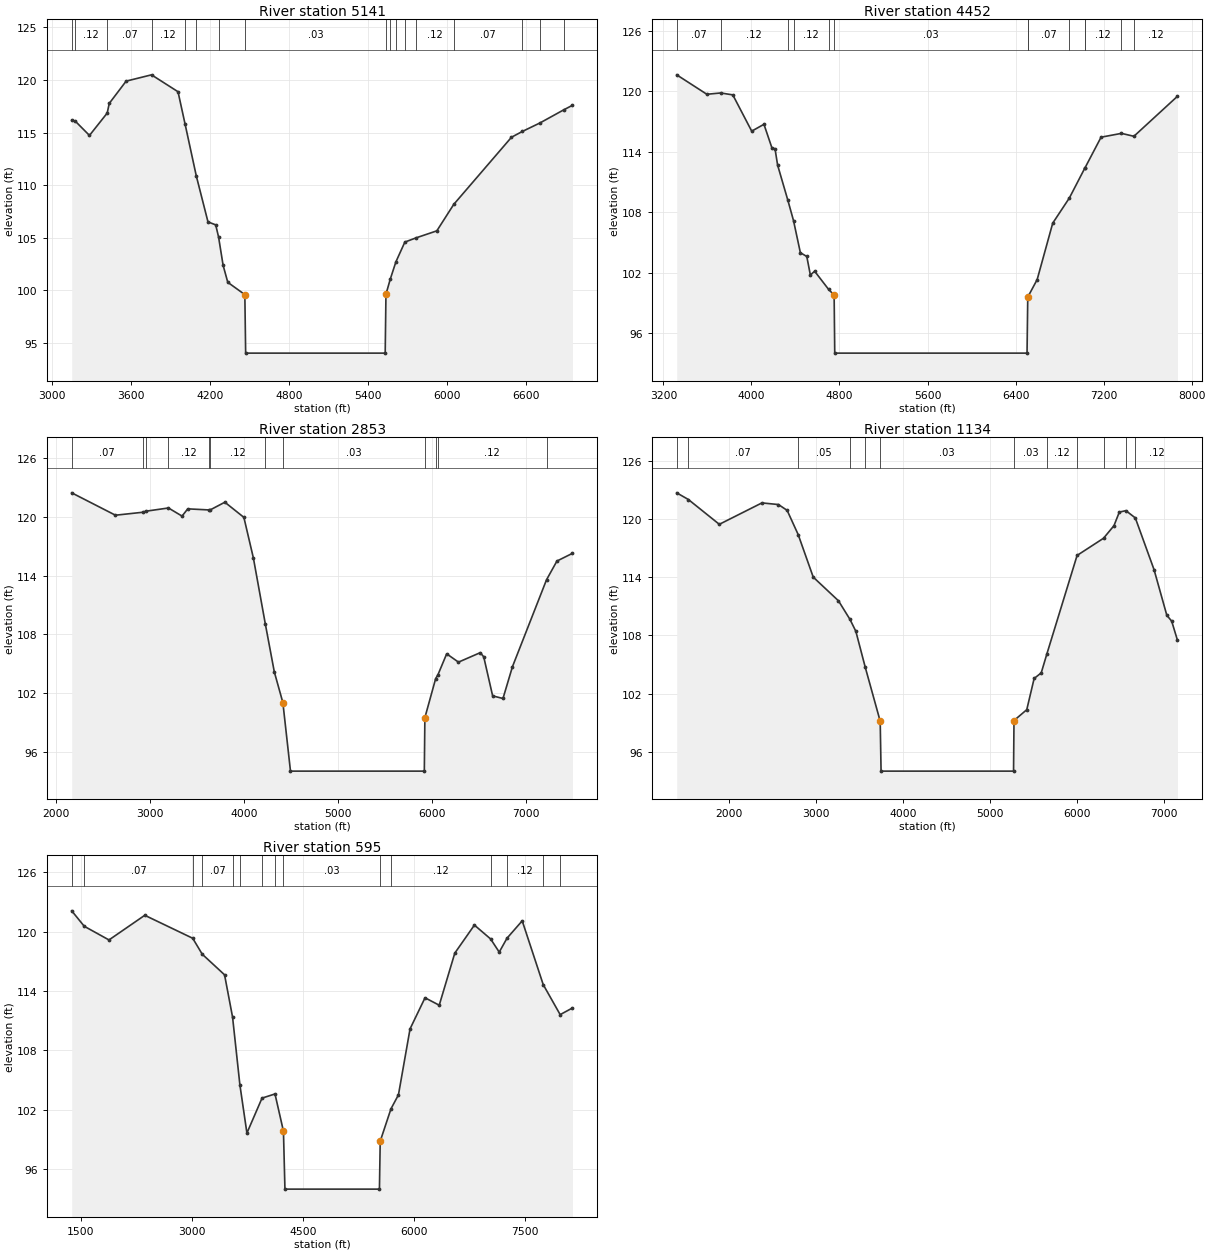
Type RM Length L Ch R = 1 ,5141    ,689,689,689
BEGIN DESCRIPTION:
Mapping XS 248201f8
END DESCRIPTION:
XS GIS Cut Line= 3
      2552169.65     13462618.97      2550997.76     13461017.39
      2550060.27      13459454.9
#Sta/Elev= 30
  3148.8  116.19    3176  116.08  3283.8  114.72  3418.7  116.85  3434.3  117.77
  3562.6  119.89  3755.5  120.49    3957  118.88  4010.9  115.79  4095.9  110.87
  4184.8  106.49  4243.4  106.21  4265.2  105.06  4299.8  102.36  4335.3  100.74
    4465   99.57  4471.2      94    5532      94  5537.8    99.6    5570  101.02
  5613.4  102.69  5681.4  104.57  5768.5  104.98  5924.6  105.64  6053.2  108.16
  6492.1  114.55  6574.5   115.1  6708.6  115.91  6891.1  117.17  6955.5  117.59
#Mann= 17 ,-1 , 0
  3148.8     .07       0    3176     .12       0  3418.7     .07       0
  3755.5     .12       0  4010.9     .07       0  4095.9     .12       0
  4265.2    .033       0    4465     .03       0  5537.8     .03       0
    5570     .07       0  5613.4     .12       0  5681.4     .07       0
  5768.5     .12       0  6053.2     .07       0  6574.5     .12       0
  6708.6     .07       0  6891.1     .05       0
Bank Sta=4465,5537.8
XS Rating Curve= 0 ,0
Exp/Cntr=0.3,0.1

Type RM Length L Ch R = 1 ,4452    ,1599,1599,1599
BEGIN DESCRIPTION:
TURKEY CREEK 4.0
END DESCRIPTION:
XS GIS Cut Line= 3
        2552375.       13462625.        2551725.       13461075.
      2549830.93     13458919.66
#Sta/Elev= 30
    3321  121.62    3595  119.69  3720.5  119.82  3830.7  119.63  4002.5  116.03
  4113.8  116.71  4185.2   114.4  4214.4  114.27  4238.1  112.65    4331  109.17
  4382.4  107.15  4444.6  103.97    4503  103.59  4535.5  101.75  4574.3  102.13
  4700.9  100.33  4751.5   99.76    4757      94  6504.3      94  6510.9   99.59
  6512.5   99.59  6596.3   101.3  6737.7   106.9    6889   109.4  7028.8  112.35
  7029.2  112.35    7177  115.43  7362.4  115.81  7475.4  115.52  7871.1  119.49
#Mann= 13 ,-1 , 0
    3321     .07       0  3720.5     .12       0    4331     .07       0
  4382.4     .12       0  4700.9    .033       0  4751.5     .03       0
  6510.9     .03       0  6512.5     .07       0    6889     .12       0
  7028.8     .07       0  7029.2     .12       0  7362.4     .07       0
  7475.4     .12       0
Bank Sta=4751.5,6510.9
XS Rating Curve= 0 ,0
Exp/Cntr=0.3,0.1

Type RM Length L Ch R = 1 ,2853    ,1719,1719,1719
BEGIN DESCRIPTION:
TURKEY CREEK 3.0
END DESCRIPTION:
XS GIS Cut Line= 3
        2552575.     13462824.97        2552175.       13460025.
      2550059.24     13458713.63
#Sta/Elev= 30
  2171.6  122.47  2636.2  120.18  2924.2  120.48  2959.4  120.59  3199.1  120.92
  3343.3  120.09    3404  120.83  3630.1  120.72  3635.8  120.69  3797.9  121.51
  3999.9  119.96    4101   115.8  4228.6  109.01  4323.2  104.15  4414.1  101.01
  4494.9      94  5916.2      94  5922.1   99.47  6036.8  103.47    6060  103.84
  6153.6     106  6278.9  105.15  6510.4  106.12  6547.1  105.69  6641.6   101.7
  6751.5  101.43  6851.9  104.68  7214.1  113.58  7324.4  115.49  7489.2  116.28
#Mann= 12 ,-1 , 0
  2171.6     .07       0  2924.2     .12       0  2959.4     .07       0
  3199.1     .12       0  3630.1     .07       0  3635.8     .12       0
  4228.6    .033       0  4414.1     .03       0  5922.1     .03       0
  6036.8     .07       0    6060     .12       0  7214.1     .07       0
Bank Sta=4414.1,5922.1
XS Rating Curve= 0 ,0
Exp/Cntr=0.3,0.1

Type RM Length L Ch R = 1 ,1134    ,539,539,539
BEGIN DESCRIPTION:
TURKEY CREEK 2.0
END DESCRIPTION:
XS GIS Cut Line= 3
        2552825.     13462774.99        2552825.       13459175.
      2550709.79     13458745.79
#Sta/Elev= 30
  1400.4  122.72  1534.6  122.03  1890.4  119.47  2380.4  121.68  2570.4  121.51
  2670.4  120.91  2797.3  118.41  2970.4  114.02  3260.4  111.58  3392.8  109.66
  3460.4  108.43  3568.8  104.71  3740.4   99.15  3750.4      94  5273.9      94
    5279   99.22  5425.8  100.34  5510.6  103.56  5592.2  104.14  5656.6  106.08
  6004.6  116.26  6308.3  118.03  6428.7  119.33  6490.1  120.73  6565.8  120.88
  6674.1  120.13  6889.6  114.79  7036.5  110.08  7092.2  109.48  7158.7  107.51
#Mann= 12 ,-1 , 0
  1400.4     .12       0  1534.6     .07       0  2797.3     .05       0
  3392.8     .07       0  3568.8    .033       0  3740.4     .03       0
    5279     .03       0  5656.6     .12       0  6004.6     .07       0
  6308.3     .12       0  6565.8     .07       0  6674.1     .12       0
Bank Sta=3740.4,5279
XS Rating Curve= 0 ,0
Exp/Cntr=0.3,0.1

Type RM Length L Ch R = 1 ,595     ,0,0,0
BEGIN DESCRIPTION:
TURKEY CREEK 1.0
END DESCRIPTION:
XS GIS Cut Line= 5
        2552925.     13462675.04      2553254.35     13459710.88
        2553325.       13459075.      2552677.62     13458845.21
      2550309.08     13458225.17
#Sta/Elev= 30
  1377.9   122.1  1547.4  120.54    1881  119.16    2364  121.65  3010.9  119.33
  3139.5  117.72  3440.6  115.64  3548.7  111.37  3647.7  104.52  3742.4   99.66
  3946.3  103.19  4121.2  103.61  4235.4   99.85  4255.5      94  5530.7      94
  5541.3   98.84  5686.5  102.11  5787.3  103.52  5943.8  110.18  6145.9  113.32
  6337.6  112.57  6547.7  117.83  6812.3  120.66  7031.1  119.26  7147.3  117.93
  7251.7  119.33  7457.4  121.09  7740.9  114.65  7969.6  111.62  8135.4  112.29
#Mann= 15 ,-1 , 0
  1377.9     .12       0  1547.4     .07       0  3010.9     .05       0
  3139.5     .07       0  3548.7     .12       0  3647.7    .033       0
  3946.3     .12       0  4121.2    .033       0  4235.4     .03       0
  5541.3     .03       0  5686.5     .12       0  7031.1     .07       0
  7251.7     .12       0  7740.9     .07       0  7969.6      .1       0
Bank Sta=4235.4,5541.3
XS Rating Curve= 0 ,0
Exp/Cntr=0.3,0.1

Chan Stop Cuts=-1
Use User Specified Reach Order=0
Composite Channel Slope=5