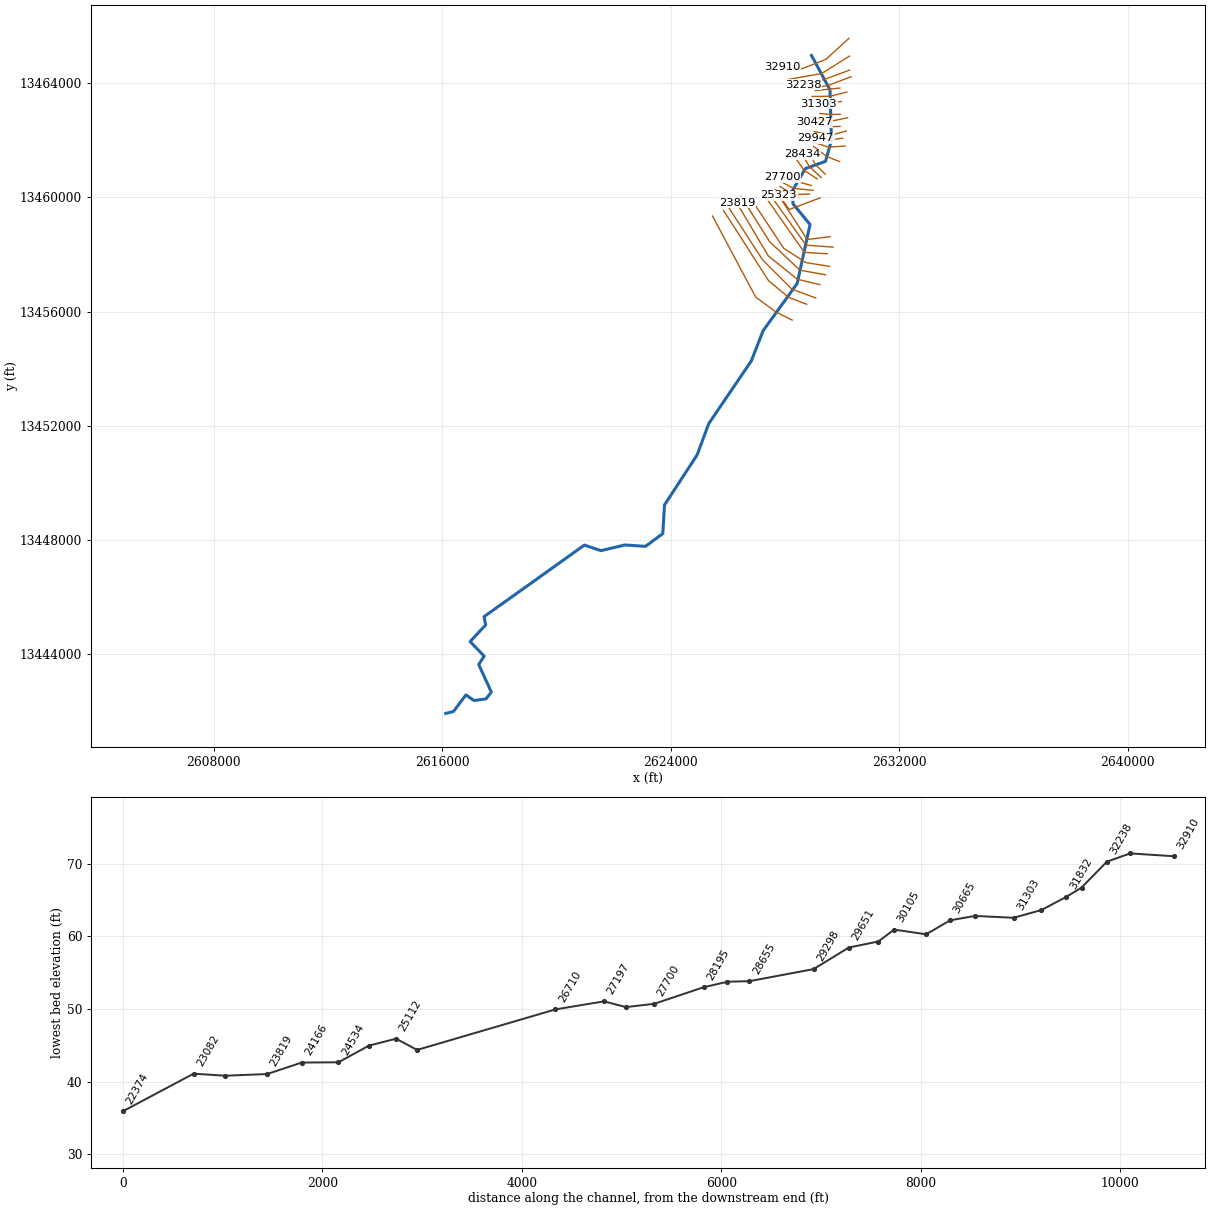
--- CRESECENT VALLEY CREEK.prj (project) ---

Proj Title=CRESECENT VALLEY CREEK Base Level Engineering
Current Plan=p01
Default Exp/Contr=0.3,0.1
English Units
Geom File=g01
Flow File=f01
Plan File=p01
Y Axis Title=Elevation
X Axis Title(PF)=Main Channel Distance
X Axis Title(XS)=Station
BEGIN DESCRIPTION:
CRESECENT VALLEY CREEK
END DESCRIPTION:
DSS Export Rating Curves= 0
DSS Export Rating Curve Sorted= 0
DSS Export Volume Flow Curves= 0
DXF OffsetX= 0
DXF OffsetY= 0
DXF ScaleX= 1
DXF ScaleY= 10

--- CRESECENT VALLEY CREEK.p01 (plan) ---

Plan Title=Multiple Run
Short Identifier=Multiple
Geom File=g01
Flow File=f01
Subcritical Flow
K Sum by GR= 0
Std Step Tol= 0.01
Critical Tol= 0.01
Num of Std Step Trials= 20
Max Error Tol= 0.3
Flow Tol Ratio= 0.001
Split Flow NTrial= 30
Split Flow Tol= 0.02
Split Flow Ratio= 0.02
Log Output Level= 0
Friction Slope Method= 1
Unsteady Friction Slope Method= 2
Unsteady Bridges Friction Slope Method= 1
Parabolic Critical Depth
Global Vel Dist=  1 , 1 , 1
Global Log Level= 0
CheckData=True
Encroach Param= -1, 0, 0, 0
BEGIN DESCRIPTION:
Multiple Run
END DESCRIPTION:

--- CRESECENT VALLEY CREEK.f01 (steady flow) ---

Flow Title=Multiple
Program Version=4.10
Number of Profiles= 7
Profile Names=10-year,25-year,50-year,1pct_min,100-year,1pct_plu,500-year
River Rch & RM=CRESECENT VALLEY,Reach-1         ,32910
     386     570     721     440     879    1753    1289
River Rch & RM=CRESECENT VALLEY,Reach-1         ,32472
     504     760     975     605    1207    2407    1824
River Rch & RM=CRESECENT VALLEY,Reach-1         ,30914
     744    1153    1507     951    1897    3784    2970
River Rch & RM=CRESECENT VALLEY,Reach-1         ,27700
    1273    2033    2709    1741    3473    6929    5645
River Rch & RM=CRESECENT VALLEY,Reach-1         ,22374
    1411    2265    3029    1953    3896    7774    6376
River Rch & RM=CRESECENT VALLEY,Reach-1         ,19082
    1636    2638    3541    2289    4568    9114    7518
River Rch & RM=CRESECENT VALLEY,Reach-1         ,17394
    1703    2752    3698    2394    4776    9529    7878
River Rch & RM=CRESECENT VALLEY,Reach-1         ,16388
    2147    3505    4744    3090    6164   12300   10298
River Rch & RM=CRESECENT VALLEY,Reach-1         ,12976
    2195    3587    4856    3165    6314   12599   10560
River Rch & RM=CRESECENT VALLEY,Reach-1         ,8745
    2347    3843    5209    3398    6780   13528   11361
River Rch & RM=CRESECENT VALLEY,Reach-1         ,7513
    2422    3959    5361    3492    6967   13902   11643
Boundary for River Rch & Prof#=CRESECENT VALLEY,Reach-1         , 1
Up Type= 0
Dn Type= 3
Dn Slope=0.005
Boundary for River Rch & Prof#=CRESECENT VALLEY,Reach-1         , 2
Up Type= 0
Dn Type= 3
Dn Slope=0.005
Boundary for River Rch & Prof#=CRESECENT VALLEY,Reach-1         , 3
Up Type= 0
Dn Type= 3
Dn Slope=0.005
Boundary for River Rch & Prof#=CRESECENT VALLEY,Reach-1         , 4
Up Type= 0
Dn Type= 3
Dn Slope=0.005
Boundary for River Rch & Prof#=CRESECENT VALLEY,Reach-1         , 5
Up Type= 0
Dn Type= 3
Dn Slope=0.005
Boundary for River Rch & Prof#=CRESECENT VALLEY,Reach-1         , 6
Up Type= 0
Dn Type= 3
Dn Slope=0.005
Boundary for River Rch & Prof#=CRESECENT VALLEY,Reach-1         , 7
Up Type= 0
Dn Type= 3
Dn Slope=0.005
DSS Import GetInterval= 0
DSS Import GetPeak= 0
DSS Import FillOption= 0

--- CRESECENT VALLEY CREEK.g01 (geometry) ---

Geom Title=Existing Conditions
Program Version=4.10

River Reach=CRESECENT VALLEY,Reach-1
Reach XY= 30
        2628925.       13464975.      2629572.76     13463769.07
      2629624.94     13461995.03      2629414.24     13461264.58
      2628708.32     13461008.36      2628277.06     13460269.15
      2628278.54     13459776.46       2628875.2     13459050.08
      2628422.93     13456980.86      2627230.85     13455327.29
      2626819.46     13454272.58      2625330.84     13452077.29
      2624919.48     13450972.57      2623780.47     13449227.45
      2623719.17      13448222.7      2623114.32     13447775.75
      2622390.22     13447824.48      2621554.85     13447624.64
      2620976.58     13447821.33      2617461.43     13445311.51
      2617520.06     13445023.05      2616975.01     13444440.42
      2617466.16     13443931.95      2617276.08     13443635.55
      2617717.23     13442671.59      2617532.01     13442434.03
      2617109.58     13442375.03      2616826.65      13442571.9
      2616391.75     13441991.22        2616125.       13441925.

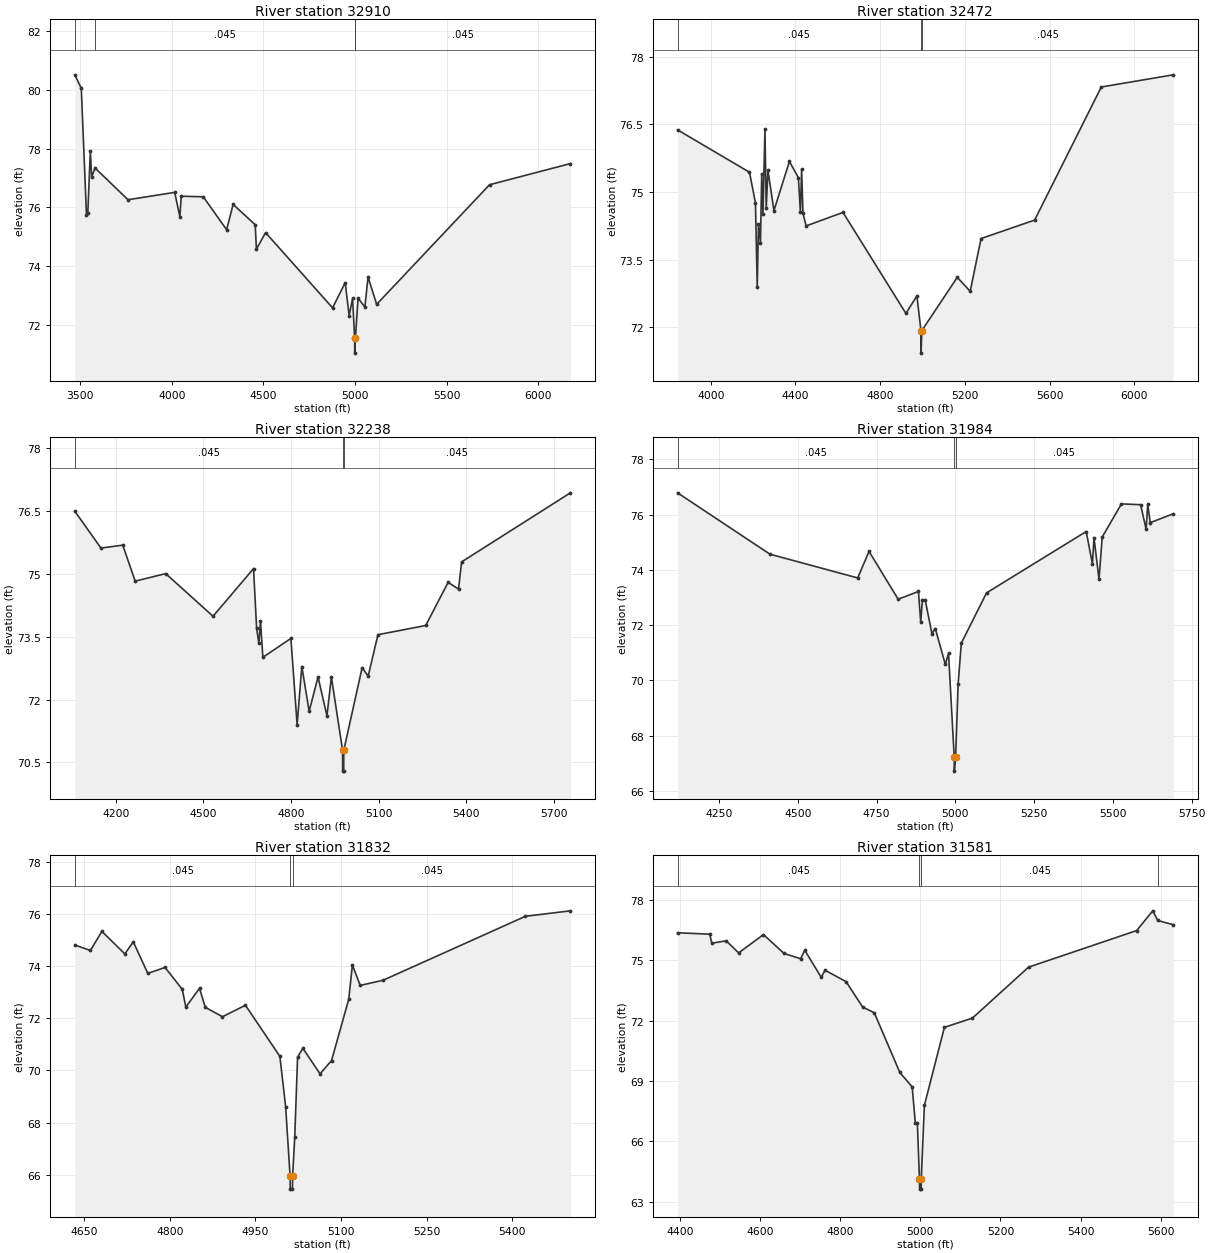
Type RM Length L Ch R = 1 ,32910   ,438,438,438
BEGIN DESCRIPTION:
CRESECENT VALLEY CREEK 50.0
END DESCRIPTION:
XS GIS Cut Line= 4
      2630237.45     13465572.51      2629420.14     13464828.82
       2628567.9     13464499.39      2627885.09     13464552.58
#Sta/Elev= 30
  3471.3   80.51  3506.6   80.05    3535   75.73  3542.2   75.81  3555.9   77.92
  3563.3   77.03  3581.7   77.34  3761.3   76.26  4016.1   76.51  4044.4   75.68
  4051.9   76.38  4172.1   76.36  4299.3   75.24    4335    76.1  4455.3   75.41
    4462   74.58    4512   75.14  4877.4   72.58  4946.4   73.44  4967.8   72.32
  4986.5    72.9    4998   71.54  4998.2   71.04    5002   71.54  5016.4   72.91
  5053.6   72.61    5071   73.63  5117.9    72.7  5733.7   76.77  6174.9   77.49
#Mann= 4 ,-1 , 0
  3471.3    .063       0  3581.7    .045       0    4998    .045       0
    5002    .045       0
Bank Sta=4998,5002
XS Rating Curve= 0 ,0
Exp/Cntr=0.3,0.1

Type RM Length L Ch R = 1 ,32472   ,234,234,234
BEGIN DESCRIPTION:
Mapping XS 2bf33b24
END DESCRIPTION:
XS GIS Cut Line= 3
      2630256.65     13464951.37      2629277.48     13464336.79
       2628110.8     13464133.66
#Sta/Elev= 30
    3843   76.38  4182.8   75.44    4211   74.76  4219.3    72.9  4225.2    74.3
  4234.6   73.87  4240.5    75.4  4246.4   74.52  4255.8    76.4  4261.7   74.65
    4270   75.48  4298.3   74.59  4371.3   75.68  4413.7   75.32  4423.1   74.56
    4429   75.51  4435.3   74.53  4450.3   74.25  4624.2   74.55  4921.5   72.31
  4973.3    72.7  4992.5   71.93  4992.8   71.43  4996.7   71.93    5164   73.11
  5224.9    72.8  5276.3   73.97  5529.4   74.38  5844.1   77.33  6183.3    77.6
#Mann= 3 ,-1 , 0
    3843    .045       0  4992.5    .045       0  4996.7    .045       0
Bank Sta=4992.5,4996.7
XS Rating Curve= 0 ,0
Exp/Cntr=0.3,0.1

Type RM Length L Ch R = 1 ,32238   ,254,254,254
BEGIN DESCRIPTION:
Mapping XS 45943ac3
END DESCRIPTION:
XS GIS Cut Line= 3
      2630258.85     13464458.67      2629375.21     13464133.02
      2628644.27     13463946.52
#Sta/Elev= 30
  4060.1    76.5  4149.5   75.62  4224.1   75.69  4266.7   74.83  4371.2   75.01
  4533.1   73.99  4671.7   75.13  4682.3    73.7  4690.1   73.34  4695.4   73.88
  4703.7   73.01  4799.6   73.46  4820.9    71.4    4837   72.79  4862.1   71.72
  4892.5   72.54    4923   71.61  4938.1   72.54  4976.4   70.79  4976.7   70.29
  4980.4   70.29  4980.6   70.79  5043.3   72.76    5064   72.56  5097.5   73.55
    5261   73.77  5337.6    74.8  5373.3   74.64  5383.9   75.29  5756.2   76.94
#Mann= 3 ,-1 , 0
  4060.1    .045       0  4976.4    .045       0  4980.6    .045       0
Bank Sta=4976.4,4980.6
XS Rating Curve= 0 ,0
Exp/Cntr=0.3,0.1

Type RM Length L Ch R = 1 ,31984   ,152,152,152
BEGIN DESCRIPTION:
Mapping XS 2881cd74
END DESCRIPTION:
XS GIS Cut Line= 3
      2630308.76     13464227.42      2629522.27     13463925.33
      2628803.48     13463795.11
#Sta/Elev= 30
  4118.2   76.79  4411.5   74.57    4690   73.71    4726   74.67  4818.5   72.94
  4882.8   73.22    4890   72.12  4895.4    72.9  4904.2   72.92  4925.7   71.69
  4936.4   71.88  4968.1   70.58  4978.3   70.98  4996.4   67.22  4996.7   66.72
  5000.8   67.22  5008.8   69.87  5018.9   71.35    5099   73.17  5415.3   75.39
    5435   74.22    5440   75.17  5455.9   73.66  5466.1   75.19  5527.1   76.39
    5588   76.36  5605.5   75.47  5610.6   76.38  5618.5   75.71  5691.2   76.03
#Mann= 3 ,-1 , 0
  4118.2    .045       0  4996.4    .045       0  5000.8    .045       0
Bank Sta=4996.4,5000.8
XS Rating Curve= 0 ,0
Exp/Cntr=0.3,0.1

Type RM Length L Ch R = 1 ,31832   ,251,251,251
BEGIN DESCRIPTION:
Mapping XS 2d243fee
END DESCRIPTION:
XS GIS Cut Line= 3
       2629922.1     13463830.93      2629583.54     13463794.48
      2629058.72     13463742.51
#Sta/Elev= 30
  4633.7   74.81    4661    74.6  4681.1   75.33  4721.3   74.47  4736.1   74.93
  4761.5   73.72  4791.7   73.95  4821.9   73.11  4828.1   72.43  4852.1   73.15
  4862.1   72.42  4892.3   72.06  4932.5    72.5  4992.8   70.54  5002.9   68.61
  5010.7   65.95    5011   65.45  5014.8   65.45  5015.1   65.95  5018.8   67.43
  5023.8   70.51    5033   70.85  5063.2   69.87  5083.3   70.38  5113.4   72.73
  5119.8   74.04  5133.5   73.26  5173.7   73.46  5422.8   75.91  5501.6   76.12
#Mann= 3 ,-1 , 0
  4633.7    .045       0  5010.7    .045       0  5015.1    .045       0
Bank Sta=5010.7,5015.1
XS Rating Curve= 0 ,0
Exp/Cntr=0.3,0.1

Type RM Length L Ch R = 1 ,31581   ,278,278,278
BEGIN DESCRIPTION:
Mapping XS e5469b98
END DESCRIPTION:
XS GIS Cut Line= 3
      2630162.94     13463690.97      2629584.77     13463545.12
      2628944.14      13463534.7
#Sta/Elev= 30
  4394.2   76.37  4474.6    76.3  4479.8   75.85  4515.7   75.97  4546.8   75.37
  4608.7   76.28  4660.2   75.34  4701.5   75.08  4711.8    75.5    4753   74.15
  4762.2   74.51  4814.9   73.94  4856.2   72.68  4885.4   72.39    4949   69.43
  4979.9   68.71  4987.8    66.9  4992.9    66.9    4998   64.13  4998.4   63.63
  5002.2   63.63  5002.5   64.13  5010.3   67.79  5060.3   71.67  5130.3   72.13
  5270.3   74.66  5540.3   76.48  5580.3   77.46  5592.8   76.98  5631.2   76.77
#Mann= 4 ,-1 , 0
  4394.2    .045       0    4998    .045       0  5002.5    .045       0
  5592.8     .05       0
Bank Sta=4998,5002.5
XS Rating Curve= 0 ,0
Exp/Cntr=0.3,0.1

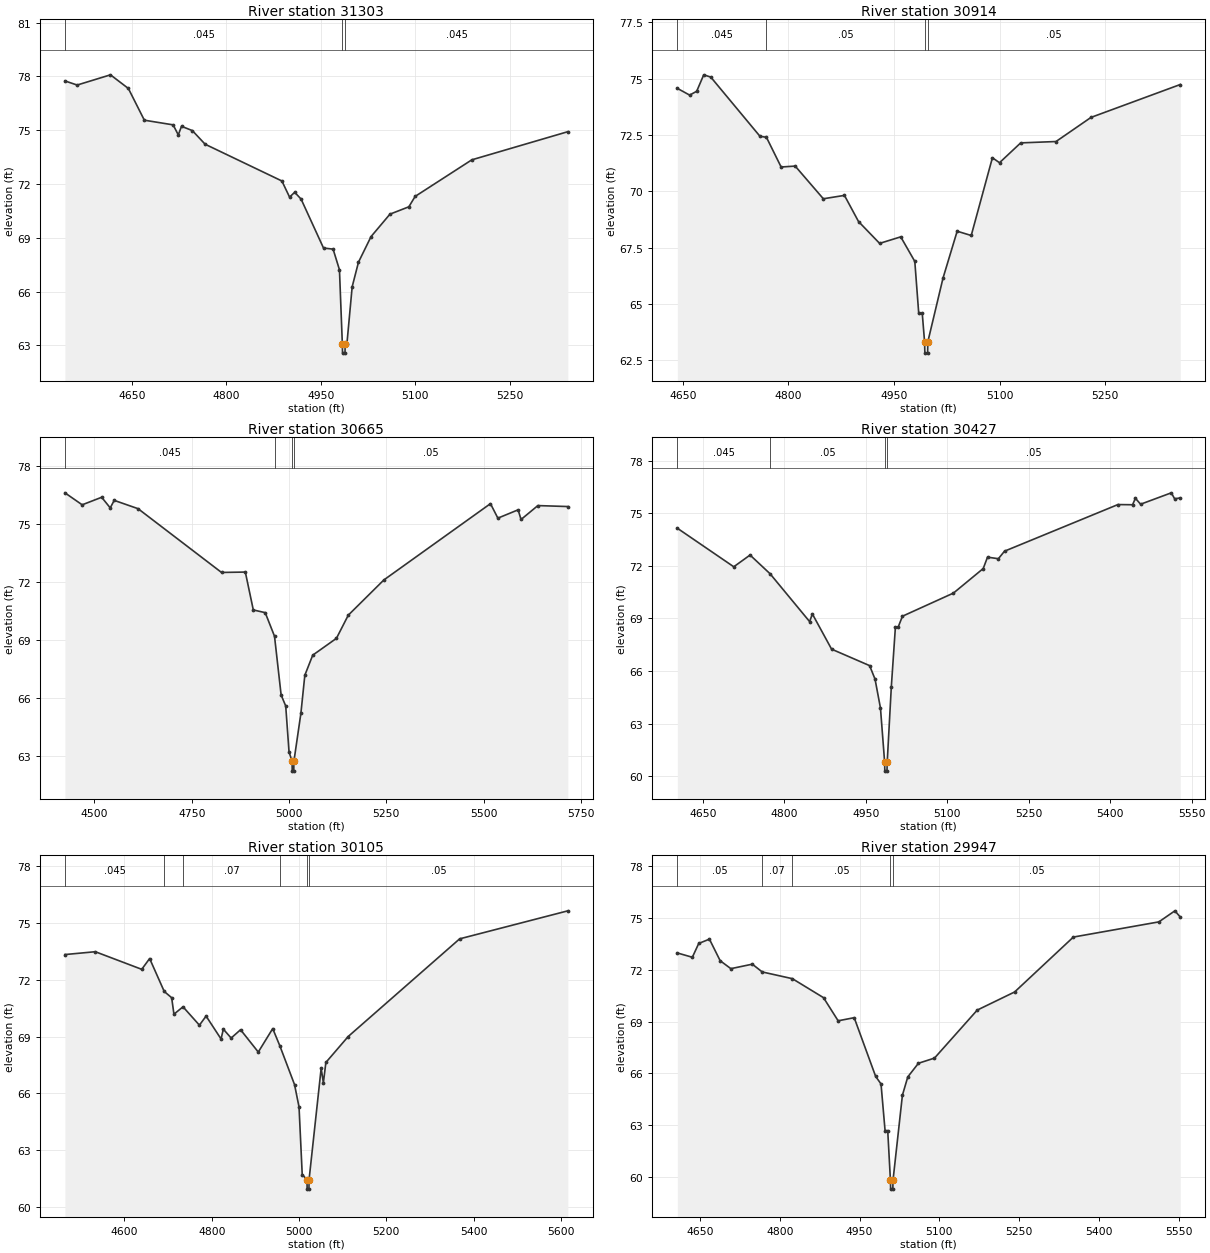
Type RM Length L Ch R = 1 ,31303   ,389,389,389
BEGIN DESCRIPTION:
Mapping XS 3b55a758
END DESCRIPTION:
XS GIS Cut Line= 3
      2629974.14     13463362.18      2629536.67     13463284.06
      2629182.46     13463284.06
#Sta/Elev= 30
  4543.9   77.75  4563.3   77.52  4616.2   78.09  4644.6   77.33    4670   75.56
  4715.7    75.3  4723.9   74.74    4729   75.22  4746.2   74.98  4766.5   74.22
  4888.4   72.17  4900.6   71.27  4908.7   71.54  4918.9   71.16  4954.5   68.43
  4969.7   68.37  4979.8   67.22  4984.4   63.07  4984.7   62.57  4988.6   62.57
  4988.9   63.07  4991.6   63.07    5000   66.27    5010   67.64    5030   69.07
    5060   70.32    5090   70.73    5100   71.31    5190   73.35  5342.5   74.92
#Mann= 3 ,-1 , 0
  4543.9    .045       0  4984.4    .045       0  4988.9    .045       0
Bank Sta=4984.4,4988.9
XS Rating Curve= 0 ,0
Exp/Cntr=0.3,0.1

Type RM Length L Ch R = 1 ,30914   ,249,249,249
BEGIN DESCRIPTION:
Mapping XS 83c3fd2c
END DESCRIPTION:
XS GIS Cut Line= 3
      2629932.47     13462909.06      2629588.75     13462909.06
      2629218.99     13462940.31
#Sta/Elev= 30
  4642.1   74.57  4659.6   74.27  4669.6   74.44  4679.6   75.17  4689.6   75.07
  4759.6   72.44  4768.7    72.4  4789.6   71.08  4809.6   71.12  4849.6   69.67
  4879.6   69.82  4899.6   68.66  4929.6   67.69  4959.6   67.98  4979.6   66.89
  4985.2   64.58  4990.2   64.58  4993.5   63.32  4993.9   62.82  4997.8   62.82
  4998.1   63.32  5019.7   66.15  5039.8   68.23  5059.8   68.04  5089.9   71.49
    5100   71.27  5130.1   72.15  5180.3   72.21    5230   73.28  5356.9   74.74
#Mann= 4 ,-1 , 0
  4642.1    .045       0  4768.7     .05       0  4993.5     .05       0
  4998.1     .05       0
Bank Sta=4993.5,4998.1
XS Rating Curve= 0 ,0
Exp/Cntr=0.3,0.1

Type RM Length L Ch R = 1 ,30665   ,238,238,238
BEGIN DESCRIPTION:
Mapping XS c2aa6461
END DESCRIPTION:
XS GIS Cut Line= 3
      2630188.96     13462789.92      2629636.86     13462675.33
        2628919.     13462800.17
#Sta/Elev= 30
  4424.2   76.61  4468.5   75.99  4518.6   76.38  4540.6   75.83  4550.8   76.22
  4612.1   75.79  4826.6   72.49  4887.8   72.51  4908.3   70.55  4938.9   70.41
  4962.8   69.19  4979.8   66.15  4991.6   65.58  5000.1   63.21    5008   62.71
  5008.3   62.21  5012.3   62.21  5012.6   62.71  5030.6    65.2  5040.7   67.17
    5061   68.21  5121.9   69.08  5152.4   70.28  5243.7    72.1  5517.8   76.05
  5536.8    75.3  5588.8   75.73  5596.4   75.23  5639.6   75.95  5716.7    75.9
#Mann= 4 ,-1 , 0
  4424.2    .045       0  4962.8     .05       0    5008     .05       0
  5012.6     .05       0
Bank Sta=5008,5012.6
XS Rating Curve= 0 ,0
Exp/Cntr=0.3,0.1

Type RM Length L Ch R = 1 ,30427   ,322,322,322
BEGIN DESCRIPTION:
CRESECENT VALLEY CREEK 45.0
END DESCRIPTION:
XS GIS Cut Line= 3
      2629928.82     13462487.96        2629525.       13462475.
      2629025.04     13462624.99
#Sta/Elev= 30
  4603.3   74.15  4707.2   71.95  4737.2   72.62  4774.1   71.55  4846.9   68.82
  4851.9   69.26  4887.3   67.25  4957.3   66.31  4967.3   65.54  4977.3   63.89
    4985   60.79  4985.3   60.29  4989.3   60.29  4989.7   60.79  4997.3   65.11
  5004.8   68.51  5009.9   68.51  5017.8   69.13  5111.7   70.45  5166.5   71.85
  5174.4    72.5  5194.4   72.41  5205.7   72.84  5414.5    75.5  5441.5   75.49
  5446.7   75.86  5456.3   75.52  5512.8   76.17  5518.9   75.83  5529.3   75.88
#Mann= 4 ,-1 , 0
  4603.3    .045       0  4774.1     .05       0    4985     .05       0
  4989.7     .05       0
Bank Sta=4985,4989.7
XS Rating Curve= 0 ,0
Exp/Cntr=0.3,0.1

Type RM Length L Ch R = 1 ,30105   ,158,158,158
BEGIN DESCRIPTION:
Mapping XS c39d609e
END DESCRIPTION:
XS GIS Cut Line= 3
      2630142.04     13462326.36      2629616.02     13462180.54
      2629022.29     13462305.53
#Sta/Elev= 30
  4463.5   73.33  4533.1   73.48  4639.5   72.55  4657.6   73.12  4691.1   71.38
  4708.1   71.05  4713.3   70.18  4734.1   70.57  4771.7    69.6    4787   70.08
  4821.3   68.87  4826.5   69.39  4844.4   68.92    4866   69.36  4906.6   68.18
  4939.7   69.42    4956   68.51  4989.7   66.46    5000   65.28  5007.3   61.71
  5018.2   61.44  5018.6   60.94  5022.7   60.94    5023   61.44  5050.7   67.32
  5055.8   66.56  5061.5   67.63  5112.6      69  5368.1   74.16  5616.1   75.64
#Mann= 6 ,-1 , 0
  4463.5    .045       0  4691.1     .05       0  4734.1     .07       0
    4956     .05       0  5018.2     .05       0    5023     .05       0
Bank Sta=5018.2,5023
XS Rating Curve= 0 ,0
Exp/Cntr=0.3,0.1

Type RM Length L Ch R = 1 ,29947   ,296,296,296
BEGIN DESCRIPTION:
CRESECENT VALLEY CREEK 44.0
END DESCRIPTION:
XS GIS Cut Line= 3
      2630014.84     13462073.91        2629625.       13462025.
      2629074.96       13462075.
#Sta/Elev= 30
  4607.5   72.98  4635.7   72.73  4647.7   73.53  4667.8   73.78    4688   72.53
  4708.1   72.07  4748.4   72.33    4767   71.88  4823.7   71.49  4882.2   70.39
  4909.7   69.05  4939.9   69.23  4980.2   65.83  4990.3   65.39  4997.9   62.69
  5002.9   62.69    5008    59.8  5008.4    59.3  5012.5    59.3  5012.8    59.8
  5030.5   64.74  5040.6    65.8  5060.6   66.59  5090.8   66.89  5171.1   69.67
  5241.4   70.72  5351.8    73.9  5512.5   74.78  5542.6   75.42  5552.7   75.06
#Mann= 5 ,-1 , 0
  4607.5     .05       0    4767     .07       0  4823.7     .05       0
    5008     .05       0  5012.8     .05       0
Bank Sta=5008,5012.8
XS Rating Curve= 0 ,0
Exp/Cntr=0.3,0.1

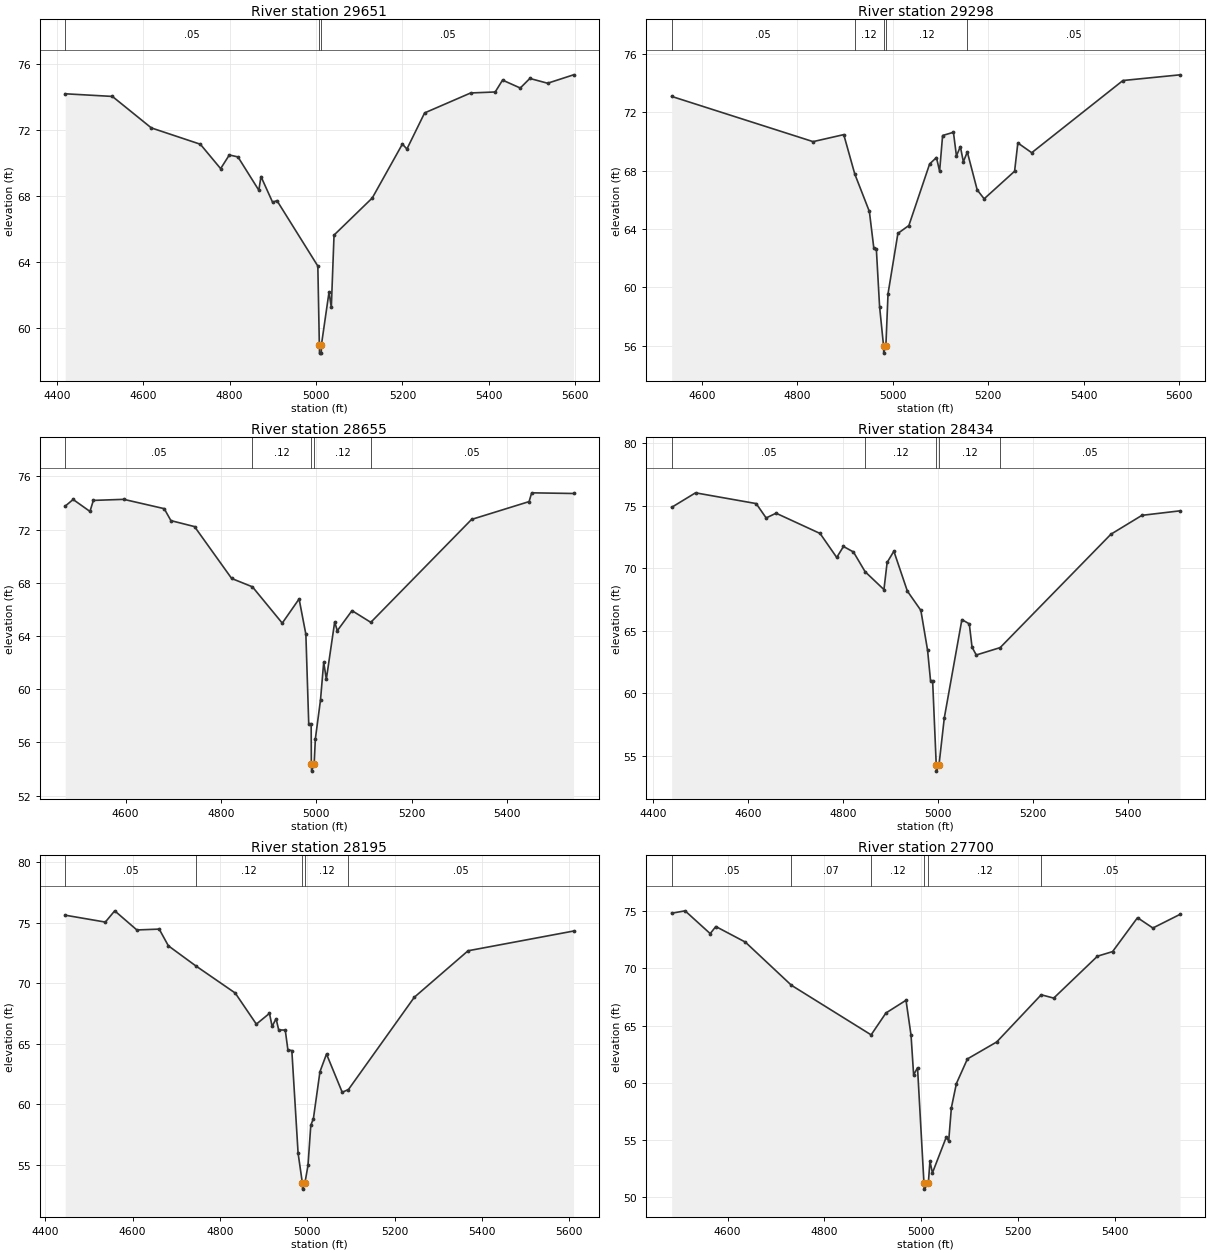
Type RM Length L Ch R = 1 ,29651   ,353,353,353
BEGIN DESCRIPTION:
Mapping XS a9c4ba79
END DESCRIPTION:
XS GIS Cut Line= 3
      2630103.92     13461802.15      2629520.64     13461760.49
      2628959.08     13461947.67
#Sta/Elev= 30
  4419.3    74.2  4528.5   74.04  4618.7   72.13  4732.1   71.14  4779.1   69.66
  4799.2   70.49  4819.2   70.37  4867.5   68.35  4872.5   69.18  4899.4   67.62
  4909.5   67.72  5004.1   63.75  5007.6   58.97    5008   58.47  5012.1   58.47
  5012.4   58.97    5030   62.17  5035.3   61.24  5041.6   65.63  5130.1   67.88
  5199.8   71.15  5210.3   70.85  5251.3   73.04  5357.9   74.25  5414.7   74.31
  5431.7   75.03  5472.7   74.55  5494.9   75.13    5536   74.84    5596   75.35
#Mann= 3 ,-1 , 0
  4419.3     .05       0  5007.6     .05       0  5012.4     .05       0
Bank Sta=5007.6,5012.4
XS Rating Curve= 0 ,0
Exp/Cntr=0.3,0.1

Type RM Length L Ch R = 1 ,29298   ,643,643,643
BEGIN DESCRIPTION:
Mapping XS 2eae4bc8
END DESCRIPTION:
XS GIS Cut Line= 3
      2629911.29     13461255.27      2629468.55     13461427.15
      2628999.88     13461786.47
#Sta/Elev= 30
  4536.4    73.1  4832.8      70  4897.1   70.48  4920.2   67.78  4950.8   65.21
    4960   62.73  4965.4   62.65  4972.2   58.69  4980.5      56  4980.9    55.5
  4985.4      56  4989.9   59.57  5010.6   63.71  5033.6   64.25  5077.1   68.47
  5091.4   68.91    5098   67.97  5104.3   70.42    5127   70.64  5133.3   69.02
  5141.5   69.66  5147.8   68.62  5156.1   69.29  5176.8   66.69  5191.4   66.08
  5255.2   67.97    5262   69.91  5291.1   69.24  5482.3   74.19  5601.9   74.58
#Mann= 5 ,-1 , 0
  4536.4     .05       0  4920.2     .12       0  4980.5     .05       0
  4985.4     .12       0  5156.1     .05       0
Bank Sta=4980.5,4985.4
XS Rating Curve= 0 ,0
Exp/Cntr=0.3,0.1

Type RM Length L Ch R = 1 ,28655   ,221,221,221
BEGIN DESCRIPTION:
Mapping XS eb171b99
END DESCRIPTION:
XS GIS Cut Line= 3
      2629406.04     13460812.58      2629041.47     13461177.15
       2628812.3     13461677.16
#Sta/Elev= 30
  4473.4   73.77    4490   74.27  4525.3   73.37  4532.4    74.2  4596.1   74.28
  4680.9   73.58    4695   72.68  4744.5   72.23  4822.3   68.33  4865.9    67.7
  4928.4   64.97  4963.7   66.79  4977.9   64.13  4983.9    57.4    4989    57.4
  4989.4   54.34  4989.9   53.84  4995.2   54.34  4997.8   56.27  5008.6    59.2
  5015.3   62.04  5020.8   60.75  5038.3   65.06  5043.8    64.4  5074.6   65.91
    5114   65.03  5325.3   72.77  5445.8   74.11  5451.3   74.77    5539   74.72
#Mann= 5 ,-1 , 0
  4473.4     .05       0  4865.9     .12       0  4989.4     .05       0
  4995.2     .12       0    5114     .05       0
Bank Sta=4989.4,4995.2
XS Rating Curve= 0 ,0
Exp/Cntr=0.3,0.1

Type RM Length L Ch R = 1 ,28434   ,239,239,239
BEGIN DESCRIPTION:
Mapping XS 528a40d5
END DESCRIPTION:
XS GIS Cut Line= 3
       2629267.1     13460696.13      2628860.81     13461065.95
      2628595.16     13461513.91
#Sta/Elev= 30
  4439.5   74.86  4489.7   76.02  4617.4   75.16  4638.4   74.01  4659.3   74.39
  4751.9   72.77    4787   70.85  4801.2   71.73  4822.2   71.29  4846.8   69.71
  4886.4   68.28  4893.1   70.45  4907.3   71.35  4935.7   68.16  4964.1   66.62
  4978.3   63.42  4984.5   60.99  4988.9   60.99  4996.5   54.26    4997   53.76
  5002.3   54.26  5013.5   58.02  5050.5   65.88  5066.1   65.54  5071.9   63.67
  5080.8   63.05  5131.1   63.64  5364.3   72.71  5429.6   74.22  5509.7   74.58
#Mann= 5 ,-1 , 0
  4439.5     .05       0  4846.8     .12       0  4996.5     .05       0
  5002.3     .12       0  5131.1     .05       0
Bank Sta=4996.5,5002.3
XS Rating Curve= 0 ,0
Exp/Cntr=0.3,0.1

Type RM Length L Ch R = 1 ,28195   ,495,495,495
BEGIN DESCRIPTION:
Mapping XS f86c9822
END DESCRIPTION:
XS GIS Cut Line= 3
      2629119.56     13460651.14      2628656.05      13460958.4
      2628317.48     13461463.65
#Sta/Elev= 30
  4445.5   75.63  4537.4   75.06  4558.9   75.99  4609.6   74.41  4660.8   74.48
  4681.8    73.1  4744.7   71.44  4834.9    69.2  4883.3   66.63  4913.4   67.52
  4919.4   66.44  4928.5   67.08  4934.5   66.15  4949.5   66.14  4955.5   64.52
  4964.6   64.44  4978.9   55.98  4988.7    53.5  4989.2      53  4994.5    53.5
  5001.6   54.96    5008   58.27    5014   58.83    5029    62.7    5044   64.16
    5080      61  5094.3   61.23  5245.1   68.85  5368.2   72.69  5609.8   74.32
#Mann= 5 ,-1 , 0
  4445.5     .05       0  4744.7     .12       0  4988.7     .05       0
  4994.5     .12       0  5094.3     .05       0
Bank Sta=4988.7,4994.5
XS Rating Curve= 0 ,0
Exp/Cntr=0.3,0.1

Type RM Length L Ch R = 1 ,27700   ,284,284,284
BEGIN DESCRIPTION:
Mapping XS 7704601b
END DESCRIPTION:
XS GIS Cut Line= 3
      2628921.71     13460416.73      2628432.09     13460552.15
      2627911.26      13460703.2
#Sta/Elev= 30
  4484.6   74.81  4512.3   75.02  4564.2   73.03  4575.8   73.65  4636.8   72.29
    4732   68.52  4896.7   64.19  4927.3    66.1  4968.8   67.21  4979.2   64.15
  4984.5    60.7  4992.6   61.32  5005.9   51.22  5006.4   50.72  5014.9   51.22
  5018.2   53.15  5023.4   52.14  5051.8   55.24    5057   54.93  5062.5   57.82
  5072.9   59.94  5095.7   62.09  5156.2   63.57  5248.1   67.69    5274    67.4
  5364.4   71.06  5395.6   71.46  5447.1   74.42  5478.9   73.52  5534.9   74.71
#Mann= 6 ,-1 , 0
  4484.6     .05       0    4732     .07       0  4896.7     .12       0
  5005.9     .05       0  5014.9     .12       0  5248.1     .05       0
Bank Sta=5005.9,5014.9
XS Rating Curve= 0 ,0
Exp/Cntr=0.3,0.1

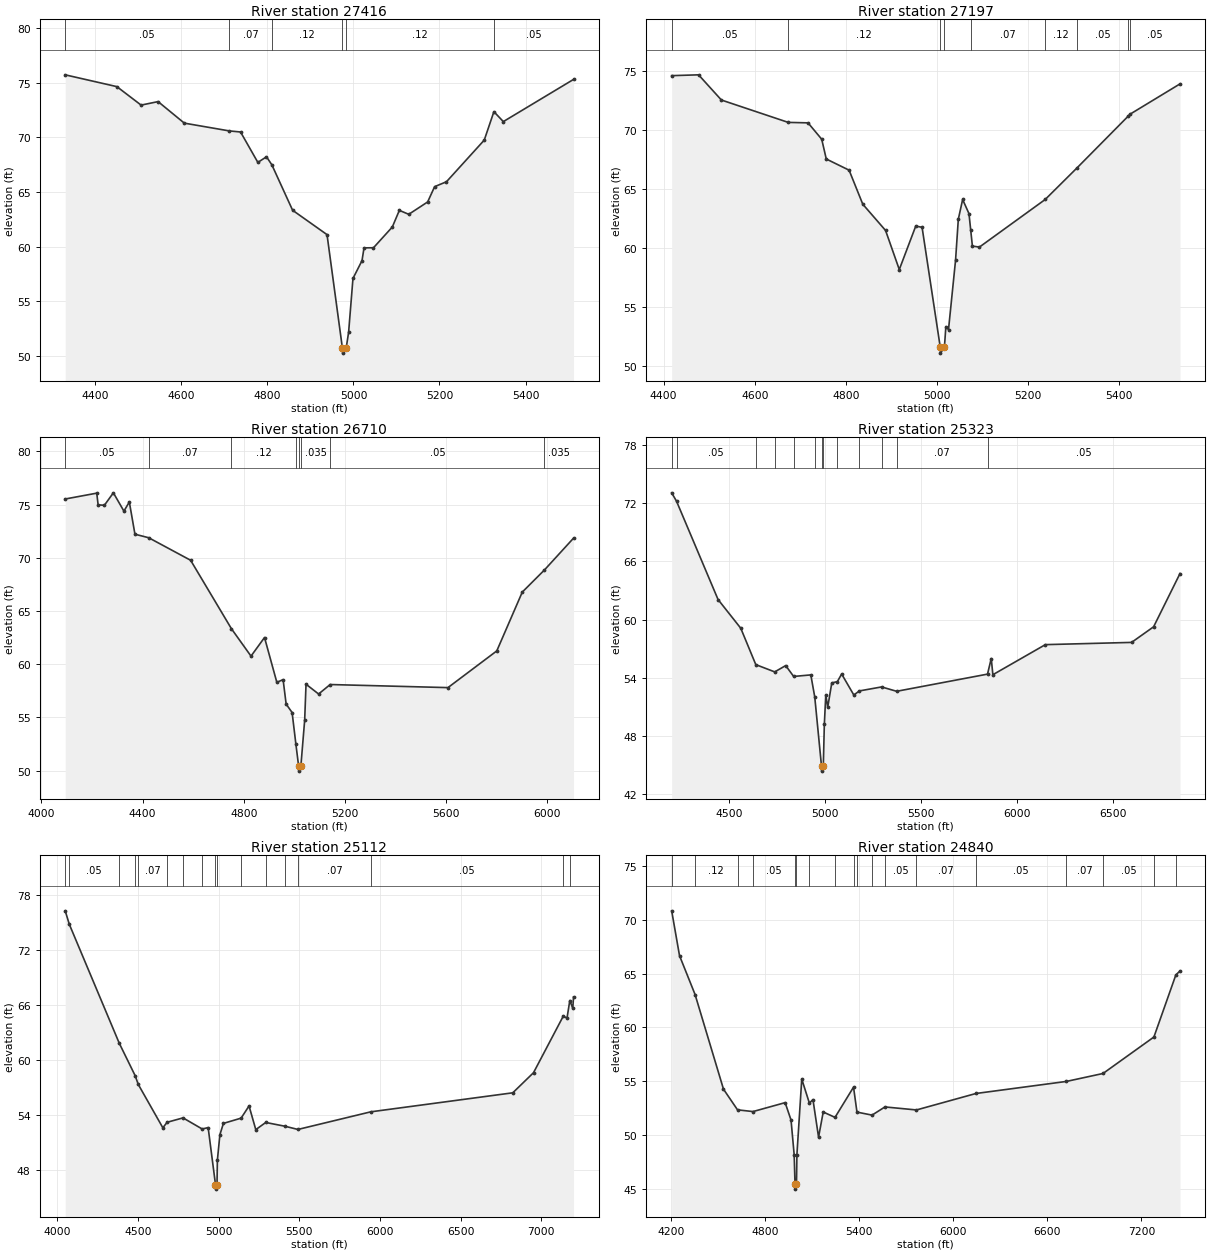
Type RM Length L Ch R = 1 ,27416   ,219,219,219
BEGIN DESCRIPTION:
Mapping XS e2629e8e
END DESCRIPTION:
XS GIS Cut Line= 3
      2628980.59     13460248.25      2628298.31     13460315.95
      2627861.12     13460550.17
#Sta/Elev= 30
    4330   75.73  4450.1   74.65  4506.4   72.96  4545.9   73.28  4606.9   71.31
  4711.3    70.6  4737.6    70.5  4777.8   67.72  4797.9   68.23  4810.3    67.5
  4858.6   63.34  4938.6   61.11  4974.2   50.77  4974.7   50.27  4983.3   50.77
  4988.8   52.19  4998.9    57.1  5019.9   58.73  5024.6    59.9  5046.6   59.91
  5090.4   61.81  5106.7   63.33  5128.6   62.97  5172.5    64.1  5188.7    65.5
  5216.3   65.95  5304.1   69.76  5326.5   72.36  5348.4   71.45  5511.6   75.31
#Mann= 6 ,-1 , 0
    4330     .05       0  4711.3     .07       0  4810.3     .12       0
  4974.2     .05       0  4983.3     .12       0  5326.5     .05       0
Bank Sta=4974.2,4983.3
XS Rating Curve= 0 ,0
Exp/Cntr=0.3,0.1

Type RM Length L Ch R = 1 ,27197   ,487,487,487
BEGIN DESCRIPTION:
Mapping XS 450f34cb
END DESCRIPTION:
XS GIS Cut Line= 3
      2628854.01     13460119.86      2628291.47     13460099.03
      2627818.73     13460384.75
#Sta/Elev= 30
  4417.8   74.63  4476.8    74.7  4526.9   72.56  4673.5   70.66    4717   70.62
    4747   69.23    4757   67.55  4807.1    66.6  4837.1   63.71  4887.1   61.48
  4917.2   58.16  4953.3   61.85  4967.2   61.75  5007.1   51.56  5007.6   51.06
  5016.2   51.56  5019.4   53.31  5025.2   53.06  5040.7   58.97  5046.7   62.43
  5056.2   64.11  5070.1   62.91  5073.8   61.55  5077.6   60.15  5093.1   60.07
  5237.3   64.11  5307.3    66.8  5419.7    71.2  5424.1   71.37  5533.1   73.93
#Mann= 9 ,-1 , 0
  4417.8     .05       0  4673.5     .12       0  5007.1     .05       0
  5016.2     .12       0  5073.8     .07       0  5237.3     .12       0
  5307.3     .05       0  5419.7     .07       0  5424.1     .05       0
Bank Sta=5007.1,5016.2
XS Rating Curve= 0 ,0
Exp/Cntr=0.3,0.1

Type RM Length L Ch R = 1 ,26710   ,1387,1387,1387
BEGIN DESCRIPTION:
Mapping XS 2cab7d3a
END DESCRIPTION:
XS GIS Cut Line= 3
       2629232.1      13459985.8      2628146.19     13459575.65
      2627653.99     13460267.07
#Sta/Elev= 30
  4093.8   75.53  4218.5   76.08  4223.9   74.98  4248.7   74.94  4284.2   76.11
  4325.9   74.39  4347.3   75.25  4369.5   72.22  4423.8   71.89  4589.6   69.77
  4750.8   63.34  4828.3   60.76  4881.7   62.51  4930.4    58.3  4955.2   58.55
  4967.2   56.25  4990.8   55.46  5005.8   52.47  5016.4   50.45  5016.9   49.95
  5025.5   50.45  5040.5   54.76  5045.8   58.12  5095.5    57.2  5141.3   58.09
  5606.9    57.8  5799.9   61.25  5900.7   66.78  5988.4   68.86  6103.3   71.85
#Mann= 8 ,-1 , 0
  4093.8     .05       0  4423.8     .07       0  4750.8     .12       0
  5005.8    .035       0  5016.4     .05       0  5025.5    .035       0
  5141.3     .05       0  5988.4    .035       0
Bank Sta=5016.4,5025.5
XS Rating Curve= 0 ,0
Exp/Cntr=0.3,0.1

Type RM Length L Ch R = 1 ,25323   ,211,211,211
BEGIN DESCRIPTION:
CRESECENT VALLEY CREEK 37.0
END DESCRIPTION:
XS GIS Cut Line= 3
        2629575.       13458625.        2628775.       13458525.
      2627775.01     13460074.99
#Sta/Elev= 30
  4198.7   73.06  4223.9    72.2  4440.6   62.06    4559    59.1  4637.4   55.35
  4736.1    54.6  4793.3   55.25  4834.8   54.13  4924.3   54.29  4944.8   52.02
  4980.1   44.87  4980.6   44.37  4989.4   44.87  4994.8   49.18  5002.4   52.24
  5012.5   50.96  5033.6   53.46  5062.8    53.6  5085.1   54.38  5148.5   52.22
  5178.1   52.64  5293.4   53.05  5371.9    52.6  5845.7   54.37  5865.2   55.98
  5873.7   54.31  6147.4   57.41  6597.1   57.64  6711.9   59.25  6849.5   64.74
#Mann= 13 ,-1 , 0
  4198.7    .045       0  4223.9     .05       0  4637.4    .035       0
  4736.1     .05       0  4834.8     .12       0  4944.8     .07       0
  4980.1     .05       0  4989.4     .07       0  5062.8     .05       0
  5178.1     .07       0  5293.4     .05       0  5371.9     .07       0
  5845.7     .05       0
Bank Sta=4980.1,4989.4
XS Rating Curve= 0 ,0
Exp/Cntr=0.3,0.1

Type RM Length L Ch R = 1 ,25112   ,272,272,272
BEGIN DESCRIPTION:
Mapping XS 7024bd9f
END DESCRIPTION:
XS GIS Cut Line= 3
      2629678.54     13458258.66      2628735.81     13458326.37
      2627455.75     13460121.58
#Sta/Elev= 30
  4049.7   76.23  4075.2   74.76  4384.9    61.8  4483.6   58.26  4502.2   57.33
  4654.8    52.6  4681.1    53.2  4779.8   53.68  4898.5   52.47  4935.5   52.62
    4981   46.42  4981.5   45.92  4990.3   46.42  4992.8   49.09  5008.2   51.84
    5030   53.08  5139.6   53.65  5188.9   54.98  5230.7    52.4  5292.4   53.18
  5411.2   52.77  5491.8   52.42  5943.6   54.34  6823.2   56.41  6951.7    58.6
  7135.5   64.74  7159.4   64.56  7176.6   66.46  7195.1   65.61  7199.7   66.85
#Mann= 17 ,-1 , 0
  4049.7    .045       0  4075.2     .05       0  4384.9    .035       0
  4483.6     .12       0  4502.2     .07       0  4681.1     .05       0
  4779.8     .07       0  4898.5     .12       0    4981     .05       0
  4990.3     .12       0  5139.6     .05       0  5292.4     .07       0
  5411.2     .05       0  5491.8     .07       0  5943.6     .05       0
  7135.5    .035       0  7176.6     .05       0
Bank Sta=4981,4990.3
XS Rating Curve= 0 ,0
Exp/Cntr=0.3,0.1

Type RM Length L Ch R = 1 ,24840   ,306,306,306
BEGIN DESCRIPTION:
CRESECENT VALLEY CREEK 36.0
END DESCRIPTION:
XS GIS Cut Line= 3
      2629474.99       13458025.        2628675.       13458075.
      2627274.98     13460075.03
#Sta/Elev= 30
  4202.9   70.83    4253   66.66  4352.2   63.05  4533.5   54.25    4623   52.33
  4721.7   52.17  4926.8      53  4964.4   51.38  4984.4   48.15  4989.7   45.46
  4990.2   44.96  4999.2   45.46  5001.9   48.17  5032.8   55.19  5081.3   52.96
  5104.3   53.28    5140   49.79  5169.7   52.13    5245   51.63  5363.1   54.44
    5385   52.12  5481.2   51.84  5563.4    52.6  5764.5   52.32    6144   53.85
  6720.5   54.97  6954.7   55.71  7279.4    59.1  7419.3   64.87  7445.8   65.24
#Mann= 18 ,-1 , 0
  4202.9     .05       0  4352.2     .12       0    4623     .07       0
  4721.7     .05       0  4989.7     .05       0  4999.2     .05       0
  5081.3     .12       0    5245     .05       0  5363.1     .07       0
    5385     .05       0  5481.2     .07       0  5563.4     .05       0
  5764.5     .07       0    6144     .05       0  6720.5     .07       0
  6954.7     .05       0  7279.4    .035       0  7419.3     .05       0
Bank Sta=4989.7,4999.2
XS Rating Curve= 0 ,0
Exp/Cntr=0.3,0.1

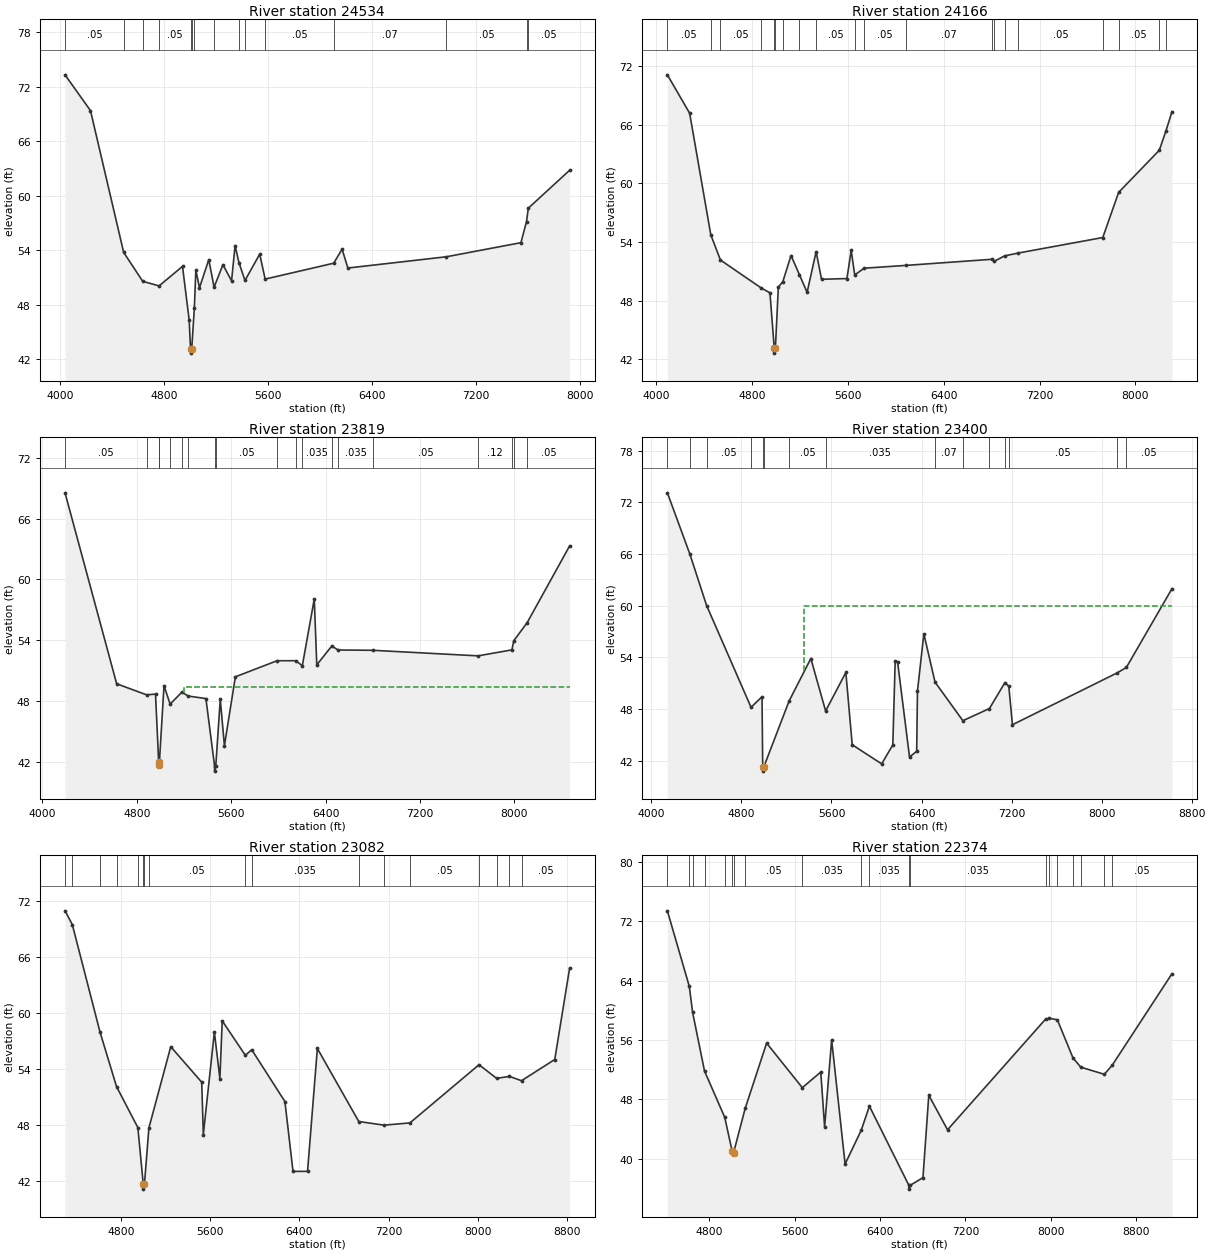
Type RM Length L Ch R = 1 ,24534   ,368,368,368
BEGIN DESCRIPTION:
Mapping XS 29061119
END DESCRIPTION:
XS GIS Cut Line= 4
      2629558.81     13457585.14      2628734.18     13457715.35
      2627952.93     13458218.82      2626781.08     13459989.61
#Sta/Elev= 30
  4035.5   73.31  4231.7   69.37  4487.3   53.76    4634   50.58  4760.1   50.07
  4940.7   52.22    4992   46.33  5002.4   43.17  5002.9   42.67  5011.9   43.17
  5031.8   47.59  5043.5    51.8  5071.6   49.87  5143.2   52.96    5184   49.93
  5252.1    52.4  5318.7   50.63  5345.8   54.51  5375.7   52.63    5422   50.67
  5535.6   53.57  5577.5   50.82  6105.3   52.57  6170.2   54.11  6214.9   52.04
  6974.3   53.28  7548.3   54.83  7591.3   57.16  7605.1   58.63  7923.2    62.8
#Mann= 15 ,-1 , 0
  4035.5     .05       0  4487.3     .12       0    4634     .07       0
  4760.1     .05       0  5002.4     .05       0  5011.9     .05       0
  5031.8     .12       0    5184     .07       0  5375.7     .05       0
    5422     .07       0  5577.5     .05       0  6105.3     .07       0
  6974.3     .05       0  7591.3    .035       0  7605.1     .05       0
Bank Sta=5002.4,5011.9
XS Rating Curve= 0 ,0
Exp/Cntr=0.3,0.1

Type RM Length L Ch R = 1 ,24166   ,347,347,347
BEGIN DESCRIPTION:
Mapping XS 2008a681
END DESCRIPTION:
XS GIS Cut Line= 4
      2629418.07     13457289.92      2628517.06     13457451.37
      2627459.77     13458451.37      2626475.38     13460008.69
#Sta/Elev= 30
  4092.7   71.11  4278.7   67.18  4455.4   54.73  4535.7   52.16    4876    49.3
  4949.2    48.8  4985.1   43.13  4985.6   42.63  4994.6   43.13  5019.2   49.39
  5056.9   49.95  5125.2   52.62  5195.8   50.64  5259.5   48.85  5334.7   53.01
    5380   50.19    5592   50.26  5627.6   53.15    5657   50.63  5735.6   51.32
    6087   51.61  6799.4   52.23  6823.7   52.04  6908.4   52.58  7021.1   52.87
  7728.3   54.46  7860.5   59.08  8200.2   63.39  8256.3    65.4  8305.7   67.34
#Mann= 20 ,-1 , 0
  4092.7     .05       0  4455.4     .12       0  4535.7     .05       0
    4876     .12       0  4985.1     .05       0  4994.6     .12       0
  5056.9     .12       0  5195.8     .07       0  5334.7     .05       0
    5657     .07       0  5735.6     .05       0    6087     .07       0
  6799.4     .05       0  6823.7     .07       0  6908.4     .05       0
  7021.1     .05       0  7728.3    .035       0  7860.5     .05       0
  8200.2     .07       0  8256.3     .05       0
Bank Sta=4985.1,4994.6
XS Rating Curve= 0 ,0
Exp/Cntr=0.3,0.1

Type RM Length L Ch R = 1 ,23819   ,419,419,419
BEGIN DESCRIPTION:
Mapping XS dc7bd78d
END DESCRIPTION:
XS GIS Cut Line= 4
       2629220.3     13456942.78      2628430.36     13457133.75
      2627414.73     13457949.72      2626312.32     13459807.33
#Sta/Elev= 30
  4191.5   68.55  4629.1   49.68  4882.3   48.59  4958.3   48.66  4986.1   41.68
  4991.3   41.93  5030.2    49.5  5082.1   47.67  5182.2   48.86  5234.4   48.47
  5385.4   48.22  5458.8   41.55  5459.3   41.05  5468.9   41.55    5507   48.15
  5542.2   43.56    5635   50.37  5988.8   51.96  6147.9   51.96  6202.3   51.46
  6303.6   58.07  6324.8   51.55  6451.8   53.41  6505.9   53.02  6800.1   52.99
  7691.7   52.44    7978   53.03  7994.5   53.94  8107.4   55.72  8467.1    63.3
#Mann= 19 ,-1 , 0
  4191.5     .05       0  4882.3     .12       0  4986.1     .05       0
  4991.3     .12       0  5082.1     .07       0  5182.2     .12       0
  5234.4     .05       0  5458.8     .07       0  5468.9     .05       0
  5988.8    .035       0  6147.9     .07       0  6202.3    .035       0
  6451.8     .07       0  6505.9    .035       0  6800.1     .05       0
  7691.7     .12       0    7978    .035       0  7994.5     .12       0
  8107.4     .05       0
#XS Ineff= 2 , 0
       0                    5200       0   49.37
Permanent Ineff=
       F       F
Bank Sta=4986.1,4991.3
XS Rating Curve= 0 ,0
Exp/Cntr=0.3,0.1

Type RM Length L Ch R = 1 ,23400   ,318,318,318
BEGIN DESCRIPTION:
Mapping XS 9469b7e6
END DESCRIPTION:
XS GIS Cut Line= 4
      2629074.39      13456477.4      2628241.02      13456784.7
      2627214.98     13457810.75      2626050.07     13459610.12
#Sta/Elev= 30
  4142.2    73.1  4342.2   65.99  4490.7   60.03  4885.7   48.22  4983.1   49.45
  4989.2   41.32  4989.7   40.82  4999.3   41.32  5224.3   48.97  5416.7   53.88
  5548.2    47.8  5727.9   52.26  5784.4   43.88    6046   41.66    6145   43.86
  6166.3   53.59  6187.5   53.49  6293.5   42.46  6357.2   43.12  6364.2    50.1
  6420.8   56.75    6520   51.15  6767.4   46.67  7003.5   48.08  7141.1   51.09
  7175.6   50.66  7207.8    46.2  8133.1   52.18  8219.8   52.84    8625   61.98
#Mann= 15 ,-1 , 0
  4142.2     .05       0  4342.2     .07       0  4490.7     .05       0
  4885.7     .12       0  4989.2     .05       0  4999.3     .12       0
  5224.3     .05       0  5548.2    .035       0    6520     .07       0
  6767.4    .035       0  7003.5     .05       0  7141.1    .035       0
  7175.6     .05       0  8133.1    .035       0  8219.8     .05       0
#XS Ineff= 2 , 0
       0                  5360.2       0      60
Permanent Ineff=
       F       F
Bank Sta=4989.2,4999.3
XS Rating Curve= 0 ,0
Exp/Cntr=0.3,0.1

Type RM Length L Ch R = 1 ,23082   ,708,708,708
BEGIN DESCRIPTION:
Mapping XS a3486d31
END DESCRIPTION:
XS GIS Cut Line= 4
      2628760.26       13456257.      2628135.22     13456491.39
      2627423.41     13457081.67      2625843.56     13459546.93
#Sta/Elev= 30
  4300.7    70.9  4365.9   69.43  4613.9   57.93  4762.1   52.08  4953.2   47.69
  5001.9    41.6  5002.4    41.1  5012.1    41.6  5052.1   47.65  5247.9   56.35
  5525.3   52.55  5539.7   46.94  5638.6   57.92  5688.1   52.93    5709   59.12
  5915.9   55.43  5973.3   56.03  6270.5   50.48  6343.2      43  6473.4      43
  6561.3   56.16  6932.3   48.34  7158.7   47.95  7390.4   48.19  8009.4   54.42
  8167.3   52.96  8282.4   53.17  8390.1   52.71  8688.1   54.98    8821   64.76
#Mann= 17 ,-1 , 0
  4300.7     .05       0  4365.9     .12       0  4613.9     .07       0
  4762.1     .05       0  4953.2     .12       0  5001.9     .05       0
  5012.1     .12       0  5052.1     .05       0  5915.9     .07       0
  5973.3    .035       0  6932.3     .05       0  7158.7    .035       0
  7390.4     .05       0  8009.4     .12       0  8167.3     .05       0
  8282.4    .035       0  8390.1     .05       0
#XS Ineff= 2 , 0
       0                    5709       0   59.12
Permanent Ineff=
       F       F
Bank Sta=5001.9,5012.1
XS Rating Curve= 0 ,0
Exp/Cntr=0.3,0.1

Type RM Length L Ch R = 1 ,22374   ,594,594,594
BEGIN DESCRIPTION:
Mapping XS 36b21dc4
END DESCRIPTION:
XS GIS Cut Line= 4
      2628248.05     13455701.47      2627692.51     13455979.24
      2626972.03     13456508.75      2625461.62     13459347.27
#Sta/Elev= 30
  4406.3    73.4  4611.8   63.23  4643.1   59.72  4754.5   51.83  4944.1    45.6
  5013.4   41.05  5027.4   40.86  5135.8    46.8  5336.7   55.59  5671.4   49.59
  5844.4   51.69  5880.6    44.3  5946.4   56.03  6072.5   39.31  6223.3   43.84
  6300.5    47.1  6670.8   36.43  6671.3   35.93    6682   36.43  6802.6   37.48
  6857.2   48.57  7032.9   43.92  7952.1   58.82  7988.3   58.92  8062.2   58.74
  8208.9    53.6  8282.4   52.35  8502.6   51.39  8575.9   52.59  9136.9   64.93
#Mann= 20 ,-1 , 0
  4406.3     .12       0  4611.8     .12       0  4643.1     .07       0
  4754.5     .05       0  4944.1     .12       0  5013.4     .05       0
  5027.4     .12       0  5135.8     .05       0  5671.4    .035       0
  6223.3     .05       0  6300.5    .035       0  6670.8     .07       0
    6682    .035       0  7952.1     .12       0  7988.3    .035       0
  8062.2     .05       0  8208.9    .035       0  8282.4     .05       0
  8502.6    .035       0  8575.9     .05       0
#XS Ineff= 2 , 0
       0                  5946.4       0   56.03
Permanent Ineff=
       F       F
Bank Sta=5013.4,5027.4
XS Rating Curve= 0 ,0
Exp/Cntr=0.3,0.1