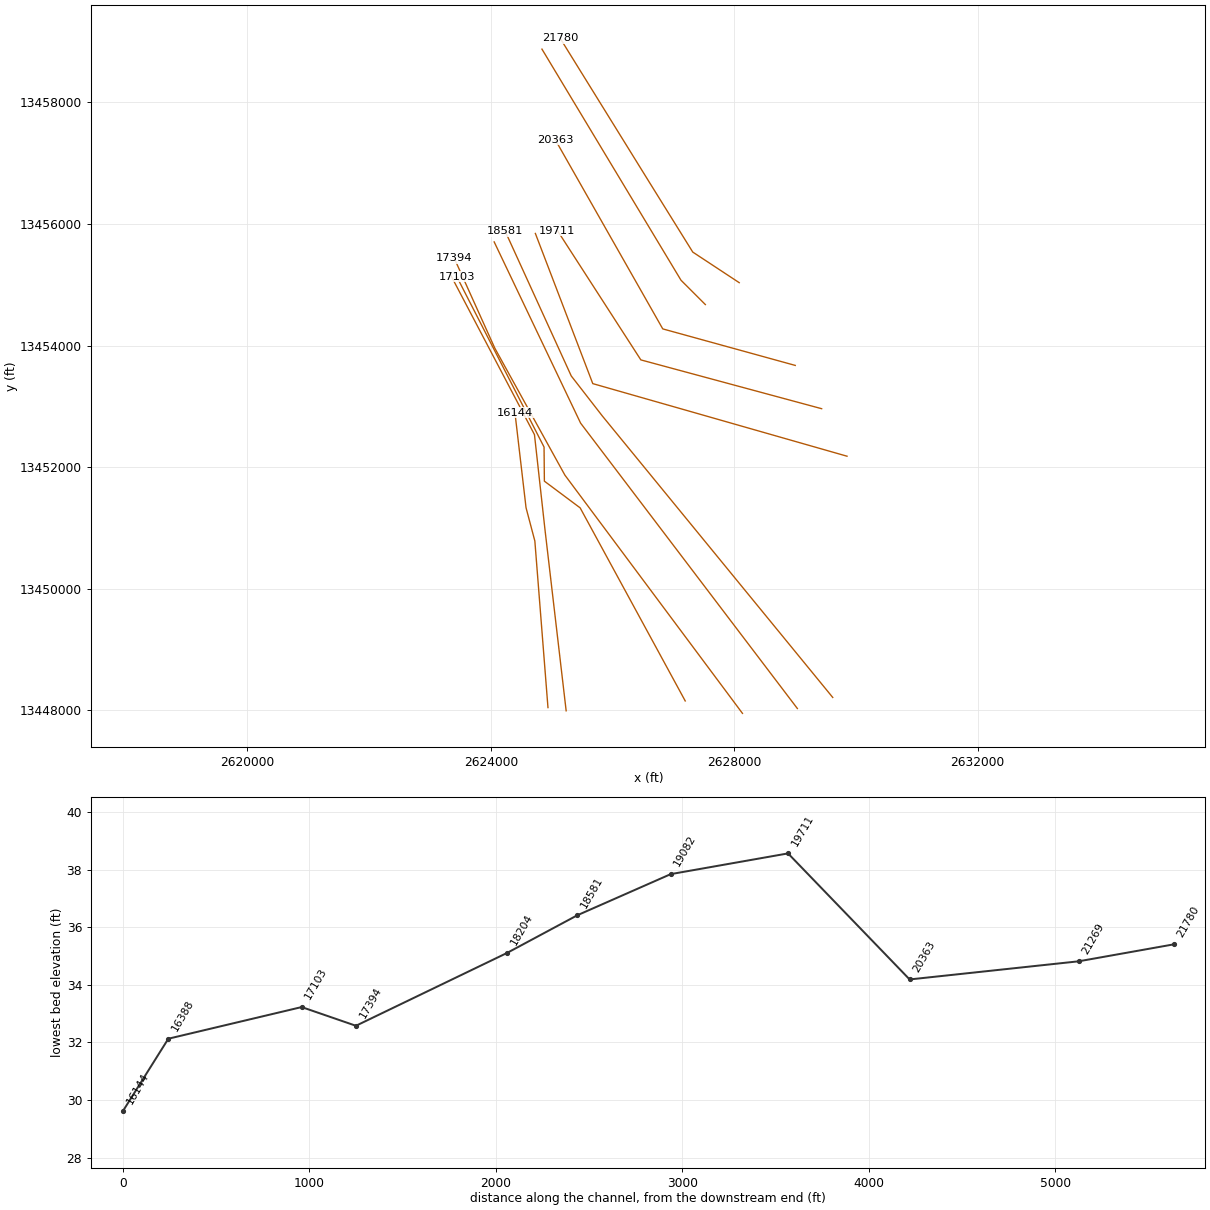
HEC-RAS study CRESECENT VALLEY CREEK.prj: CRESECENT VALLEY CREEK Base Level Engineering

--- CRESECENT VALLEY CREEK.g01 (geometry) --- (continued)

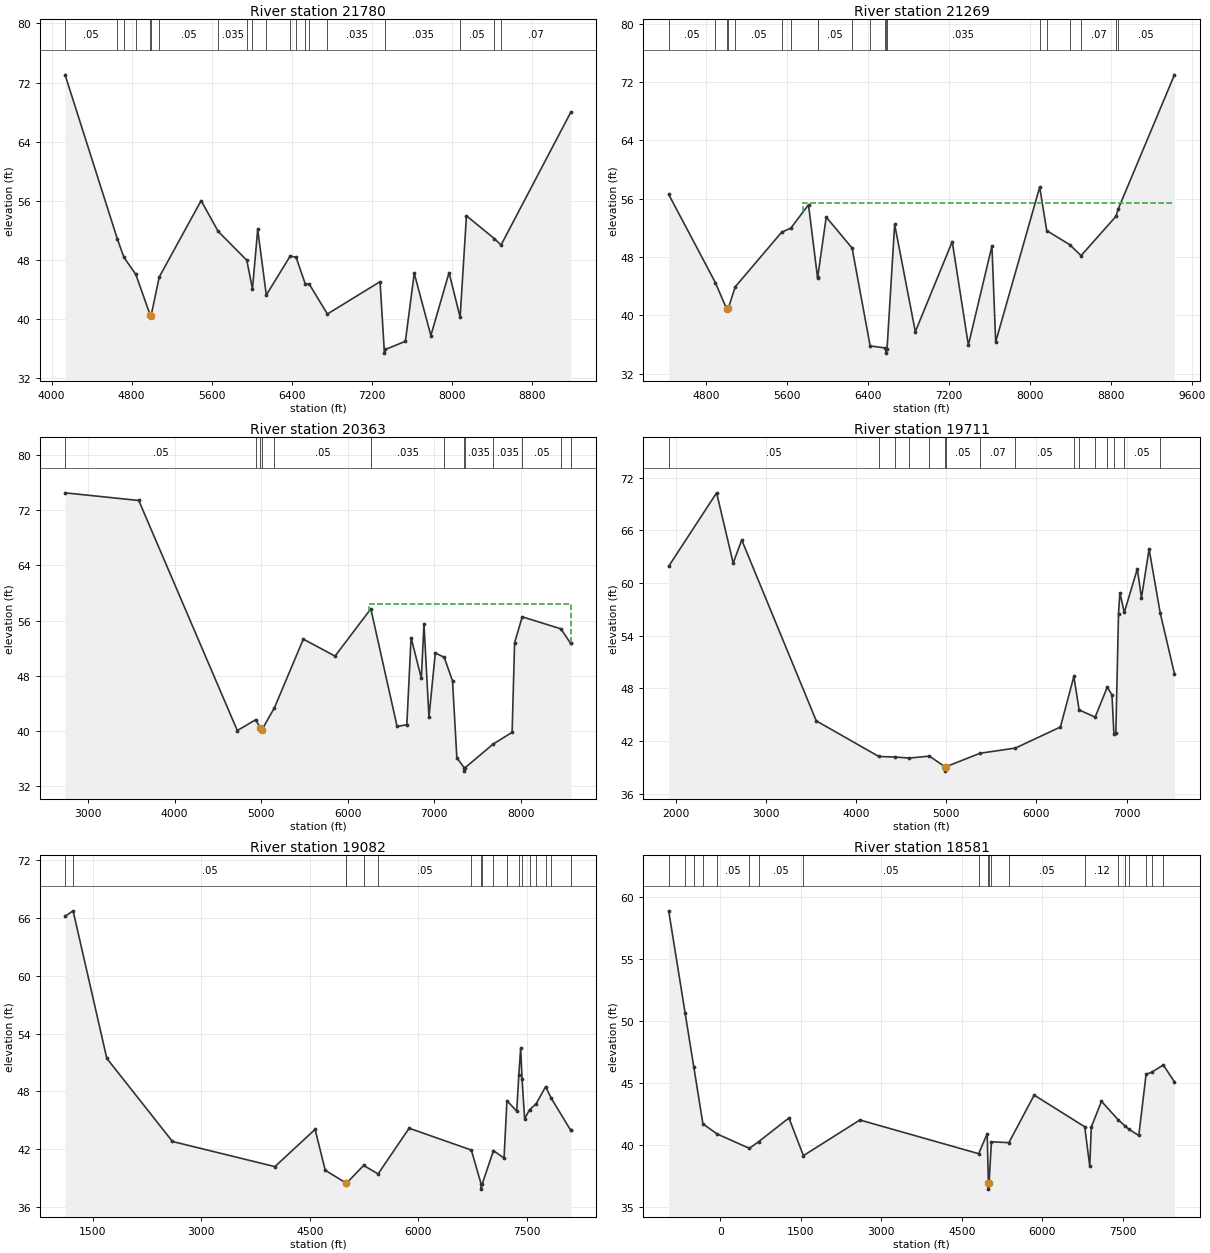
Type RM Length L Ch R = 1 ,21780   ,511,511,511
BEGIN DESCRIPTION:
Mapping XS f47980bc
END DESCRIPTION:
XS GIS Cut Line= 4
      2628081.87     13455034.79      2627318.02     13455538.24
      2626606.21     13456684.08      2625139.61      13459053.2
#Sta/Elev= 30
  4135.3   73.04  4658.4    50.8    4723   48.36  4841.9   46.05  4984.3   40.59
  4993.4   40.42  5075.5    45.7  5493.7   56.03  5664.1   51.87  5949.8   47.97
  6006.6    44.1  6058.8   52.13  6144.7   43.27  6383.5   48.54    6442   48.37
  6534.8   44.73  6571.8   44.78  6754.8    40.7  7280.6   45.07  7324.1   35.41
  7334.9   35.91  7533.4   37.01  7622.1    46.2    7788   37.79  7969.5   46.29
  8080.1   40.25  8143.2   53.98  8421.5    50.9  8488.8   50.03  9185.4   67.99
#Mann= 20 ,-1 , 0
  4135.3     .05       0  4658.4     .07       0    4723     .05       0
  4841.9     .12       0  4984.3     .05       0  4993.4     .12       0
  5075.5     .05       0  5664.1    .035       0  5949.8     .05       0
  6006.6    .035       0  6144.7     .05       0  6383.5    .035       0
    6442     .05       0  6534.8    .035       0  6571.8     .05       0
  6754.8    .035       0  7334.9    .035       0  8080.1     .05       0
  8421.5    .035       0  8488.8     .07       0
#XS Ineff= 2 , 0
       0                  5493.7       0   56.03
Permanent Ineff=
       F       F
Bank Sta=4984.3,4993.4
XS Rating Curve= 0 ,0
Exp/Cntr=0.3,0.1

Type RM Length L Ch R = 1 ,21269   ,906,906,906
BEGIN DESCRIPTION:
CRESECENT VALLEY CREEK 28.0
END DESCRIPTION:
XS GIS Cut Line= 3
      2627524.98     13454675.02        2627125.       13455075.
      2624839.85     13458875.66
#Sta/Elev= 30
  4428.7    56.6  4890.6   44.49  5002.1   40.87  5017.7   40.96  5086.5   43.92
  5545.3   51.41  5636.8   51.98  5811.1   55.18  5900.3   45.19  5902.4   45.26
  5986.2   53.49    6242   49.24  6420.6   35.81  6563.2   35.54  6575.9   35.32
  6576.4   34.82  6587.2   35.32  6662.9   52.49  6867.1   37.76  7232.3   50.12
  7391.6   35.92  7624.8   49.52  7661.7   36.36    8097   57.61  8166.5   51.63
  8392.9   49.71  8506.1    48.2    8851   53.59  8872.6   54.57  9429.1   73.01
#Mann= 20 ,-1 , 0
  4428.7     .05       0  4890.6     .12       0  5002.1     .05       0
  5017.7     .12       0  5086.5     .05       0  5545.3    .035       0
  5636.8     .05       0  5900.3    .035       0  5902.4     .05       0
    6242    .035       0  6420.6     .07       0  6563.2    .035       0
  6575.9     .07       0  6587.2    .035       0    8097     .05       0
  8166.5     .07       0  8392.9     .12       0  8506.1     .07       0
    8851    .035       0  8872.6     .05       0
#XS Ineff= 2 , 0
       0                  5759.8       0   55.49
Permanent Ineff=
       F       F
Bank Sta=5002.1,5017.7
XS Rating Curve= 0 ,0
Exp/Cntr=0.3,0.1

Type RM Length L Ch R = 1 ,20363   ,652,652,652
BEGIN DESCRIPTION:
CRESECENT VALLEY CREEK 26.0
END DESCRIPTION:
XS GIS Cut Line= 3
      2629002.39     13453674.29        2626825.       13454275.
      2625056.65     13457389.46
#Sta/Elev= 30
    2736   74.52  3586.9   73.41    4725   40.07  4938.3   41.65  4992.1   40.37
  5008.4   40.17  5153.6   43.37  5487.2   53.32  5853.5   50.86  6266.8   57.71
  6570.2   40.66  6682.6   40.92  6731.6   53.53  6849.9   47.66  6880.6   55.51
  6938.1   42.01  7011.4   51.31  7113.9   50.69  7210.4   47.25  7260.1   36.12
  7344.6   34.69  7345.1   34.19    7356   34.69  7680.2   38.12  7898.4   39.81
  7927.1    52.8  8015.2   56.55  8461.9   54.81  8573.6   52.71  8576.2    52.7
#Mann= 13 ,-1 , 0
    2736     .05       0  4938.3     .12       0  4992.1     .05       0
  5008.4     .12       0  5153.6     .05       0  6266.8    .035       0
  7113.9     .07       0  7344.6     .07       0    7356    .035       0
  7680.2    .035       0  8015.2     .05       0  8461.9    .035       0
  8573.6     .12       0
#XS Ineff= 2 , 0
       0                  6241.4       0   58.37
Permanent Ineff=
       F       F
Bank Sta=4992.1,5008.4
XS Rating Curve= 0 ,0
Exp/Cntr=0.3,0.1

Type RM Length L Ch R = 1 ,19711   ,629,629,629
BEGIN DESCRIPTION:
CRESECENT VALLEY CREEK 25.0
END DESCRIPTION:
XS GIS Cut Line= 3
      2629436.47     13452962.47      2626465.12     13453764.95
      2625094.19      13455891.2
#Sta/Elev= 30
  1922.2   61.92  2453.4   70.29  2637.4   62.28  2731.7   64.92  3558.5    44.3
  4251.9   40.24    4430   40.18  4588.7   40.06  4813.6   40.28  4984.1   39.07
  4984.6   38.57  4995.5   39.07  5375.7   40.61  5767.4    41.2  6265.8    43.6
  6414.9   49.36    6473   45.55  6650.7   44.72  6784.9   48.14  6837.4   47.27
  6858.6   42.84    6880   42.87    6910   56.53  6925.2    58.9  6973.9   56.65
  7118.6   61.62  7164.1   58.32  7248.9   63.87  7372.7   56.58  7529.9   49.68
#Mann= 16 ,-1 , 0
  1922.2     .05       0  4251.9     .07       0    4430     .05       0
  4588.7     .07       0  4813.6     .05       0  4984.1     .05       0
  4995.5     .05       0  5375.7     .07       0  5767.4     .05       0
  6414.9     .07       0    6473     .05       0  6650.7    .035       0
  6784.9     .07       0  6858.6    .035       0  6973.9     .05       0
  7372.7     .07       0
Bank Sta=4984.1,4995.5
XS Rating Curve= 0 ,0
Exp/Cntr=0.3,0.1

Type RM Length L Ch R = 1 ,19082   ,501,501,501
BEGIN DESCRIPTION:
CRESECENT VALLEY CREEK 24.0
END DESCRIPTION:
XS GIS Cut Line= 3
      2629853.11     13452181.23        2625675.       13453375.
       2624731.6     13455844.42
#Sta/Elev= 30
  1117.9    66.2  1228.8   66.77  1694.5   51.44  2601.9    42.8  4017.6   40.19
  4572.7   44.06  4713.1   39.81  4995.2   38.51  5004.3   38.44  5243.2   40.31
  5443.3   39.43  5872.4   44.18    6732   41.91  6868.5   38.35    6869   37.85
  6880.7   38.35  7037.7   41.85  7183.9   41.08    7224   47.04    7359   45.96
    7388   49.69  7413.8   52.52  7432.9   49.32  7468.5   45.16  7537.4   46.11
  7627.7   46.72  7758.6    48.5    7836    47.3  8105.5   43.96  8106.7   43.95
#Mann= 18 ,-1 , 0
  1117.9    .035       0  1228.8     .05       0  4995.2     .05       0
  5004.3     .05       0  5243.2     .07       0  5443.3     .05       0
    6732     .12       0  6868.5     .05       0  6880.7     .12       0
  7037.7     .07       0    7224    .035       0    7388     .12       0
  7432.9     .05       0  7537.4     .12       0  7627.7     .05       0
  7758.6    .063       0    7836     .07       0  8105.5     .12       0
Bank Sta=4995.2,5004.3
XS Rating Curve= 0 ,0
Exp/Cntr=0.3,0.1

Type RM Length L Ch R = 1 ,18581   ,377,377,377
BEGIN DESCRIPTION:
Mapping XS 5638ac99
END DESCRIPTION:
XS GIS Cut Line= 4
      2629618.36     13448214.03      2625833.64     13452840.76
      2625321.49     13453500.48      2624236.42     13455878.96
#Sta/Elev= 30
  -964.7   58.88    -660   50.67  -497.3   46.29  -326.2   41.68   -60.9   40.87
   539.4   39.71   714.6   40.26  1276.8   42.16  1546.1   39.12    2599      42
  4813.4   39.28  4972.1   40.89  4994.7   36.92  4995.2   36.42  5006.9   36.92
  5051.1   40.24    5377   40.17  5847.7   44.01  6790.3   41.45  6884.1   38.26
  6912.7   41.43  7102.5   43.51  7419.1   41.99  7544.3   41.51  7612.5   41.25
  7798.1   40.75  7933.7   45.68  8040.7   45.86  8254.9   46.44  8462.3   45.08
#Mann= 20 ,-1 , 0
  -964.7     .07       0    -660     .05       0  -497.3     .07       0
  -326.2     .05       0   -60.9     .05       0   539.4     .07       0
   714.6     .05       0  1546.1     .05       0  4813.4     .07       0
  4994.7     .05       0  5006.9     .05       0  5051.1     .07       0
    5377     .05       0  6790.3     .12       0  7419.1     .07       0
  7544.3     .07       0  7612.5     .12       0  7933.7    .063       0
  8040.7    .035       0  8254.9     .05       0
Bank Sta=4994.7,5006.9
XS Rating Curve= 0 ,0
Exp/Cntr=0.3,0.1

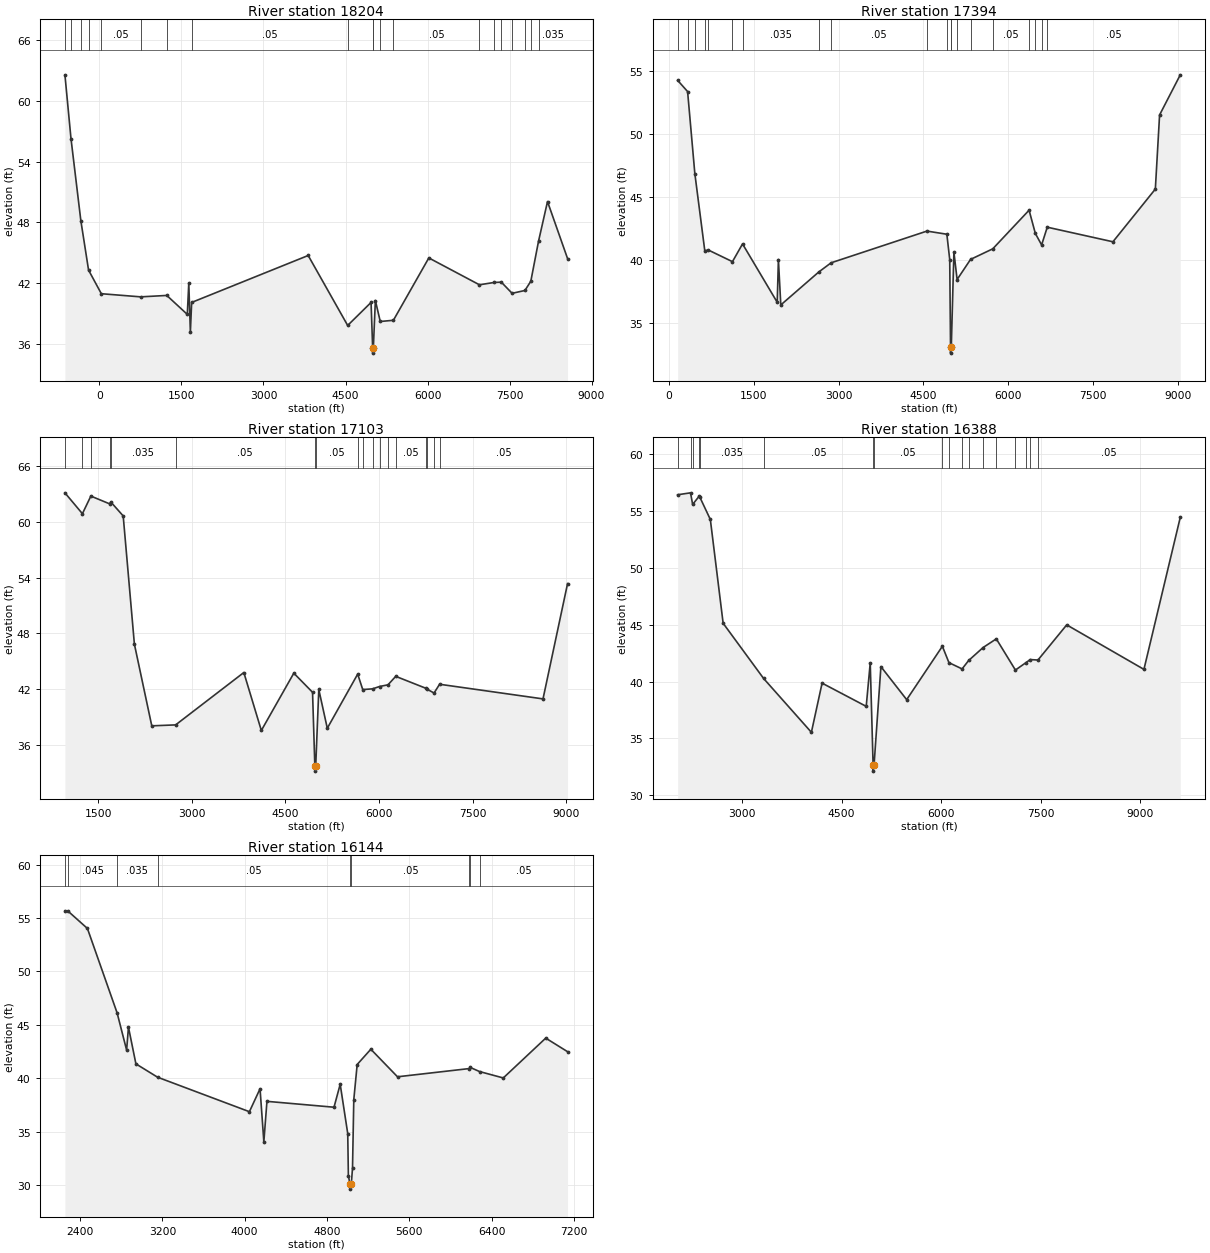
Type RM Length L Ch R = 1 ,18204   ,810,810,810
BEGIN DESCRIPTION:
CRESECENT VALLEY CREEK 23.0
END DESCRIPTION:
XS GIS Cut Line= 3
      2629037.16     13448031.92        2625475.       13452725.
       2624054.5     13455705.55
#Sta/Elev= 30
  -632.1   62.56  -521.1   56.27    -341   48.18  -199.7    43.3    33.9   40.97
   752.9   40.66  1230.9    40.8  1606.4   38.93  1633.5   42.01  1662.6   37.19
    1686   40.11  3817.4   44.74  4539.7   37.84  4967.5   40.11  4996.8   35.61
  4997.3   35.11    5009   35.61  5046.3    40.3  5135.7   38.23  5375.9   38.35
  6024.1    44.5  6949.7   41.85  7217.9   42.08  7350.4   42.11  7547.1   41.01
  7781.8   41.29  7889.6    42.2  8030.3   46.14  8194.9   50.06  8561.5   44.44
#Mann= 20 ,-1 , 0
  -632.1     .07       0  -521.1     .05       0    -341     .05       0
  -199.7     .07       0    33.9     .05       0   752.9     .07       0
  1230.9     .05       0    1686     .05       0  4539.7     .07       0
  4996.8     .05       0    5009     .05       0  5135.7     .07       0
  5375.9     .05       0  6949.7     .12       0  7217.9    .063       0
  7350.4     .12       0  7547.1     .07       0  7781.8     .07       0
  7889.6     .12       0  8030.3    .035       0
Bank Sta=4996.8,5009
XS Rating Curve= 0 ,0
Exp/Cntr=0.3,0.1

Type RM Length L Ch R = 1 ,17394   ,291,291,291
BEGIN DESCRIPTION:
Mapping XS 3b002573
END DESCRIPTION:
XS GIS Cut Line= 4
      2628135.04     13447952.04      2625216.55     13451870.46
       2624066.1     13453955.64      2623399.72     13455434.16
#Sta/Elev= 30
   153.3   54.26   329.2   53.37   457.2   46.85   633.1   40.72   698.2   40.77
  1122.4   39.85  1300.8   41.26  1914.2   36.62    1935   40.02  1977.5   36.41
  2649.2   39.03  2867.4   39.76  4562.2   42.28  4914.1   42.03  4965.1   40.01
  4979.1   33.08  4979.6   32.58  4992.7   33.08  5038.9   40.61  5095.5   38.43
  5333.3   40.03  5726.1   40.87  6368.4   43.94  6479.2   42.09  6590.2   41.18
  6689.9   42.59  7851.2   41.43  8601.4   45.62  8676.3   51.51  9042.4    54.7
#Mann= 20 ,-1 , 0
   153.3     .07       0   329.2     .07       0   457.2    .035       0
   633.1     .12       0   698.2    .035       0  1122.4    .063       0
  1300.8    .035       0  2649.2     .05       0  2867.4     .05       0
  4562.2     .05       0  4914.1     .05       0  4979.1     .05       0
  4992.7     .05       0  5095.5     .07       0  5333.3     .05       0
  5726.1     .05       0  6368.4     .05       0  6479.2     .07       0
  6590.2    .035       0  6689.9     .05       0
Bank Sta=4979.1,4992.7
XS Rating Curve= 0 ,0
Exp/Cntr=0.3,0.1

Type RM Length L Ch R = 1 ,17103   ,715,715,715
BEGIN DESCRIPTION:
Mapping XS 0f129820
END DESCRIPTION:
XS GIS Cut Line= 5
      2627194.28     13448156.52      2625467.57     13451331.58
      2624879.63     13451770.79      2624874.26     13452331.51
      2623441.31     13455131.16
#Sta/Elev= 30
   968.9   63.09  1249.1   60.85  1384.3   62.74  1684.5   61.91  1704.2   62.11
  1902.6   60.61  2082.1   46.85  2360.5   38.09  2742.8   38.19  3835.7   43.81
  4116.1   37.59  4636.5   43.74  4936.7   41.69  4973.7   33.73  4974.2   33.23
  4987.3   33.73  5036.8   41.99    5173   37.83    5660   43.64  5741.1   41.98
  5900.5   42.06  6009.8   42.31  6145.7   42.49  6269.5    43.4  6756.4   42.11
  6774.6   42.01  6883.8   41.61  6972.2   42.55  8629.5   40.98  9022.8   53.35
#Mann= 18 ,-1 , 0
   968.9    .035       0  1249.1    .063       0  1384.3    .035       0
  1684.5    .063       0  1704.2    .035       0  2742.8     .05       0
  4973.7    .035       0  4987.3     .05       0    5660     .07       0
  5741.1     .05       0  5900.5    .035       0  6009.8     .05       0
  6145.7     .07       0  6269.5     .05       0  6756.4     .07       0
  6774.6     .05       0  6883.8    .035       0  6972.2     .05       0
Bank Sta=4973.7,4987.3
XS Rating Curve= 0 ,0
Exp/Cntr=0.3,0.1

Type RM Length L Ch R = 1 ,16388   ,244,244,244
BEGIN DESCRIPTION:
Mapping XS eb9a46df
END DESCRIPTION:
XS GIS Cut Line= 4
       2625237.5     13447994.51      2624890.28     13450966.71
      2624716.67     13452536.15      2623323.51     13455190.87
#Sta/Elev= 30
    2032   56.41  2225.9   56.58  2257.8   55.56    2358    56.3  2368.5   56.17
  2524.2   54.24  2717.1   45.12  3326.4   40.27  4046.1   35.54  4207.2   39.86
  4871.7   37.82  4932.1   41.63  4975.6   32.63  4976.1   32.13  4989.3   32.63
  5093.1   41.31  5481.1   38.41  6018.7    43.1  6117.6   41.66  6315.5   41.11
  6414.4   41.85  6632.1   42.99  6830.9   43.75  7118.6   41.01    7272   41.64
  7341.8   41.93  7457.9   41.89  7891.3   44.98    9054   41.07  9601.5   54.43
#Mann= 18 ,-1 , 0
    2032     .05       0  2225.9    .063       0  2257.8    .035       0
    2358    .045       0  2368.5    .035       0  3326.4     .05       0
  4975.6    .035       0  4989.3     .05       0  6018.7     .07       0
  6117.6     .05       0  6315.5    .035       0  6414.4     .05       0
  6632.1     .07       0  6830.9     .05       0  7118.6     .07       0
    7272     .05       0  7341.8    .035       0  7457.9     .05       0
Bank Sta=4975.6,4989.3
XS Rating Curve= 0 ,0
Exp/Cntr=0.3,0.1

Type RM Length L Ch R = 1 ,16144   ,893,893,893
BEGIN DESCRIPTION:
Mapping XS 1dc9e049
END DESCRIPTION:
XS GIS Cut Line= 4
      2624938.68     13448047.05      2624723.14     13450786.09
      2624578.39     13451333.11      2624396.09     13452895.66
#Sta/Elev= 30
  2252.5   55.67  2280.4   55.66  2471.1   54.02  2759.9   46.11  2852.3   42.63
  2870.2   44.78  2942.6   41.34  3153.2   40.09    4046   36.86  4149.5   39.01
  4186.4   34.04  4216.5   37.83  4868.5   37.28  4928.7   39.43    5002   34.81
  5008.2   30.88  5023.1   30.11  5023.6   29.61  5036.8   30.11  5048.4   31.57
  5060.9   37.99  5093.8   41.28  5226.5   42.71  5485.8   40.13  6184.3    40.9
  6192.2   41.01  6283.3   40.62  6514.1   40.02  6926.9   43.75    7139   42.48
#Mann= 9 ,-1 , 0
  2252.5     .05       0  2280.4    .045       0  2759.9    .035       0
  3153.2     .05       0  5023.1    .035       0  5036.8     .05       0
  6184.3     .07       0  6192.2    .035       0  6283.3     .05       0
Bank Sta=5023.1,5036.8
XS Rating Curve= 0 ,0
Exp/Cntr=0.3,0.1