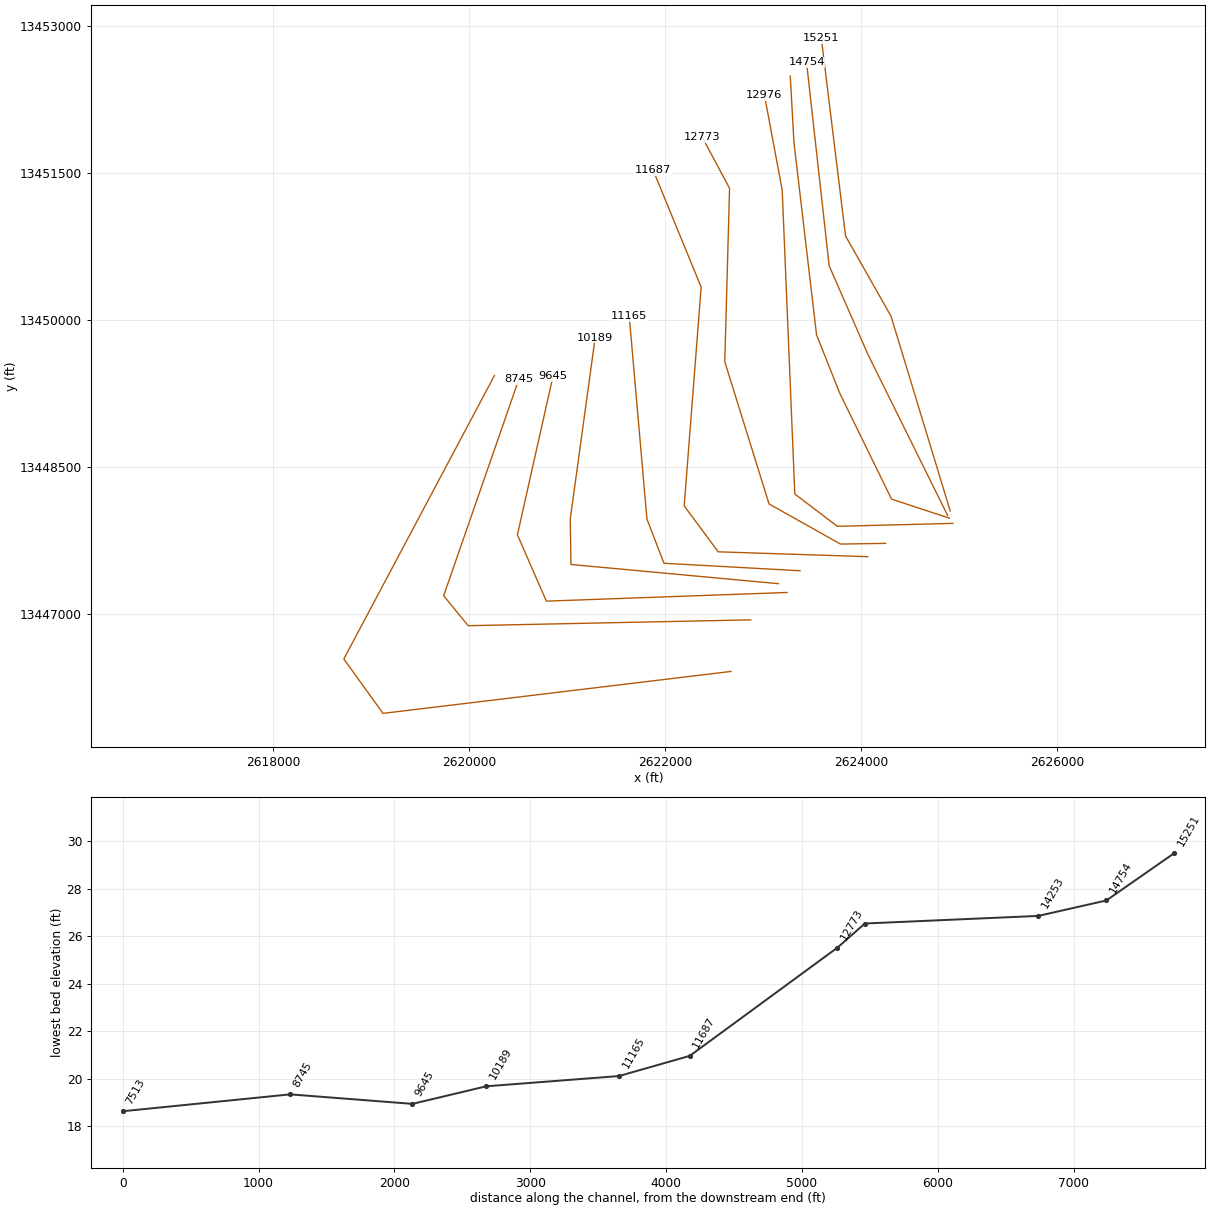
HEC-RAS study CRESECENT VALLEY CREEK.prj: CRESECENT VALLEY CREEK Base Level Engineering

--- CRESECENT VALLEY CREEK.g01 (geometry) --- (continued)

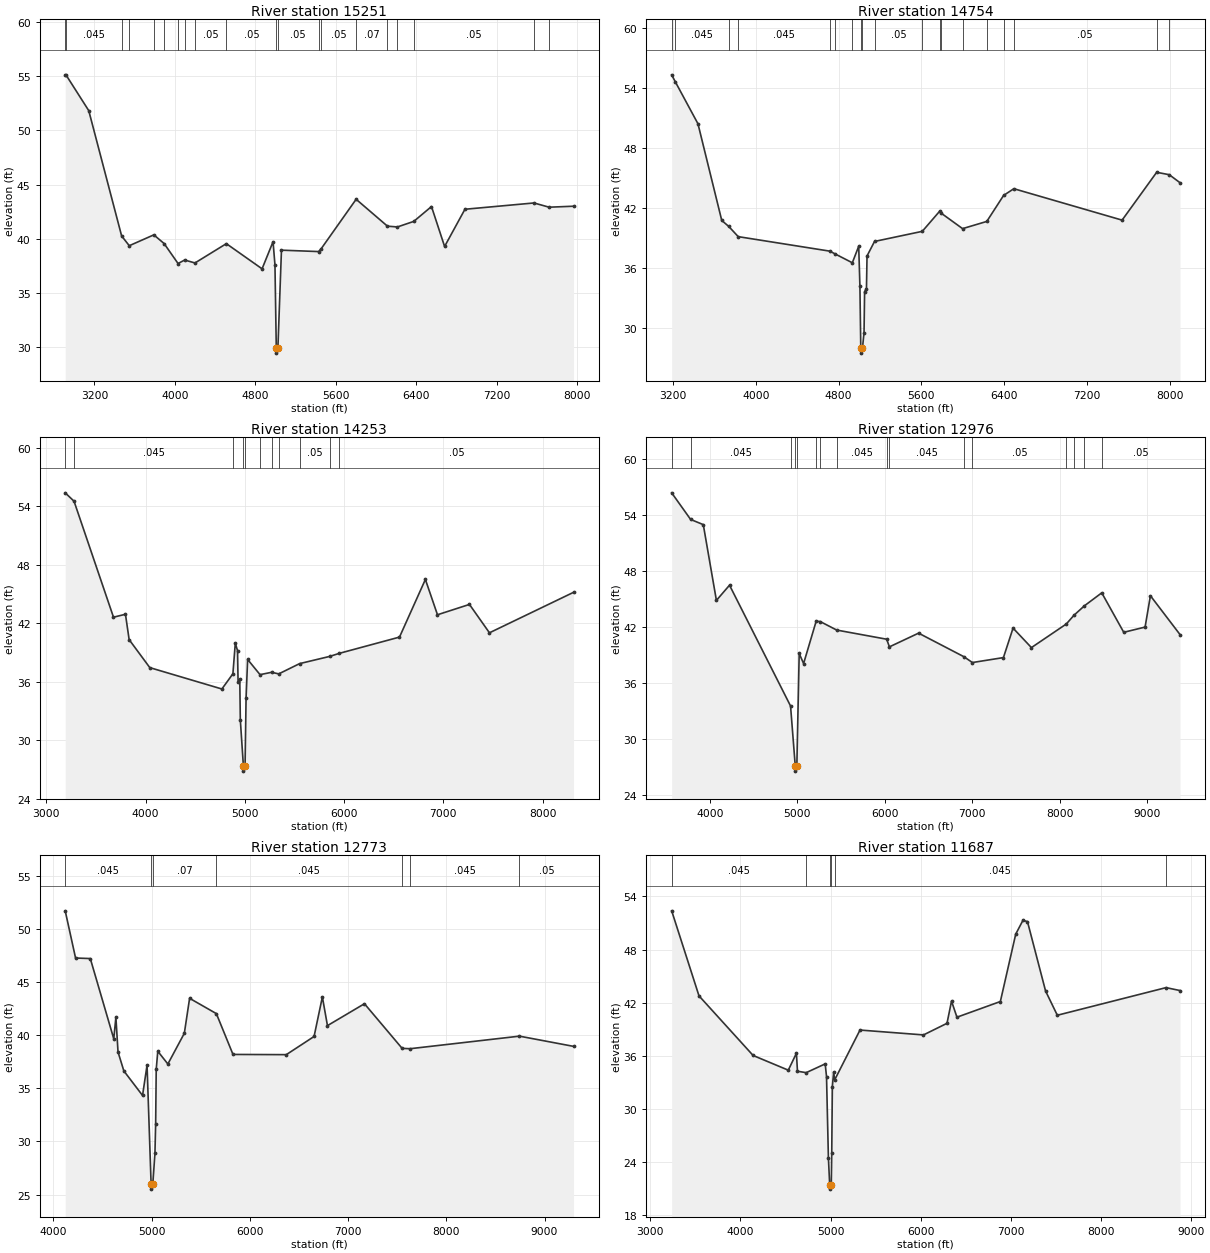
Type RM Length L Ch R = 1 ,15251   ,497,497,497
BEGIN DESCRIPTION:
Mapping XS 140af2e3
END DESCRIPTION:
XS GIS Cut Line= 4
      2624909.54     13448051.07      2624305.37     13450040.67
      2623841.83     13450858.38      2623594.87     13452876.36
#Sta/Elev= 30
  2909.8    55.1  2917.1   55.13  3143.8   51.83  3470.6   40.28  3546.4   39.38
  3790.6   40.38  3892.8   39.58  4031.3   37.74  4097.3   38.06  4199.5   37.79
  4511.4   39.57  4866.5   37.25  4975.6   39.75  4994.5   37.62  5007.7   29.98
  5008.2   29.48  5023.9   29.98  5059.1   38.97  5427.4   38.84  5452.3   39.08
  5801.3   43.66  6112.8   41.18  6211.9   41.11    6374   41.62  6550.3   42.99
  6680.6   39.31  6882.8   42.74    7569   43.32  7719.1   42.93  7962.1   43.02
#Mann= 20 ,-1 , 0
  2909.8     .05       0  2917.1    .045       0  3470.6    .035       0
  3546.4    .045       0  3790.6     .07       0  3892.8    .035       0
  4031.3     .05       0  4097.3    .035       0  4199.5     .05       0
  4511.4     .05       0  5007.7     .05       0  5023.9     .05       0
  5427.4     .07       0  5452.3     .05       0  5801.3     .07       0
  6112.8     .05       0  6211.9    .035       0    6374     .05       0
    7569     .07       0  7719.1     .05       0
Bank Sta=5007.7,5023.9
XS Rating Curve= 0 ,0
Exp/Cntr=0.3,0.1

Type RM Length L Ch R = 1 ,14754   ,501,501,501
BEGIN DESCRIPTION:
Mapping XS d500d16f
END DESCRIPTION:
XS GIS Cut Line= 4
      2624883.75     13448004.62      2624071.23     13449647.01
      2623674.96     13450553.26      2623443.95     13452631.07
#Sta/Elev= 30
  3187.2   55.31  3221.5   54.63  3441.2   50.42  3671.1   40.76  3738.7   40.16
  3830.3   39.14  4715.8   37.69    4769    37.4  4932.9   36.53  4994.6   38.18
  5006.2   34.18  5014.6      28  5015.1    27.5  5030.9      28  5046.1   29.56
  5051.6   33.65  5069.5   33.92    5075   37.21  5147.4   38.66  5608.9   39.67
  5778.5    41.7  5785.7   41.53  5998.3   39.94  6232.2   40.66  6394.8   43.26
  6493.7   43.93  7539.8   40.79  7873.8   45.57  7995.5   45.33  8099.3   44.53
#Mann= 19 ,-1 , 0
  3187.2     .05       0  3221.5    .045       0  3738.7    .035       0
  3830.3    .045       0  4715.8     .07       0    4769    .045       0
  4932.9     .07       0  5014.6    .035       0  5030.9     .07       0
  5147.4     .05       0  5608.9    .035       0  5778.5     .05       0
  5785.7     .07       0  5998.3     .05       0  6232.2     .07       0
  6394.8    .035       0  6493.7     .05       0  7873.8     .07       0
  7995.5     .05       0
Bank Sta=5014.6,5030.9
XS Rating Curve= 0 ,0
Exp/Cntr=0.3,0.1

Type RM Length L Ch R = 1 ,14253   ,1277,1277,1277
BEGIN DESCRIPTION:
Mapping XS c96df6c0
END DESCRIPTION:
XS GIS Cut Line= 6
       2624901.5     13447977.67      2624311.23     13448172.11
      2623783.45     13449251.97      2623545.86     13449850.14
      2623315.57     13451812.74      2623277.95     13452489.99
#Sta/Elev= 30
  3190.4   55.38  3279.3   54.52  3676.8   42.63  3797.4   42.93  3834.6   40.33
  4042.8   37.46    4769   35.27  4879.9   36.83  4904.1   39.97  4926.6    39.2
  4932.1   35.96  4949.1   36.27  4954.7   32.11  4985.8   27.35  4986.3   26.85
  5002.4   27.35  5012.7   34.34  5028.2    38.3  5153.3   36.74  5269.4   36.98
    5342   36.82  5551.9   37.87  5854.9   38.61  5953.9   38.93  6558.4   40.59
  6819.2    46.5    6941   42.88  7263.2   43.94  7464.6   41.03  8311.8   45.18
#Mann= 11 ,-1 , 0
  3190.4     .05       0  3279.3    .045       0  4879.9     .07       0
  4985.8    .035       0  5002.4     .07       0  5153.3     .07       0
  5269.4    .045       0    5342     .07       0  5551.9     .05       0
  5854.9    .035       0  5953.9     .05       0
Bank Sta=4985.8,5002.4
XS Rating Curve= 0 ,0
Exp/Cntr=0.3,0.1

Type RM Length L Ch R = 1 ,12976   ,203,203,203
BEGIN DESCRIPTION:
Mapping XS 0fc11ddb
END DESCRIPTION:
XS GIS Cut Line= 5
      2624936.71     13447924.68      2623758.22     13447894.77
      2623324.19     13448224.63       2623195.6     13451326.89
       2623014.2     13452297.74
#Sta/Elev= 30
  3561.4   56.36    3778   53.51  3923.2   52.95  4073.3   44.83  4223.3   46.46
  4921.7   33.51    4976   27.03  4976.5   26.53  4993.5   27.03  5020.6   39.14
  5070.9   38.06  5214.9    42.6  5261.6   42.56    5450   41.65  6021.3   40.67
    6053   39.85  6386.7   41.32  6903.9    38.8  7002.5   38.17  7357.6    38.7
  7467.7   41.86  7677.8   39.77    8077    42.3  8165.1   43.24  8284.3   44.25
  8482.7   45.64  8734.3   41.41  8978.5   41.97  9039.5   45.33    9378   41.17
#Mann= 16 ,-1 , 0
  3561.4     .05       0    3778    .045       0  4921.7     .07       0
    4976    .035       0  4993.5     .07       0  5214.9     .07       0
  5261.6     .12       0    5450    .045       0  6021.3     .12       0
    6053    .045       0  6903.9    .035       0  7002.5     .05       0
    8077     .07       0  8165.1     .05       0  8284.3     .07       0
  8482.7     .05       0
Bank Sta=4976,4993.5
XS Rating Curve= 0 ,0
Exp/Cntr=0.3,0.1

Type RM Length L Ch R = 1 ,12773   ,1086,1086,1086
BEGIN DESCRIPTION:
Mapping XS fafef1ea
END DESCRIPTION:
XS GIS Cut Line= 6
      2624250.49     13447720.63      2623790.48     13447713.43
      2623061.31     13448123.15      2622609.92     13449574.54
      2622658.54     13451345.37      2622381.62     13451864.17
#Sta/Elev= 30
  4119.5   51.69    4225   47.25    4375    47.2    4614   39.65  4635.6   41.68
  4657.3   38.41  4716.6   36.63    4907   34.32  4952.9   37.17  4994.1   26.01
  4994.6   25.51  5011.6   26.01  5033.2   28.87  5040.5   31.65  5046.2   36.77
  5062.2   38.48  5164.8   37.28  5332.5   40.17  5386.1   43.46  5658.6   42.02
    5828   38.18  6370.9   38.16  6653.6   39.87  6738.1   43.59  6789.8   40.89
  7166.5   42.95  7550.3   38.75    7632   38.72  8744.9    39.9  9295.5   38.94
#Mann= 7 ,-1 , 0
  4119.5    .045       0  4994.1    .035       0  5011.6     .07       0
  5658.6    .045       0  7550.3     .05       0    7632    .045       0
  8744.9     .05       0
Bank Sta=4994.1,5011.6
XS Rating Curve= 0 ,0
Exp/Cntr=0.3,0.1

Type RM Length L Ch R = 1 ,11687   ,522,522,522
BEGIN DESCRIPTION:
Mapping XS 9243cc13
END DESCRIPTION:
XS GIS Cut Line= 5
      2624067.86     13447584.76      2622542.94     13447634.35
      2622195.72      13448103.1      2622368.73     13450336.49
      2621879.62     13451529.03
#Sta/Elev= 30
  3236.7   52.38  3539.7   42.78    4140   36.05  4530.2   34.39  4620.3    36.3
    4632   34.27  4728.7   34.11  4939.5    35.1  4954.2   33.66    4975   24.53
  4989.2   21.46  4989.7   20.96  5006.9   21.46  5012.1      25  5018.9   32.53
  5033.5   34.21  5044.4   33.29  5325.6   38.92  6029.7   38.37  6290.5   39.68
  6340.6   42.19  6400.8   40.37  6882.3   42.14  7052.8   49.75    7133   51.31
  7183.2   51.16  7383.8   43.33  7514.1   40.59  8719.9   43.71  8874.8   43.38
#Mann= 6 ,-1 , 0
  3236.7    .045       0  4728.7     .07       0  4989.2    .035       0
  5006.9    .035       0  5044.4    .045       0  8719.9     .05       0
Bank Sta=4989.2,5006.9
XS Rating Curve= 0 ,0
Exp/Cntr=0.3,0.1

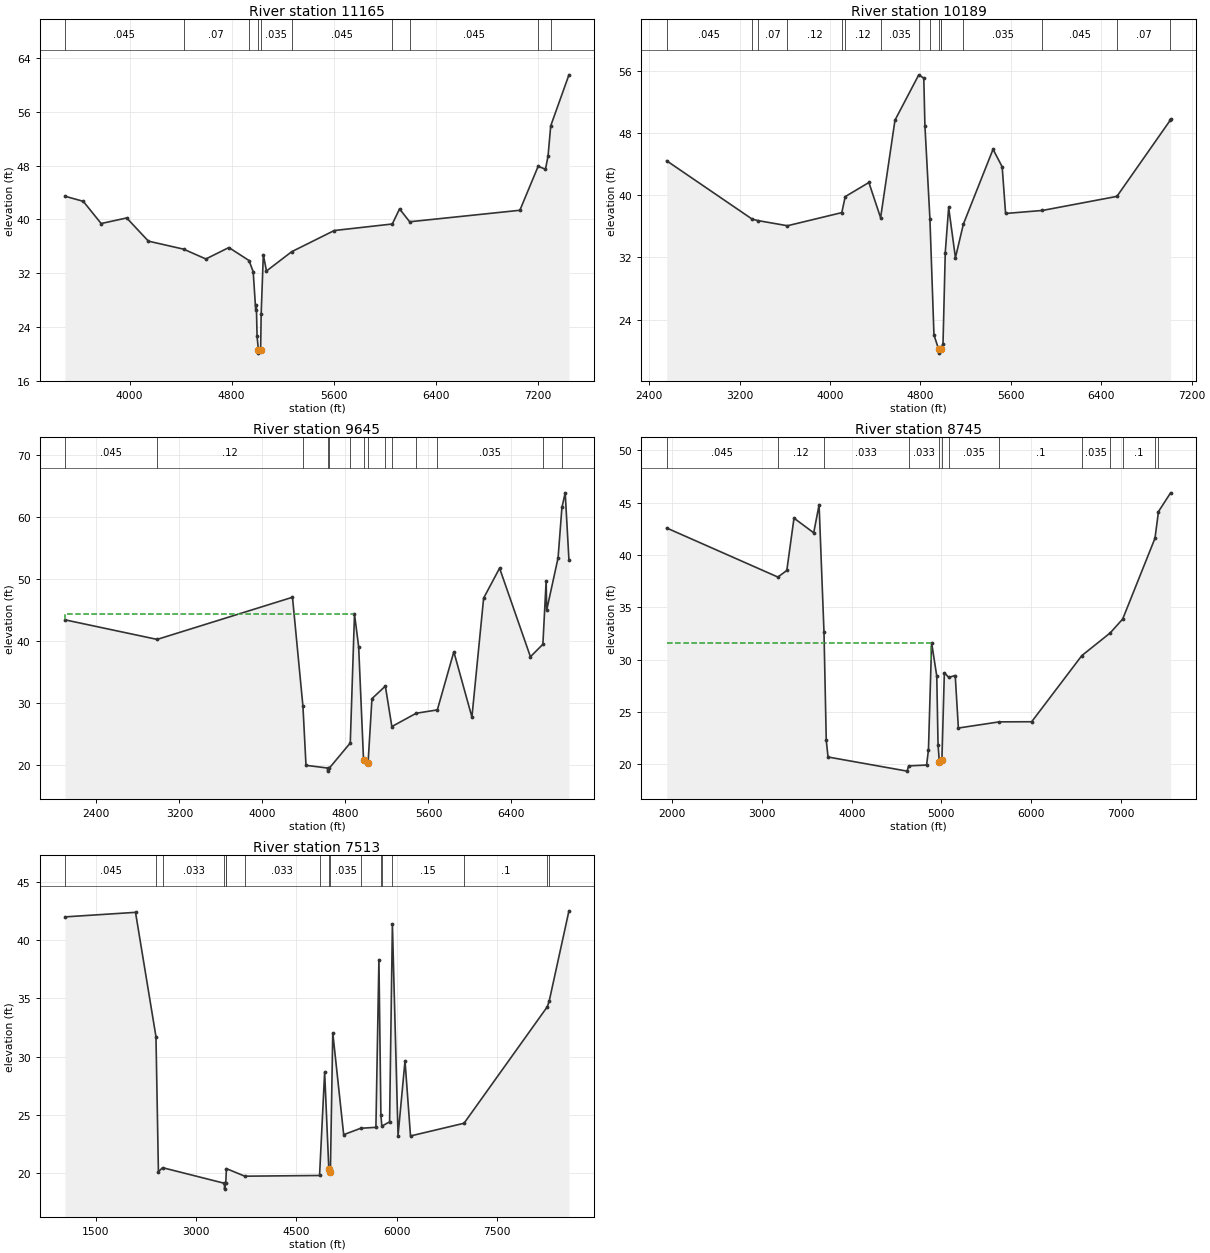
Type RM Length L Ch R = 1 ,11165   ,976,976,976
BEGIN DESCRIPTION:
Mapping XS eeea4b73
END DESCRIPTION:
XS GIS Cut Line= 4
      2623378.19     13447441.07      2621989.32     13447517.46
      2621815.71     13447968.85      2621635.16      13450038.3
#Sta/Elev= 30
  3494.1   43.44  3637.5   42.68  3777.7   39.38    3978   40.21  4148.3   36.76
    4424   35.57    4599   34.11  4779.2   35.81  4937.1   33.88  4970.1   32.21
  4989.4   26.59  4994.8   27.27  5000.3   22.63  5010.6   20.61  5011.1   20.11
  5028.3   20.61  5032.4   25.87  5049.4   34.74  5074.1   32.32  5271.7   35.19
  5605.7   38.34  6060.8   39.31  6117.7   41.56  6196.9   39.64  7061.2   41.35
  7204.3   47.88    7262   47.46  7282.1    49.4  7303.1    53.9    7446   61.49
#Mann= 10 ,-1 , 0
  3494.1    .045       0    4424     .07       0  4937.1     .07       0
  5010.6    .035       0  5028.3    .035       0  5271.7    .045       0
  6060.8    .035       0  6196.9    .045       0  7204.3     .07       0
  7303.1     .12       0
Bank Sta=5010.6,5028.3
XS Rating Curve= 0 ,0
Exp/Cntr=0.3,0.1

Type RM Length L Ch R = 1 ,10189   ,544,544,544
BEGIN DESCRIPTION:
Mapping XS b74372aa
END DESCRIPTION:
XS GIS Cut Line= 4
      2623156.82     13447309.13      2621040.48      13447505.1
      2621033.54     13447970.37      2621287.72     13449821.48
#Sta/Elev= 30
  2553.9   44.46  3309.7   36.95  3359.3   36.76  3622.8   36.09  4103.7   37.78
    4134   39.84  4343.3   41.66  4447.1   37.12  4574.3   49.69  4784.8   55.53
  4829.2    55.1  4839.2   48.98  4883.4      37  4919.2   22.04  4960.3   20.18
  4960.8   19.68  4978.2   20.18    4982   20.33  4999.2   20.86  5019.2   32.63
  5049.2   38.45  5109.2   31.97  5179.7   36.31    5442   45.94  5522.8   43.68
    5553   37.67  5879.2   38.06    6538   39.87  7009.3   49.67  7013.1   49.83
#Mann= 16 ,-1 , 0
  2553.9    .045       0  3309.7     .12       0  3359.3     .07       0
  3622.8     .12       0  4103.7     .07       0    4134     .12       0
  4447.1    .035       0  4784.8     .15       0  4883.4    .035       0
  4960.3     .05       0  4978.2    .035       0    4982     .15       0
  5179.7    .035       0  5879.2    .045       0    6538     .07       0
  7009.3     .05       0
Bank Sta=4960.3,4978.2
XS Rating Curve= 0 ,0
Exp/Cntr=0.3,0.1

Type RM Length L Ch R = 1 ,9645    ,900,900,900
BEGIN DESCRIPTION:
Mapping XS df8e3e67
END DESCRIPTION:
XS GIS Cut Line= 4
       2623245.7      13447219.3      2620789.47     13447130.88
      2620494.33     13447807.96      2620857.39     13449427.23
#Sta/Elev= 30
  2097.9   43.38  2985.7   40.22    4290   47.03  4390.7   29.42  4420.1   19.88
  4627.6   19.44  4628.1   18.94  4645.5   19.44  4846.8   23.49  4887.5   44.32
  4927.7      39  4974.6   20.79  5018.4   20.29  5055.7   30.65  5184.8   32.68
  5247.4   26.14  5482.1   28.29  5685.7   28.83  5844.7   38.22  6018.9   27.67
  6131.7   46.89  6285.4   51.73  6582.6   37.42  6702.7   39.43  6734.2   49.69
  6739.3   44.95    6849   53.39  6886.2   61.53  6917.8    63.9  6953.8   53.05
#Mann= 14 ,-1 , 0
  2097.9    .045       0  2985.7     .12       0  4390.7    .033       0
  4627.6    .033       0  4645.5    .033       0  4846.8    .033       0
  4974.6    .033       0  5018.4    .033       0  5184.8     .07       0
  5247.4     .15       0  5482.1      .1       0  5685.7    .035       0
  6702.7     .12       0  6886.2     .05       0
#XS Ineff= 2 , 0
       0  4887.5   44.32               0
Permanent Ineff=
       F       F
Bank Sta=4974.6,5018.4
XS Rating Curve= 0 ,0
Exp/Cntr=0.3,0.1

Type RM Length L Ch R = 1 ,8745    ,1232,1232,1232
BEGIN DESCRIPTION:
Mapping XS b159d237
END DESCRIPTION:
XS GIS Cut Line= 4
      2622875.26     13446939.84      2619991.87      13446880.1
      2619741.87     13447185.65      2620510.09     13449399.23
#Sta/Elev= 30
  1935.6   42.58  3176.4   37.89  3276.1   38.52  3356.2   43.52  3576.2   42.12
  3636.2    44.8  3690.8   32.64  3716.2   22.28  3736.2   20.69    4618   19.34
  4635.4   19.84  4835.4   19.92  4856.2   21.36  4891.4   31.62  4948.8   28.43
  4963.2   21.87  4977.5   20.24  5006.2   20.38  5033.5   28.74  5083.2    28.3
  5154.8   28.48    5190   23.46  5646.7   24.05  6007.6   24.06  6566.9   30.38
  6883.7   32.55  7023.1   33.88  7383.3    41.6  7422.3   44.15  7557.5   45.94
#Mann= 13 ,-1 , 0
  1935.6    .045       0  3176.4     .12       0  3690.8    .033       0
  4635.4    .033       0  4977.5    .033       0  5006.2    .033       0
  5083.2    .035       0  5646.7      .1       0  6566.9    .035       0
  6883.7     .12       0  7023.1      .1       0  7383.3    .035       0
  7422.3     .12       0
#XS Ineff= 2 , 0
       0  4884.9   31.55               0
Permanent Ineff=
       F       F
Bank Sta=4977.5,5006.2
XS Rating Curve= 0 ,0
Exp/Cntr=0.3,0.1

Type RM Length L Ch R = 1 ,7513    ,0,0,0
BEGIN DESCRIPTION:
CRESECENT VALLEY CREEK 16.0
END DESCRIPTION:
XS GIS Cut Line= 4
      2622671.82     13446413.01       2619122.8     13445985.04
       2618723.5      13446540.6      2620260.09       13449434.
#Sta/Elev= 30
  1040.2   41.98  2094.6   42.37  2400.5   31.71  2437.1   20.12  2499.1   20.47
  3424.8   19.13  3425.3   18.63  3443.7   19.13  3453.9   20.39  3728.5   19.74
  4846.5    19.8  4922.4   28.66 4985.05  20.349  5008.3   20.07  5043.9   32.04
  5207.2    23.3  5461.7   23.85    5689   23.93    5734   38.31  5763.7   24.97
  5777.5   24.03  5893.6    24.4  5935.4   41.35  6019.8   23.22  6124.1   29.63
  6206.3   23.19  7006.6   24.28  8252.6   34.28  8281.6    34.8  8575.2    42.5
#Mann= 17 ,-1 , 0
  1040.2    .045       0  2400.5    .094       0  2499.1    .033       0
  3424.8    .035       0  3443.7    .033       0  3453.9    .035       0
  3728.5    .033       0  4846.5    .035       0 4985.05    .035       0
  5008.3    .035       0  5461.7    .033       0  5763.7     .15       0
  5777.5    .033       0  5935.4     .15       0  7006.6      .1       0
  8252.6     .07       0  8281.6      .1       0
#XS Ineff= 2 , 0
       0  4922.4   28.66               0
Permanent Ineff=
       F       F
Bank Sta=4985.05,5008.3
XS Rating Curve= 0 ,0
Exp/Cntr=0.3,0.1

Chan Stop Cuts=-1
Use User Specified Reach Order=0
Composite Channel Slope=5