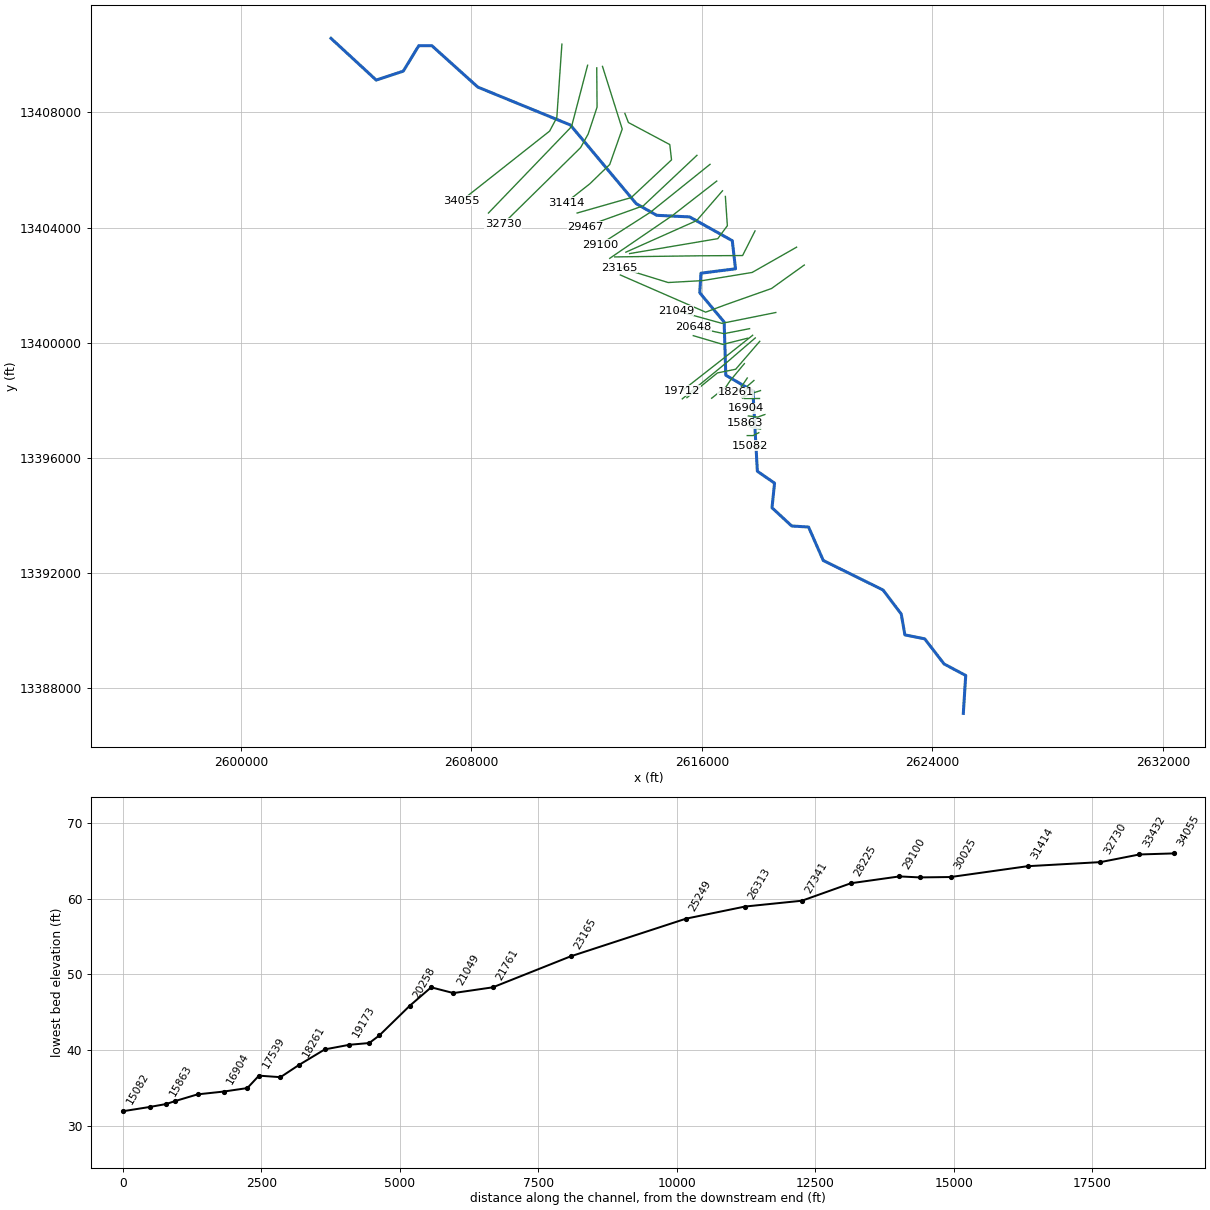
--- DRY KUY CREEK.prj (project) ---

Proj Title=DRY KUY CREEK Detailed Study
Current Plan=p01
Default Exp/Contr=0.3,0.1
English Units
Geom File=g01
Flow File=f01
Plan File=p01
BEGIN DESCRIPTION:
DRY KUY CREEK
END DESCRIPTION:

--- DRY KUY CREEK.p01 (plan) ---

Plan Title=Multiple Run
Short Identifier=Multiple
Geom File=g01
Flow File=f01
Subcritical Flow
K Sum by GR= 0
Std Step Tol= 0.01
Critical Tol= 0.01
Num of Std Step Trials= 20
Max Error Tol= 0.3
Flow Tol Ratio= 0.001
Split Flow NTrial= 30
Split Flow Tol= 0.02
Split Flow Ratio= 0.02
Log Output Level= 0
Friction Slope Method= 1
Unsteady Friction Slope Method= 2
Unsteady Bridges Friction Slope Method= 1
Parabolic Critical Depth
Global Vel Dist=  1 , 1 , 1
Global Log Level= 0
CheckData=True
Encroach Param= -1, 0, 0, 0
BEGIN DESCRIPTION:
Multiple Run
END DESCRIPTION:

--- DRY KUY CREEK.f01 (steady flow) ---

Flow Title=Multiple
Number of Profiles=4
Profile Names=10-year,50-year,100-year,500-year
River Rch & RM= DRY KUY CREEK,Reach-1,34055
     300     500     600     700
Boundary for River Rch & Prof#=DRY KUY CREEK,Reach-1,1
Up Type=0
Dn Type=3
Dn Slope=0.005
Boundary for River Rch & Prof#=DRY KUY CREEK,Reach-1,2
Up Type=0
Dn Type=3
Dn Slope=0.005
Boundary for River Rch & Prof#=DRY KUY CREEK,Reach-1,3
Up Type=0
Dn Type=3
Dn Slope=0.005
Boundary for River Rch & Prof#=DRY KUY CREEK,Reach-1,4
Up Type=0
Dn Type=3
Dn Slope=0.005

--- DRY KUY CREEK.g01 (geometry) ---

Geom Title=Existing Conditions

River Reach=DRY KUY CREEK,Reach-1
Reach XY= 30
      2603125.00     13410575.00      2604695.03     13409125.06
      2605634.68     13409435.20      2606172.57     13410319.48
      2606627.42     13410319.46      2608222.55     13408880.47
      2611434.79     13407564.48      2613718.81     13404832.82
      2614430.93     13404427.24      2615573.44     13404371.24
      2617055.21     13403545.09      2617167.33     13402568.48
      2615968.57     13402416.98      2615926.05     13401735.44
      2616772.93     13400719.14      2616830.37     13398872.30
      2617771.56     13398323.81      2617925.70     13395535.76
      2618521.96     13395123.58      2618433.99     13394267.99
      2619118.27     13393634.11      2619702.70     13393598.73
      2620214.51     13392435.52      2622288.25     13391411.39
      2622919.65     13390577.70      2623047.30     13389851.27
      2623735.08     13389713.91      2624407.87     13388841.30
      2625158.59     13388441.80      2625075.00     13387125.00

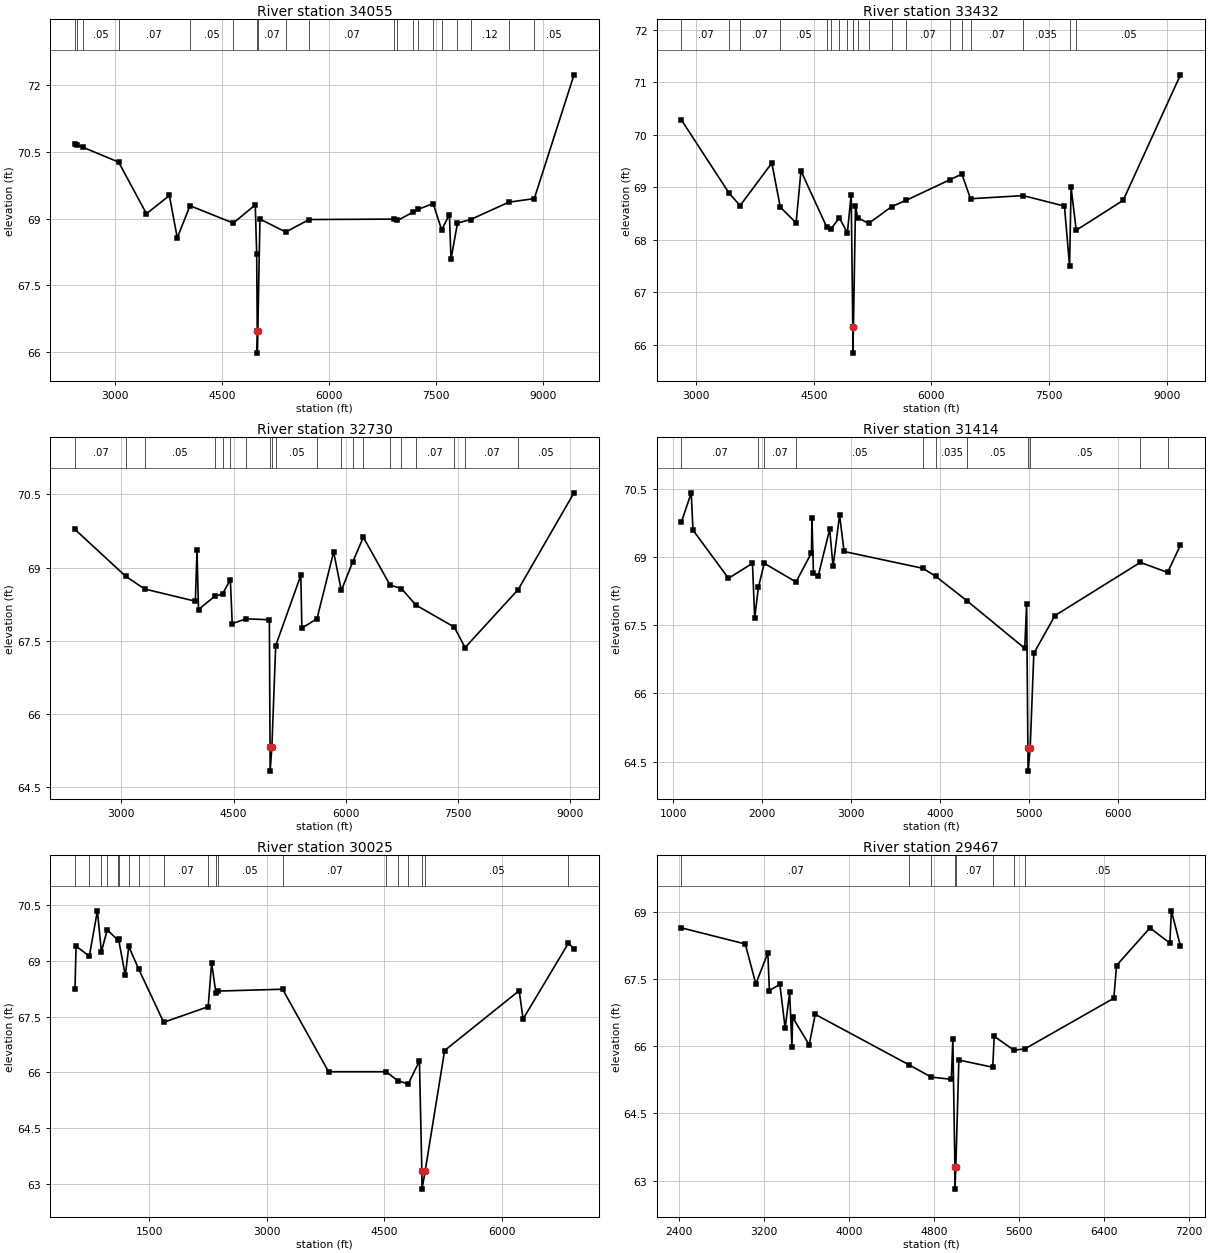
Type RM Length L Ch R = 1,34055,623,623,623
BEGIN DESCRIPTION:
Mapping XS e25f44ca
END DESCRIPTION:
XS GIS Cut Line= 4
      2611140.70     13410373.71      2610964.30     13407823.30
      2610714.80     13407352.44      2607655.22     13404934.43
#Sta/Elev= 30
  2443.5   70.68  2469.1   70.66  2559.0   70.60  3054.1   70.27  3444.6   69.11
  3765.4   69.52  3875.6   68.57  4054.8   69.29  4660.8   68.90  4968.2   69.31
  4988.3   68.21  4996.1   66.48  4996.6   65.98  5004.0   66.48  5034.1   68.99
  5396.0   68.70  5722.7   68.98  6914.2   68.99  6959.9   68.96  7183.5   69.15
  7252.5   69.21  7459.8   69.34  7578.6   68.75  7687.4   69.09  7709.9   68.09
  7800.5   68.90  7984.1   68.98  8519.6   69.37  8876.4   69.45  9432.6   72.23
#Mann=20,-1,0
  2443.5   0.035       0  2469.1    0.07       0  2559.0    0.05       0
  3054.1    0.07       0  4054.8    0.05       0  4660.8    0.07       0
  4996.1    0.05       0  5004.0    0.07       0  5396.0   0.035       0
  5722.7    0.07       0  6914.2   0.035       0  6959.9    0.07       0
  7183.5   0.035       0  7252.5    0.07       0  7459.8    0.07       0
  7578.6    0.12       0  7800.5    0.07       0  7984.1    0.12       0
  8519.6    0.05       0  8876.4    0.05       0
Bank Sta=4996.1,5004
Exp/Cntr=0.3,0.1

Type RM Length L Ch R = 1,33432,702,702,702
BEGIN DESCRIPTION:
Mapping XS 43d3dddd
END DESCRIPTION:
XS GIS Cut Line= 3
      2612033.17     13409640.39      2611475.71     13407508.33
      2608590.60     13404505.87
#Sta/Elev= 30
  2809.6   70.28  3420.0   68.88  3558.3   68.65  3962.5   69.46  4070.9   68.62
  4272.6   68.32  4334.6   69.31  4660.7   68.25  4721.4   68.21  4824.2   68.42
  4926.9   68.13  4975.4   68.86  4996.0   66.34  4996.5   65.84  5004.1   66.34
  5030.4   68.65  5057.2   68.42  5198.6   68.31  5491.2   68.63  5677.1   68.75
  6232.2   69.14  6388.1   69.25  6498.2   68.78  7169.8   68.84  7696.6   68.64
  7762.3   67.50  7781.5   69.00  7847.0   68.18  8446.3   68.75  9177.3   71.14
#Mann=20,-1,0
  2809.6    0.07       0  3420.0    0.05       0  3558.3    0.07       0
  4070.9    0.05       0  4660.7    0.07       0  4721.4    0.05       0
  4824.2    0.07       0  4926.9    0.05       0  4996.0    0.05       0
  5004.1    0.05       0  5057.2    0.07       0  5198.6    0.07       0
  5491.2   0.035       0  5677.1    0.07       0  6232.2    0.05       0
  6388.1    0.05       0  6498.2    0.07       0  7169.8   0.035       0
  7762.3   0.035       0  7847.0    0.05       0
Bank Sta=4996,5004.1
Exp/Cntr=0.3,0.1

Type RM Length L Ch R = 1,32730,1316,1316,1316
BEGIN DESCRIPTION:
Mapping XS 44671194
END DESCRIPTION:
XS GIS Cut Line= 5
      2612350.00     13409549.98      2612361.50     13408184.38
      2612051.61     13407248.27      2611791.19     13406779.52
      2609100.03     13404130.84
#Sta/Elev= 30
  2383.1   69.78  3060.3   68.82  3315.0   68.56  3990.4   68.31  4012.4   69.36
  4032.5   68.14  4248.2   68.41  4353.1   68.46  4458.0   68.75  4482.8   67.85
  4667.8   67.95  4978.8   67.93  4987.7   65.33  4989.2   64.83  5012.6   65.33
  5063.4   67.40  5398.8   68.84  5413.0   67.76  5614.4   67.95  5837.3   69.32
  5939.8   68.53  6093.5   69.12  6233.5   69.62  6591.2   68.64  6741.7   68.57
  6936.7   68.23  7448.7   67.78  7592.1   67.36  8301.8   68.55  9047.0   70.53
#Mann=20,-1,0
  2383.1    0.07       0  3060.3    0.05       0  3315.0    0.05       0
  4248.2   0.035       0  4353.1    0.07       0  4458.0    0.05       0
  4667.8    0.07       0  4987.7    0.05       0  5012.6    0.07       0
  5063.4    0.05       0  5614.4    0.05       0  5939.8    0.07       0
  6093.5    0.05       0  6233.5    0.05       0  6591.2    0.07       0
  6741.7    0.05       0  6936.7    0.07       0  7448.7    0.12       0
  7592.1    0.07       0  8301.8    0.05       0
Bank Sta=4987.7,5012.6
Exp/Cntr=0.3,0.1

Type RM Length L Ch R = 1,31414,1389,1389,1389
BEGIN DESCRIPTION:
Mapping XS c5c41804
END DESCRIPTION:
XS GIS Cut Line= 5
      2612550.01     13409599.96      2613234.90     13407424.73
      2612799.99     13406191.17      2612112.71     13405523.53
      2611279.10     13404866.45
#Sta/Elev= 30
  1093.9   69.77  1203.9   70.41  1223.4   69.59  1622.3   68.53  1891.8   68.86
  1916.8   67.66  1958.5   68.33  2024.4   68.86  2381.0   68.45  2555.0   69.09
  2560.3   69.86  2577.3   68.64  2630.3   68.58  2759.8   69.61  2797.5   68.79
  2870.9   69.92  2921.6   69.12  3806.3   68.75  3954.1   68.57  4306.0   68.03
  4952.0   66.99  4973.1   67.96  4987.4   64.79  4988.9   64.29  5012.9   64.79
  5054.1   66.88  5291.3   67.71  6251.1   68.88  6557.2   68.66  6702.0   69.26
#Mann=11,-1,0
  1093.9    0.07       0  1958.5    0.05       0  2024.4    0.07       0
  2381.0    0.05       0  3806.3    0.07       0  3954.1   0.035       0
  4306.0    0.05       0  4987.4    0.05       0  5012.9    0.05       0
  6251.1    0.07       0  6557.2    0.05       0
Bank Sta=4987.4,5012.9
Exp/Cntr=0.3,0.1

Type RM Length L Ch R = 1,30025,558,558,558
BEGIN DESCRIPTION:
Mapping XS ea8d28cf
END DESCRIPTION:
XS GIS Cut Line= 6
      2613326.89     13407967.45      2613450.00     13407650.00
      2614885.79     13406884.37      2614946.43     13406353.39
      2613547.01     13405042.79      2611670.19     13404506.56
#Sta/Elev= 30
   550.1   68.25   563.8   69.40   732.9   69.13   836.1   70.35   886.9   69.25
   962.0   69.84  1098.1   69.56  1106.2   69.59  1192.3   68.61  1237.3   69.39
  1361.5   68.79  1682.4   67.35  2250.6   67.77  2294.6   68.95  2349.1   68.14
  2371.0   68.19  3200.8   68.24  3787.9   66.02  4521.8   66.02  4669.6   65.78
  4804.7   65.69  4948.0   66.31  4978.5   63.36  4981.0   62.86  5022.0   63.36
  5269.4   66.59  6221.0   68.20  6271.6   67.44  6850.1   69.48  6921.4   69.33
#Mann=19,-1,0
   550.1    0.07       0   732.9    0.05       0   886.9    0.07       0
   962.0    0.05       0  1098.1    0.07       0  1106.2    0.05       0
  1237.3    0.07       0  1361.5    0.05       0  1682.4    0.07       0
  2250.6    0.05       0  2349.1    0.07       0  2371.0    0.05       0
  3200.8    0.07       0  4521.8    0.05       0  4669.6    0.07       0
  4804.7    0.05       0  4978.5    0.05       0  5022.0    0.05       0
  6850.1    0.07       0
Bank Sta=4978.5,5022
Exp/Cntr=0.3,0.1

Type RM Length L Ch R = 1,29467,367,367,367
BEGIN DESCRIPTION:
Mapping XS 1ad3fc03
END DESCRIPTION:
XS GIS Cut Line= 3
      2615827.82     13406510.78      2613969.61     13404760.15
      2611954.92     13404036.43
#Sta/Elev= 30
  2423.6   68.64  3023.9   68.28  3123.0   67.39  3236.3   68.08  3250.5   67.24
  3349.2   67.38  3398.9   66.40  3441.4   67.20  3462.4   65.99  3469.7   66.64
  3625.1   66.03  3681.7   66.71  4566.9   65.58  4773.1   65.31  4962.2   65.26
  4976.3   66.16  4995.6   63.31  4996.1   62.81  5004.4   63.31  5032.7   65.69
  5351.4   65.53  5365.4   66.22  5550.7   65.91  5654.1   65.94  6490.6   67.07
  6516.0   67.80  6830.3   68.64  7017.1   68.30  7032.2   69.02  7117.3   68.23
#Mann=8,-1,0
  2423.6    0.07       0  4566.9   0.035       0  4773.1    0.07       0
  4995.6    0.05       0  5004.4    0.07       0  5351.4    0.05       0
  5550.7    0.07       0  5654.1    0.05       0
Bank Sta=4995.6,5004.4
Exp/Cntr=0.3,0.1

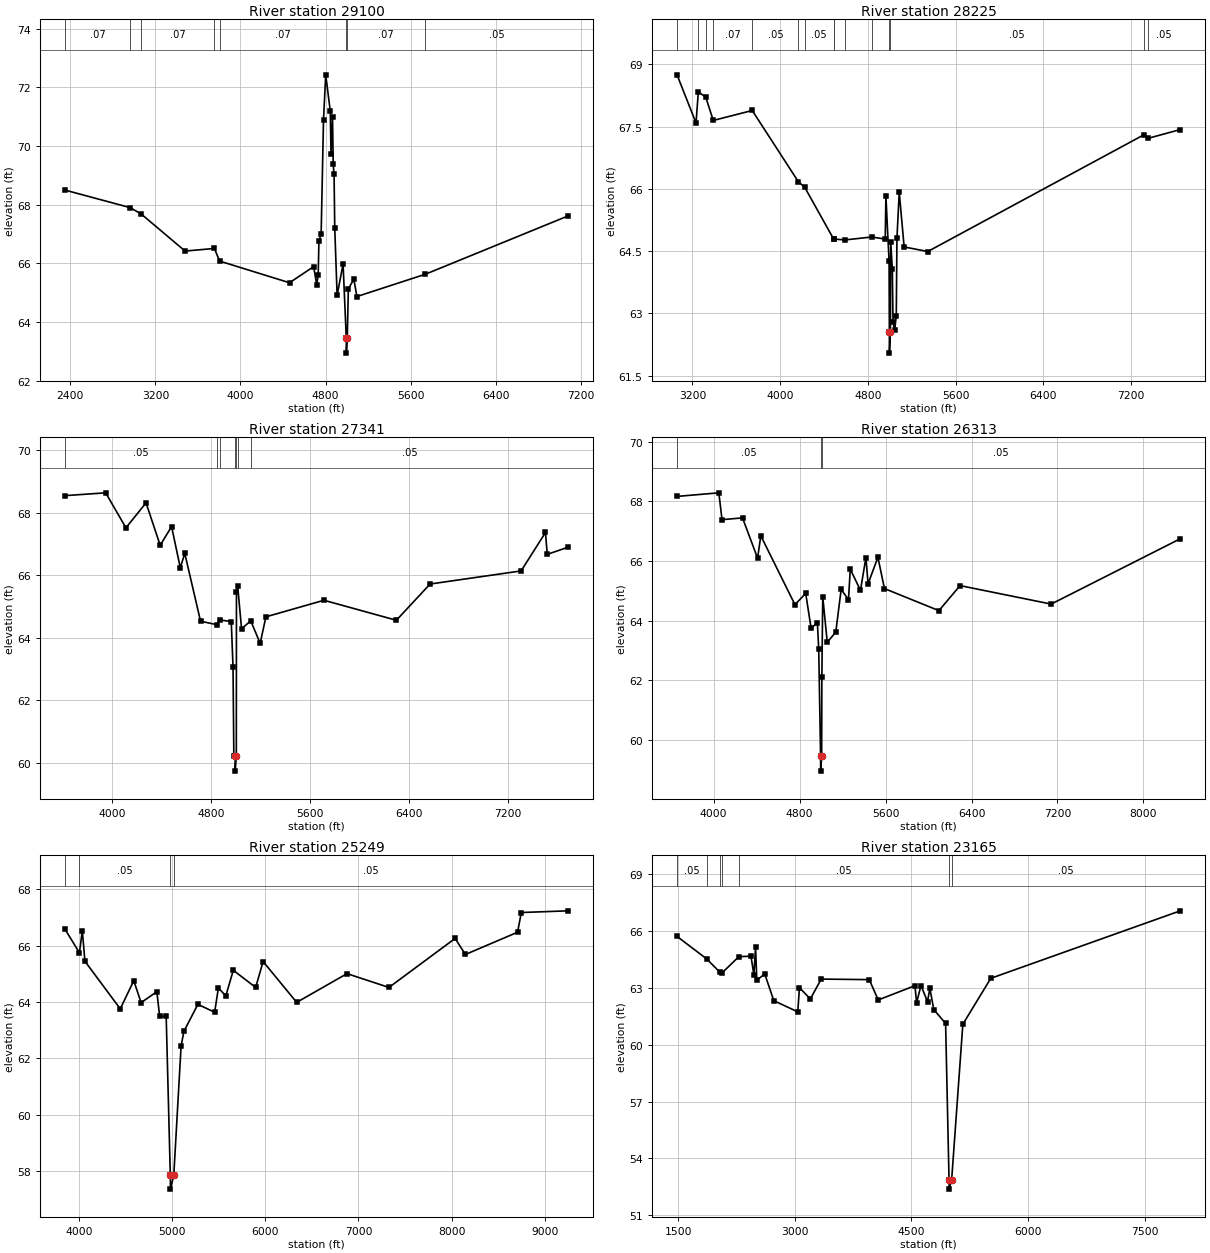
Type RM Length L Ch R = 1,29100,875,875,875
BEGIN DESCRIPTION:
Mapping XS 323480e5
END DESCRIPTION:
XS GIS Cut Line= 3
      2616282.23     13406197.22      2614215.45     13404536.08
      2612461.95     13403411.75
#Sta/Elev= 30
  2348.4   68.50  2963.1   67.90  3067.2   67.68  3478.8   66.42  3755.0   66.51
  3802.6   66.08  4461.2   65.34  4688.4   65.89  4717.1   65.27  4731.2   65.61
  4738.0   66.76  4758.8   67.01  4781.1   70.90  4802.0   72.43  4845.1   71.18
  4851.6   69.74  4866.0   70.98  4872.4   69.38  4880.4   69.04  4886.8   67.21
  4909.1   64.91  4965.2   65.98  4995.4   63.44  4995.9   62.94  5004.6   63.44
  5014.8   65.13  5066.4   65.46  5095.6   64.87  5739.2   65.63  7083.0   67.62
#Mann=8,-1,0
  2348.4    0.07       0  2963.1    0.05       0  3067.2    0.07       0
  3755.0   0.035       0  3802.6    0.07       0  4995.4    0.05       0
  5004.6    0.07       0  5739.2    0.05       0
Bank Sta=4995.4,5004.6
Exp/Cntr=0.3,0.1

Type RM Length L Ch R = 1,28225,884,884,884
BEGIN DESCRIPTION:
Mapping XS 0bb24a92
END DESCRIPTION:
XS GIS Cut Line= 3
      2616515.82     13405616.64      2614984.98     13404424.95
      2612800.00     13402931.51
#Sta/Elev= 30
  3060.0   68.75  3232.9   67.59  3254.2   68.34  3321.9   68.21  3390.3   67.65
  3745.3   67.89  4166.4   66.17  4223.5   66.04  4487.4   64.79  4487.6   64.79
  4593.6   64.77  4834.5   64.84  4957.4   64.79  4963.8   65.82  4992.7   64.25
  4995.2   62.54  4995.7   62.04  5004.8   62.54  5007.4   64.73  5022.3   64.06
  5028.4   62.79  5043.3   62.59  5058.2   62.94  5064.3   64.81  5085.2   65.92
  5130.0   64.60  5345.3   64.49  7312.1   67.30  7354.9   67.22  7646.6   67.43
#Mann=15,-1,0
  3060.0    0.05       0  3254.2    0.07       0  3321.9    0.05       0
  3390.3    0.07       0  3745.3    0.05       0  4166.4    0.07       0
  4223.5    0.05       0  4487.4    0.07       0  4487.6    0.05       0
  4593.6    0.07       0  4834.5    0.05       0  4995.2    0.05       0
  5004.8    0.05       0  7312.1    0.07       0  7354.9    0.05       0
Bank Sta=4995.2,5004.8
Exp/Cntr=0.3,0.1

Type RM Length L Ch R = 1,27341,1028,1028,1028
BEGIN DESCRIPTION:
Mapping XS a5110d64
END DESCRIPTION:
XS GIS Cut Line= 3
      2616715.46     13405278.09      2615821.37     13404245.11
      2613360.79     13403146.20
#Sta/Elev= 30
  3621.9   68.55  3950.6   68.64  4114.0   67.52  4276.3   68.32  4390.4   66.96
  4482.5   67.56  4552.7   66.24  4588.9   66.70  4716.1   64.53  4845.4   64.42
  4869.7   64.57  4964.0   64.52  4978.3   63.06  4984.8   60.23  4995.2   60.23
  4995.7   59.73  5004.9   60.23  5006.0   65.46  5015.4   65.67  5047.0   64.29
  5121.6   64.54  5197.2   63.82  5243.7   64.67  5712.1   65.20  6296.6   64.56
  6568.4   65.72  7303.1   66.14  7499.8   67.37  7514.0   66.67  7682.9   66.90
#Mann=7,-1,0
  3621.9    0.05       0  4845.4    0.07       0  4869.7    0.05       0
  4995.2    0.05       0  5004.9    0.05       0  5015.4    0.07       0
  5121.6    0.05       0
Bank Sta=4995.2,5004.9
Exp/Cntr=0.3,0.1

Type RM Length L Ch R = 1,26313,1064,1064,1064
BEGIN DESCRIPTION:
Mapping XS 23564807
END DESCRIPTION:
XS GIS Cut Line= 4
      2616815.60     13405082.90      2616884.06     13404065.77
      2616551.54     13403615.89      2613490.37     13403097.55
#Sta/Elev= 30
  3659.0   68.17  4047.8   68.29  4077.8   67.39  4268.3   67.45  4408.6   66.10
  4438.7   66.85  4756.4   64.54  4856.6   64.92  4906.7   63.75  4965.2   63.94
  4977.8   63.04  4995.1   59.46  4995.6   58.96  5005.0   59.46  5006.9   62.10
  5015.1   64.81  5057.0   63.28  5136.4   63.62  5186.5   65.05  5254.6   64.71
  5271.5   65.73  5366.2   65.02  5416.9   66.12  5437.2   65.24  5528.5   66.13
  5589.3   65.08  6096.4   64.34  6292.8   65.18  7141.1   64.56  8342.6   66.75
#Mann=3,-1,0
  3659.0    0.05       0  4995.1    0.05       0  5005.0    0.05       0
Bank Sta=4995.1,5005
Exp/Cntr=0.3,0.1

Type RM Length L Ch R = 1,25249,2084,2084,2084
BEGIN DESCRIPTION:
Mapping XS 65e80852
END DESCRIPTION:
XS GIS Cut Line= 4
      2617844.86     13403884.53      2617413.61     13403029.65
      2615915.78     13403020.54      2612972.29     13402981.85
#Sta/Elev= 30
  3851.1   66.59  4006.4   65.75  4037.4   66.54  4065.3   65.45  4444.5   63.76
  4589.4   64.76  4668.2   63.98  4837.2   64.37  4867.2   63.49  4937.2   63.50
  4981.5   57.86  4983.2   57.36  5018.9   57.86  5097.2   62.44  5127.2   62.96
  5277.2   63.92  5457.2   63.64  5497.2   64.50  5577.2   64.22  5657.2   65.13
  5897.2   64.52  5977.2   65.44  6337.2   63.99  6877.3   65.01  7327.3   64.52
  8037.4   66.26  8147.4   65.69  8707.4   66.48  8747.4   67.18  9250.2   67.24
#Mann=4,-1,0
  3851.1   0.035       0  4006.4    0.05       0  4981.5    0.05       0
  5018.9    0.05       0
Bank Sta=4981.5,5018.9
Exp/Cntr=0.3,0.1

Type RM Length L Ch R = 1,23165,1404,1404,1404
BEGIN DESCRIPTION:
Mapping XS 6aa52359
END DESCRIPTION:
XS GIS Cut Line= 5
      2619288.02     13403320.29      2617744.70     13402442.29
      2616023.41     13402158.67      2614829.38     13402092.02
      2613145.36     13402612.85
#Sta/Elev= 30
  1481.5   65.71  1861.2   64.53  2036.6   63.81  2064.2   63.80  2277.0   64.64
  2433.4   64.67  2470.8   63.68  2492.5   65.16  2508.3   63.40  2610.7   63.73
  2727.5   62.32  3035.8   61.73  3057.5   63.01  3197.3   62.41  3337.9   63.46
  3956.1   63.43  4071.7   62.36  4543.9   63.11  4566.0   62.22  4622.1   63.12
  4706.1   62.27  4736.5   62.97  4787.2   61.85  4939.2   61.12  4983.2   52.88
  4984.7   52.38  5017.1   52.88  5161.2   61.08  5520.9   63.50  7960.2   67.06
#Mann=7,-1,0
  1481.5    0.05       0  1861.2    0.07       0  2036.6    0.05       0
  2064.2    0.07       0  2277.0    0.05       0  4983.2    0.05       0
  5017.1    0.05       0
Bank Sta=4983.2,5017.1
Exp/Cntr=0.3,0.1

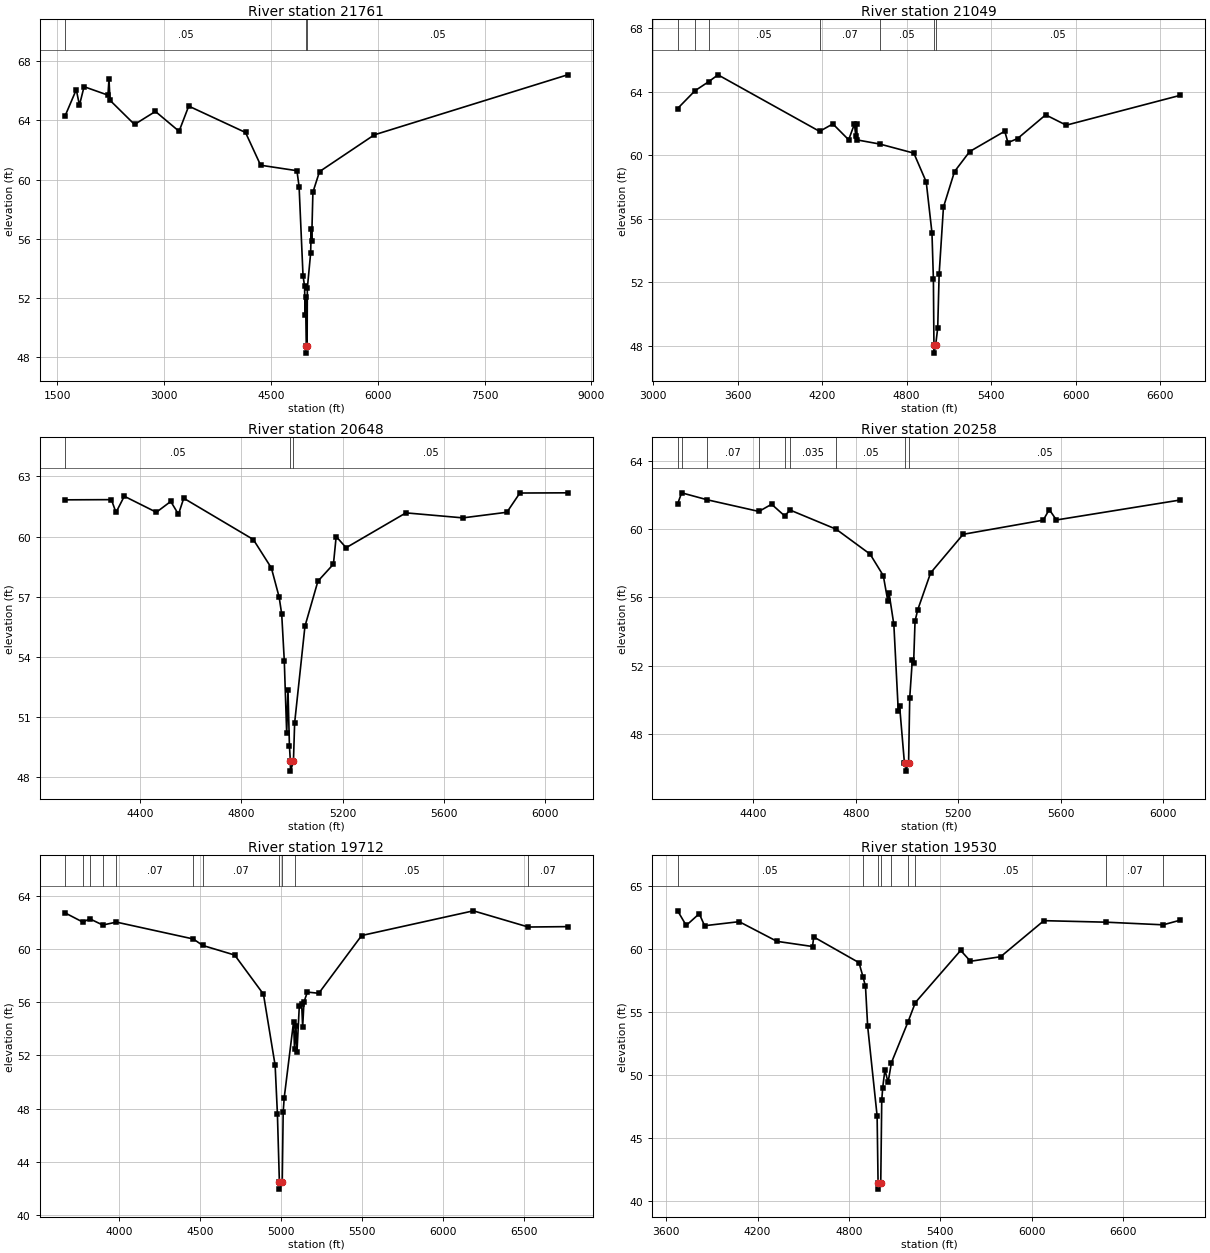
Type RM Length L Ch R = 1,21761,712,712,712
BEGIN DESCRIPTION:
Mapping XS d84984b3
END DESCRIPTION:
XS GIS Cut Line= 5
      2619554.00     13402699.96      2618416.85     13401883.99
      2616818.56     13401319.15      2616131.06     13401062.21
      2613169.38     13402354.10
#Sta/Elev= 30
  1604.4   64.27  1764.0   66.07  1808.2   65.02  1873.3   66.27  2208.5   65.70
  2223.3   66.78  2238.0   65.35  2581.8   63.72  2875.3   64.60  3207.5   63.26
  3343.1   64.96  4140.8   63.18  4352.9   60.97  4862.9   60.60  4893.2   59.53
  4948.5   53.52  4969.9   52.82  4978.8   50.89  4984.1   52.11  4994.2   48.79
  4994.7   48.29  5005.9   48.79  5009.1   52.67  5055.3   55.03  5064.3   56.68
  5069.7   55.87  5087.3   59.15  5180.2   60.54  5949.9   63.02  8664.3   67.07
#Mann=3,-1,0
  1604.4    0.05       0  4994.2    0.05       0  5005.9    0.05       0
Bank Sta=4994.2,5005.9
Exp/Cntr=0.3,0.1

Type RM Length L Ch R = 1,21049,401,401,401
BEGIN DESCRIPTION:
Mapping XS a4105589
END DESCRIPTION:
XS GIS Cut Line= 3
      2618566.08     13401050.41      2616694.95     13400674.24
      2615093.38     13401116.95
#Sta/Elev= 30
  3173.5   62.93  3297.1   64.05  3392.9   64.61  3460.2   65.05  4181.9   61.49
  4276.2   61.96  4388.3   60.96  4429.2   61.95  4439.2   61.20  4444.3   61.97
  4449.6   60.95  4610.9   60.69  4851.2   60.12  4939.2   58.31  4980.0   55.11
  4990.2   52.18  4994.0   48.03  4994.5   47.53  5006.1   48.03  5020.8   49.11
  5031.0   52.50  5061.6   56.72  5140.1   58.96  5248.0   60.22  5497.0   61.50
  5519.7   60.78  5588.4   61.04  5787.5   62.53  5933.7   61.88  6743.7   63.76
#Mann=7,-1,0
  3173.5    0.05       0  3297.1   0.035       0  3392.9    0.05       0
  4181.9    0.07       0  4610.9    0.05       0  4994.0    0.05       0
  5006.1    0.05       0
Bank Sta=4994,5006.1
Exp/Cntr=0.3,0.1

Type RM Length L Ch R = 1,20648,390,390,390
BEGIN DESCRIPTION:
Mapping XS 951e8649
END DESCRIPTION:
XS GIS Cut Line= 3
      2617655.07     13400489.36      2616769.60     13400315.74
      2615710.61     13400541.42
#Sta/Elev= 30
  4103.6   61.83  4287.1   61.84  4305.3   61.20  4338.0   62.01  4464.7   61.21
  4521.5   61.75  4552.0   61.11  4572.8   61.91  4847.6   59.85  4918.9   58.43
  4949.5   56.98  4959.7   56.13  4969.9   53.80  4979.4   50.17  4984.5   52.36
  4990.2   49.54  4993.9   48.79  4994.4   48.29  5006.1   48.79  5010.8   50.70
  5051.5   55.52  5102.7   57.77  5164.0   58.62  5174.8   60.00  5214.1   59.44
  5450.3   61.18  5675.2   60.93  5849.0   61.21  5900.2   62.17  6088.7   62.18
#Mann=3,-1,0
  4103.6    0.05       0  4993.9    0.05       0  5006.1    0.05       0
Bank Sta=4993.9,5006.1
Exp/Cntr=0.3,0.1

Type RM Length L Ch R = 1,20258,546,546,546
BEGIN DESCRIPTION:
Mapping XS bfe3ce24
END DESCRIPTION:
XS GIS Cut Line= 3
      2617594.27     13400159.49      2616726.20     13399942.47
      2615701.89     13400246.29
#Sta/Elev= 30
  4104.0   61.48  4119.7   62.13  4220.3   61.72  4421.4   61.04  4471.1   61.46
  4522.0   60.78  4543.4   61.12  4723.1   60.00  4855.7   58.54  4907.3   57.28
  4924.6   55.82  4929.8   56.25  4948.5   54.42  4965.8   49.36  4971.0   49.64
  4989.7   46.33  4993.9   46.33  4994.4   45.83  5006.1   46.33  5010.5   50.12
  5020.5   52.31  5025.7   52.15  5031.3   54.62  5041.8   55.28  5092.1   57.44
  5219.1   59.70  5532.0   60.53  5555.4   61.15  5583.4   60.54  6067.2   61.71
#Mann=9,-1,0
  4104.0    0.07       0  4119.7    0.05       0  4220.3    0.07       0
  4421.4   0.035       0  4522.0    0.05       0  4543.4   0.035       0
  4723.1    0.05       0  4993.9    0.05       0  5006.1    0.05       0
Bank Sta=4993.9,5006.1
Exp/Cntr=0.3,0.1

Type RM Length L Ch R = 1,19712,182,182,182
BEGIN DESCRIPTION:
Mapping XS 33a536ca
END DESCRIPTION:
XS GIS Cut Line= 3
      2617763.20     13400259.95      2616718.95     13399431.84
      2615324.35     13398339.06
#Sta/Elev= 30
  3666.7   62.74  3777.6   62.04  3820.0   62.29  3900.3   61.82  3984.5   62.04
  4459.3   60.77  4518.2   60.28  4715.0   59.56  4892.9   56.61  4965.0   51.25
  4979.0   47.60  4991.3   42.43  4991.8   41.93  5008.8   42.43  5014.7   47.75
  5021.1   48.82  5078.9   54.54  5084.7   52.45  5093.4   54.24  5099.7   52.24
  5114.2   55.71  5128.7   55.90  5135.0   54.13  5143.1   56.02  5163.9   56.77
  5234.5   56.68  5499.3   61.03  6189.2   62.89  6528.7   61.67  6771.2   61.70
#Mann=11,-1,0
  3666.7    0.07       0  3777.6    0.05       0  3820.0    0.07       0
  3900.3    0.05       0  3984.5    0.07       0  4459.3    0.05       0
  4518.2    0.07       0  4991.3    0.05       0  5008.8    0.07       0
  5084.7    0.05       0  6528.7    0.07       0
Bank Sta=4991.3,5008.8
Exp/Cntr=0.3,0.1

Type RM Length L Ch R = 1,19530,357,357,357
BEGIN DESCRIPTION:
Mapping XS 409d762f
END DESCRIPTION:
XS GIS Cut Line= 3
      2617852.63     13400167.08      2616858.70     13399312.05
      2615319.53     13398050.36
#Sta/Elev= 30
  3674.7   63.00  3731.2   61.84  3816.7   62.77  3851.9   61.82  4079.1   62.14
  4327.1   60.58  4560.8   60.17  4568.4   60.93  4865.8   58.89  4892.1   57.77
  4908.6   57.01  4922.9   53.83  4984.9   46.74  4991.2   41.43  4991.7   40.93
  5008.8   41.43  5015.3   47.96  5021.7   48.98  5036.1   50.39  5056.9   49.39
  5078.9   50.96  5187.1   54.17  5236.2   55.73  5533.7   59.86  5598.0   59.00
  5796.1   59.36  6080.3   62.22  6487.3   62.10  6863.6   61.89  6976.0   62.26
#Mann=9,-1,0
  3674.7    0.05       0  4892.1    0.07       0  4991.2    0.05       0
  5008.8    0.07       0  5078.9    0.05       0  5187.1    0.07       0
  5236.2    0.05       0  6487.3    0.07       0  6863.6    0.05       0
Bank Sta=4991.2,5008.8
Exp/Cntr=0.3,0.1

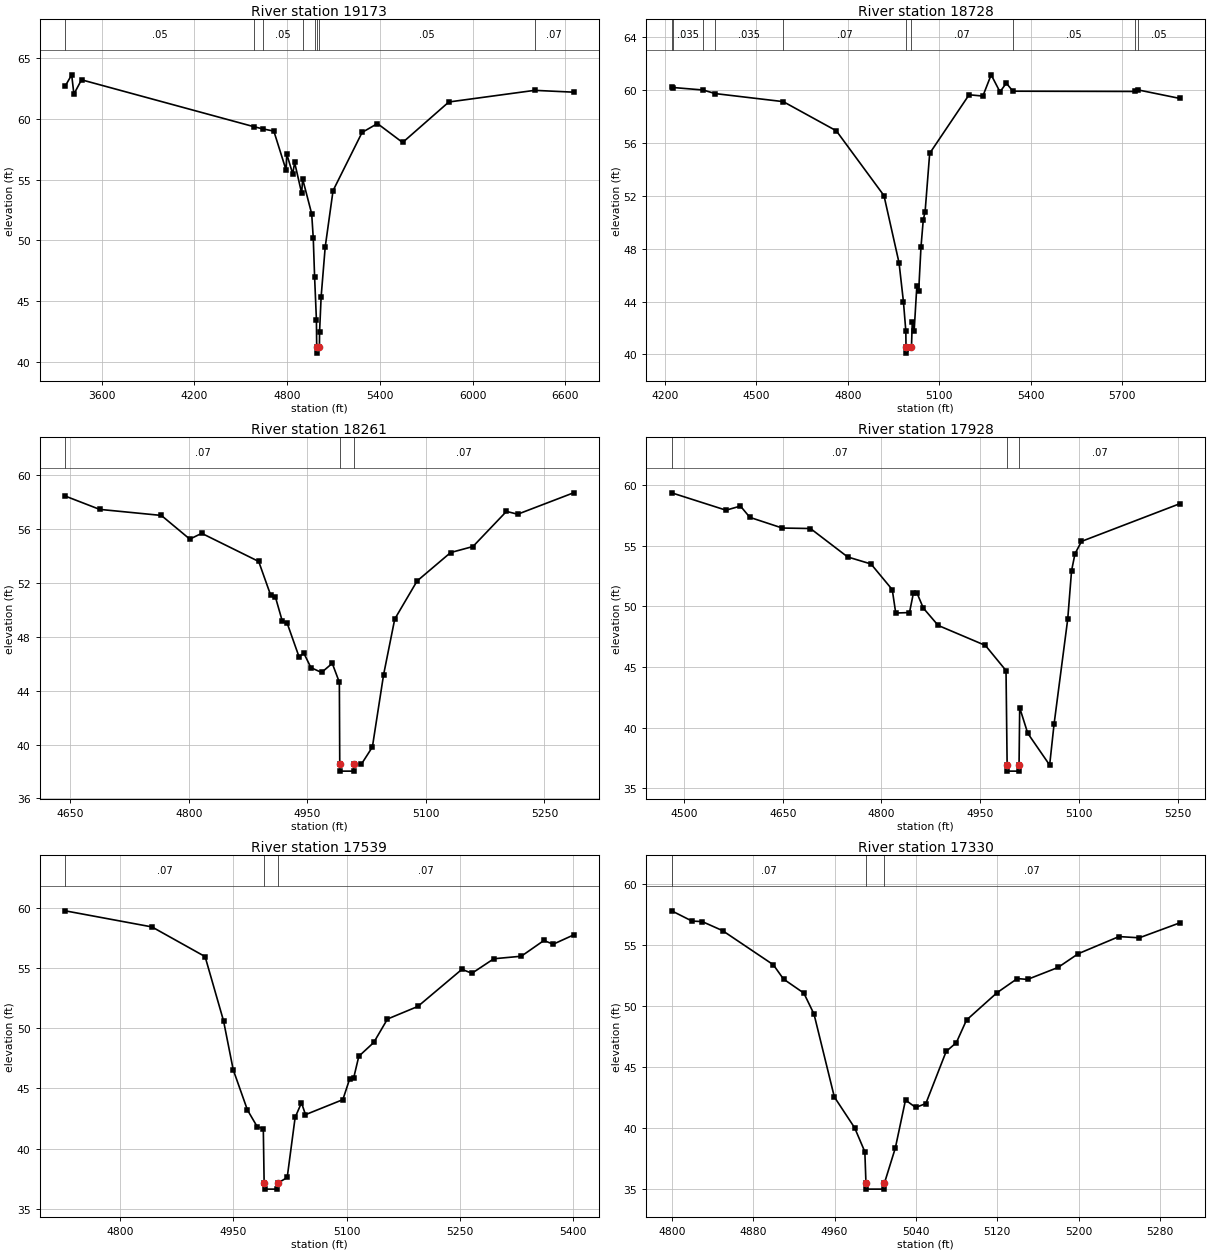
Type RM Length L Ch R = 1,19173,445,445,445
BEGIN DESCRIPTION:
Mapping XS 33a7b9ef
END DESCRIPTION:
XS GIS Cut Line= 4
      2618008.91     13400049.93      2617173.51     13399079.83
      2616540.54     13398951.95      2615481.54     13398093.06
#Sta/Elev= 30
  3363.7   62.72  3405.6   63.65  3419.9   62.06  3469.2   63.24  4582.8   59.38
  4642.6   59.19  4713.8   59.01  4792.4   55.82  4797.5   57.11  4836.2   55.48
  4848.3   56.43  4893.9   53.88  4900.2   55.06  4958.7   52.19  4968.9   50.19
  4977.7   46.95  4989.3   43.45  4991.2   41.20  4991.7   40.70  5008.8   41.20
  5009.7   42.44  5019.9   45.36  5046.2   49.45  5097.0   54.10  5284.9   58.90
  5384.3   59.63  5547.3   58.07  5846.2   61.41  6401.3   62.37  6653.2   62.22
#Mann=8,-1,0
  3363.7    0.05       0  4582.8   0.035       0  4642.6    0.05       0
  4900.2    0.07       0  4977.7    0.05       0  4991.2    0.05       0
  5008.8    0.05       0  6401.3    0.07       0
Bank Sta=4991.2,5008.8
Exp/Cntr=0.3,0.1

Type RM Length L Ch R = 1,18728,467,467,467
BEGIN DESCRIPTION:
DRY KUY CREEK 39.0
END DESCRIPTION:
XS GIS Cut Line= 4
      2617475.01     13399275.01      2616975.00     13398675.00
      2616837.80     13398469.19      2616338.66     13398072.44
#Sta/Elev= 30
  4223.0   60.22  4226.9   60.21  4326.1   60.02  4365.4   59.75  4588.6   59.14
  4762.6   56.93  4918.8   52.02  4968.2   46.93  4982.6   43.98  4990.4   41.77
  4991.0   40.59  4991.5   40.09  5009.0   40.59  5011.6   42.47  5017.6   41.74
  5026.6   45.20  5032.6   44.81  5040.1   48.13  5047.6   50.19  5053.6   50.80
  5068.6   55.22  5197.8   59.66  5242.9   59.56  5270.1   61.17  5299.0   59.88
  5319.8   60.54  5341.2   59.93  5740.5   59.91  5751.0   60.03  5889.0   59.38
#Mann=10,-1,0
  4223.0    0.05       0  4226.9   0.035       0  4326.1    0.05       0
  4365.4   0.035       0  4588.6    0.07       0  4991.0    0.05       0
  5009.0    0.07       0  5341.2    0.05       0  5740.5   0.035       0
  5751.0    0.05       0
Bank Sta=4991,5009
Exp/Cntr=0.3,0.1

Type RM Length L Ch R = 1,18261,333,333,333
BEGIN DESCRIPTION:
DRY KUY CREEK 38.0
END DESCRIPTION:
XS GIS Cut Line= 3
      2617575.00     13398775.00      2617375.00     13398475.00
      2617175.00     13398275.00
#Sta/Elev= 30
  4643.5   58.47  4687.1   57.48  4765.2   57.03  4801.2   55.27  4816.3   55.70
  4888.4   53.61  4903.4   51.13  4909.4   51.00  4918.4   49.15  4924.4   49.03
  4939.5   46.52  4945.5   46.80  4954.5   45.72  4968.0   45.36  4981.5   46.04
  4990.5   44.63  4991.0   38.53  4991.5   38.03  5008.6   38.03  5009.1   38.53
  5018.2   38.53  5032.3   39.82  5046.5   45.20  5060.6   49.33  5088.9   52.16
  5131.3   54.27  5159.6   54.72  5202.0   57.33  5216.2   57.12  5286.9   58.71
#Mann=3,-1,0
  4643.5    0.07       0  4991.0    0.05       0  5009.1    0.07       0
Bank Sta=4991,5009.1
Exp/Cntr=0.3,0.1

Type RM Length L Ch R = 1,17928,389,389,389
BEGIN DESCRIPTION:
Mapping XS 5a97d377
END DESCRIPTION:
XS GIS Cut Line= 5
      2617807.49     13398689.66      2617580.93     13398494.34
      2617528.84     13398330.28      2617474.16     13398145.38
      2617375.19     13398101.11
#Sta/Elev= 30
  4481.2   59.34  4563.8   57.91  4585.7   58.25  4600.0   57.32  4649.3   56.44
  4692.1   56.40  4748.6   54.06  4784.1   53.48  4816.4   51.37  4821.7   49.44
  4842.6   49.48  4848.7   51.12  4853.9   51.10  4863.6   49.85  4886.2   48.42
  4958.0   46.77  4989.3   44.70  4991.0   36.92  4991.5   36.42  5008.6   36.42
  5009.1   36.92  5010.1   41.64  5022.3   39.54  5055.6   36.92  5062.3   40.28
  5083.1   48.95  5088.9   52.92  5094.1   54.32  5104.0   55.34  5253.7   58.45
#Mann=3,-1,0
  4481.2    0.07       0  4991.0    0.05       0  5009.1    0.07       0
Bank Sta=4991,5009.1
Exp/Cntr=0.3,0.1

Type RM Length L Ch R = 1,17539,209,209,209
BEGIN DESCRIPTION:
Mapping XS 96e6ac23
END DESCRIPTION:
XS GIS Cut Line= 3
      2618034.05     13398338.09      2617627.80     13398205.28
      2617422.06     13398072.45
#Sta/Elev= 30
  4727.9   59.79  4842.6   58.45  4912.9   55.98  4937.3   50.63  4950.1   46.56
  4968.9   43.21  4981.9   41.81  4989.9   41.66  4991.0   37.12  4991.5   36.62
  5008.6   36.62  5009.1   37.12  5021.5   37.59  5032.0   42.59  5040.4   43.81
  5045.7   42.82  5095.1   44.07  5104.2   45.81  5109.4   45.87  5116.2   47.68
  5136.0   48.83  5154.1   50.78  5194.3   51.83  5252.6   54.92  5265.8   54.59
  5294.8   55.80  5331.1   56.01  5361.0   57.32  5373.3   57.01  5400.2   57.78
#Mann=3,-1,0
  4727.9    0.07       0  4991.0    0.05       0  5009.1    0.07       0
Bank Sta=4991,5009.1
Exp/Cntr=0.3,0.1

Type RM Length L Ch R = 1,17330,426,426,426
BEGIN DESCRIPTION:
DRY KUY CREEK 36.0
END DESCRIPTION:
XS GIS Cut Line= 3
      2617975.02     13398075.00      2617775.00     13398075.00
      2617475.02     13398075.00
#Sta/Elev= 30
  4799.8   57.78  4819.8   56.94  4829.8   56.90  4849.8   56.16  4899.8   53.36
  4909.8   52.19  4929.8   51.04  4939.8   49.32  4959.8   42.53  4979.8   40.00
  4989.8   38.04  4990.9   35.48  4991.4   34.98  5008.6   34.98  5009.1   35.48
  5019.8   38.35  5029.8   42.28  5039.8   41.67  5049.8   41.99  5069.8   46.26
  5079.8   46.98  5089.8   48.83  5119.8   51.07  5139.8   52.23  5149.8   52.16
  5179.8   53.14  5199.8   54.27  5239.8   55.67  5259.8   55.57  5299.8   56.80
#Mann=3,-1,0
  4799.8    0.07       0  4990.9    0.05       0  5009.1    0.07       0
Bank Sta=4990.9,5009.1
Exp/Cntr=0.3,0.1

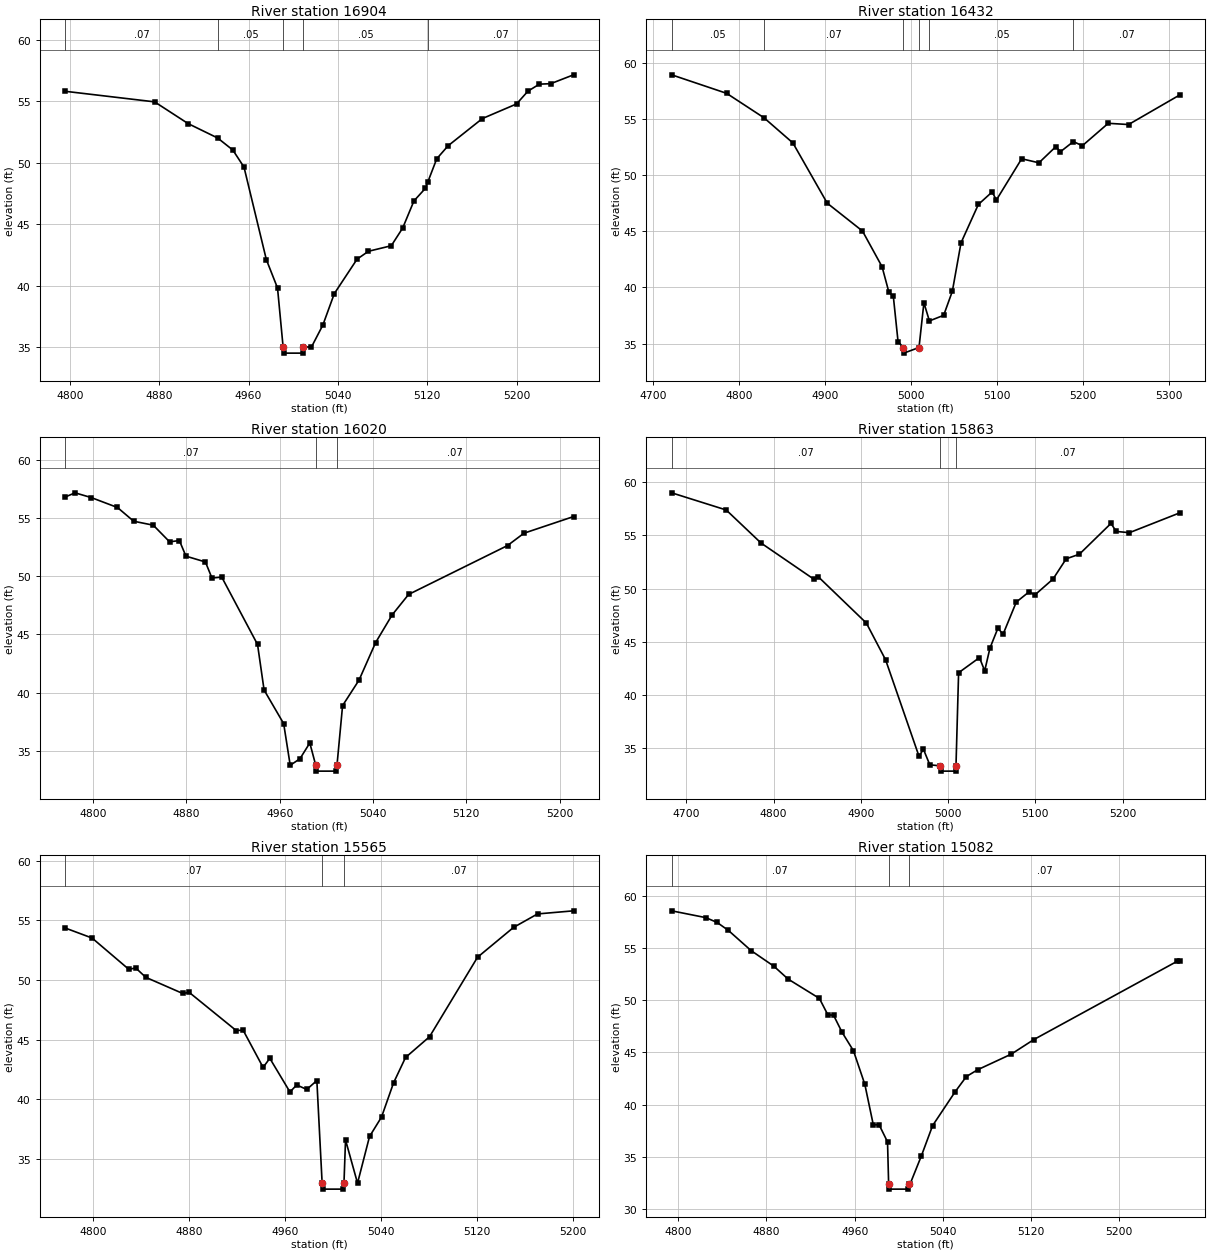
Type RM Length L Ch R = 1,16904,472,472,472
BEGIN DESCRIPTION:
DRY KUY CREEK 35.0
END DESCRIPTION:
XS GIS Cut Line= 3
      2617974.97     13397775.00      2617775.00     13397775.00
      2617525.02     13397725.00
#Sta/Elev= 30
  4795.9   55.83  4875.9   54.97  4905.9   53.20  4932.3   52.03  4945.9   51.05
  4955.9   49.66  4975.9   42.13  4985.9   39.82  4990.9   35.02  4991.4   34.52
  5008.6   34.52  5009.1   35.02  5016.3   35.02  5026.5   36.81  5036.7   39.36
  5057.1   42.17  5067.3   42.81  5087.7   43.26  5097.9   44.70  5108.0   46.91
  5118.2   47.93  5120.4   48.45  5128.4   50.34  5138.6   51.40  5169.2   53.61
  5199.8   54.80  5210.0   55.84  5220.2   56.41  5230.4   56.45  5250.8   57.17
#Mann=5,-1,0
  4795.9    0.07       0  4932.3    0.05       0  4990.9    0.05       0
  5009.1    0.05       0  5120.4    0.07       0
Bank Sta=4990.9,5009.1
Exp/Cntr=0.3,0.1

Type RM Length L Ch R = 1,16432,412,412,412
BEGIN DESCRIPTION:
Mapping XS 894fb749
END DESCRIPTION:
XS GIS Cut Line= 3
      2618185.12     13397507.37      2617935.09     13397416.22
      2617612.19     13397457.88
#Sta/Elev= 30
  4721.2   58.95  4785.2   57.30  4828.7   55.12  4862.3   52.88  4902.3   47.51
  4943.3   45.03  4966.1   41.85  4973.9   39.62  4979.2   39.22  4984.7   35.18
  4990.9   34.65  4991.4   34.15  5009.1   34.65  5014.8   38.64  5021.2   37.02
  5037.8   37.52  5047.9   39.66  5058.0   43.98  5078.2   47.40  5094.2   48.51
  5099.2   47.80  5128.6   51.47  5148.7   51.11  5168.5   52.56  5173.6   52.09
  5188.8   53.00  5199.2   52.63  5229.4   54.63  5253.0   54.52  5312.9   57.17
#Mann=6,-1,0
  4721.2    0.05       0  4828.7    0.07       0  4990.9    0.05       0
  5009.1    0.07       0  5021.2    0.05       0  5188.8    0.07       0
Bank Sta=4990.9,5009.1
Exp/Cntr=0.3,0.1

Type RM Length L Ch R = 1,16020,157,157,157
BEGIN DESCRIPTION:
DRY KUY CREEK 33.0
END DESCRIPTION:
XS GIS Cut Line= 3
      2618025.03     13397074.98      2617825.00     13397175.00
      2617674.98     13397325.02
#Sta/Elev= 30
  4776.1   56.80  4784.5   57.16  4798.5   56.75  4820.9   55.90  4834.8   54.72
  4851.6   54.38  4865.6   52.95  4874.0   53.06  4879.6   51.72  4896.3   51.22
  4901.9   49.84  4910.3   49.92  4941.0   44.13  4946.6   40.22  4963.4   37.33
  4969.0   33.75  4977.4   34.32  4985.8   35.67  4990.9   33.75  4991.4   33.25
  5008.6   33.25  5009.1   33.75  5013.9   38.88  5028.0   41.07  5042.2   44.29
  5056.3   46.66  5070.5   48.43  5155.3   52.63  5169.4   53.69  5211.9   55.12
#Mann=3,-1,0
  4776.1    0.07       0  4990.9    0.05       0  5009.1    0.07       0
Bank Sta=4990.9,5009.1
Exp/Cntr=0.3,0.1

Type RM Length L Ch R = 1,15863,298,298,298
BEGIN DESCRIPTION:
Mapping XS 3d102124
END DESCRIPTION:
XS GIS Cut Line= 3
      2618036.62     13397002.16      2617729.36     13397054.24
      2617502.80     13397202.68
#Sta/Elev= 30
  4683.3   58.98  4745.8   57.37  4785.7   54.27  4846.0   50.89  4851.1   51.12
  4906.4   46.76  4928.4   43.32  4966.7   34.27  4971.8   34.92  4979.1   33.46
  4990.9   33.37  4991.4   32.87  5008.6   32.87  5009.1   33.37  5012.1   42.10
  5036.0   43.52  5042.0   42.28  5048.0   44.41  5057.1   46.27  5063.1   45.72
  5078.2   48.73  5093.3   49.72  5099.2   49.38  5120.3   50.89  5135.4   52.79
  5150.5   53.22  5186.7   56.11  5192.7   55.36  5207.8   55.24  5265.8   57.11
#Mann=3,-1,0
  4683.3    0.07       0  4990.9    0.05       0  5009.1    0.07       0
Bank Sta=4990.9,5009.1
Exp/Cntr=0.3,0.1

Type RM Length L Ch R = 1,15565,483,483,483
BEGIN DESCRIPTION:
DRY KUY CREEK 32.0
END DESCRIPTION:
XS GIS Cut Line= 3
      2617975.02     13396875.01      2617775.00     13396775.00
      2617575.03     13396775.00
#Sta/Elev= 30
  4776.8   54.36  4799.2   53.52  4829.9   50.89  4835.5   51.02  4843.9   50.23
  4874.6   48.88  4880.2   48.96  4919.4   45.76  4925.0   45.81  4941.7   42.68
  4947.3   43.44  4964.1   40.62  4969.7   41.21  4978.1   40.83  4986.5   41.58
  4990.9   32.98  4991.4   32.48  5008.6   32.48  5009.1   32.98  5010.4   36.60
  5020.4   32.98  5030.4   36.89  5040.4   38.52  5050.4   41.38  5060.4   43.51
  5080.4   45.25  5120.4   51.91  5150.4   54.41  5170.4   55.54  5200.4   55.80
#Mann=3,-1,0
  4776.8    0.07       0  4990.9    0.05       0  5009.1    0.07       0
Bank Sta=4990.9,5009.1
Exp/Cntr=0.3,0.1

Type RM Length L Ch R = 1,15082,452,452,452
BEGIN DESCRIPTION:
DRY KUY CREEK 31.0
END DESCRIPTION:
XS GIS Cut Line= 3
      2618124.96     13396424.99      2617925.00     13396375.00
      2617674.96     13396425.01
#Sta/Elev= 30
  4794.0   58.55  4824.9   57.90  4835.2   57.44  4845.5   56.67  4866.1   54.74
  4886.7   53.25  4899.6   52.02  4928.0   50.17  4935.7   48.59  4940.8   48.57
  4948.6   46.92  4958.9   45.16  4969.2   41.95  4976.9   38.07  4982.1   38.09
  4989.8   36.44  4990.8   32.42  4991.3   31.92  5008.8   31.92  5009.3   32.42
  5010.3   32.42  5020.5   35.10  5030.7   38.00  5051.1   41.23  5061.3   42.69
  5071.5   43.34  5102.1   44.84  5122.5   46.23  5252.5   53.72  5255.1   53.72
#Mann=3,-1,0
  4794.0    0.07       0  4990.8    0.05       0  5009.3    0.07       0
Bank Sta=4990.8,5009.3
Exp/Cntr=0.3,0.1