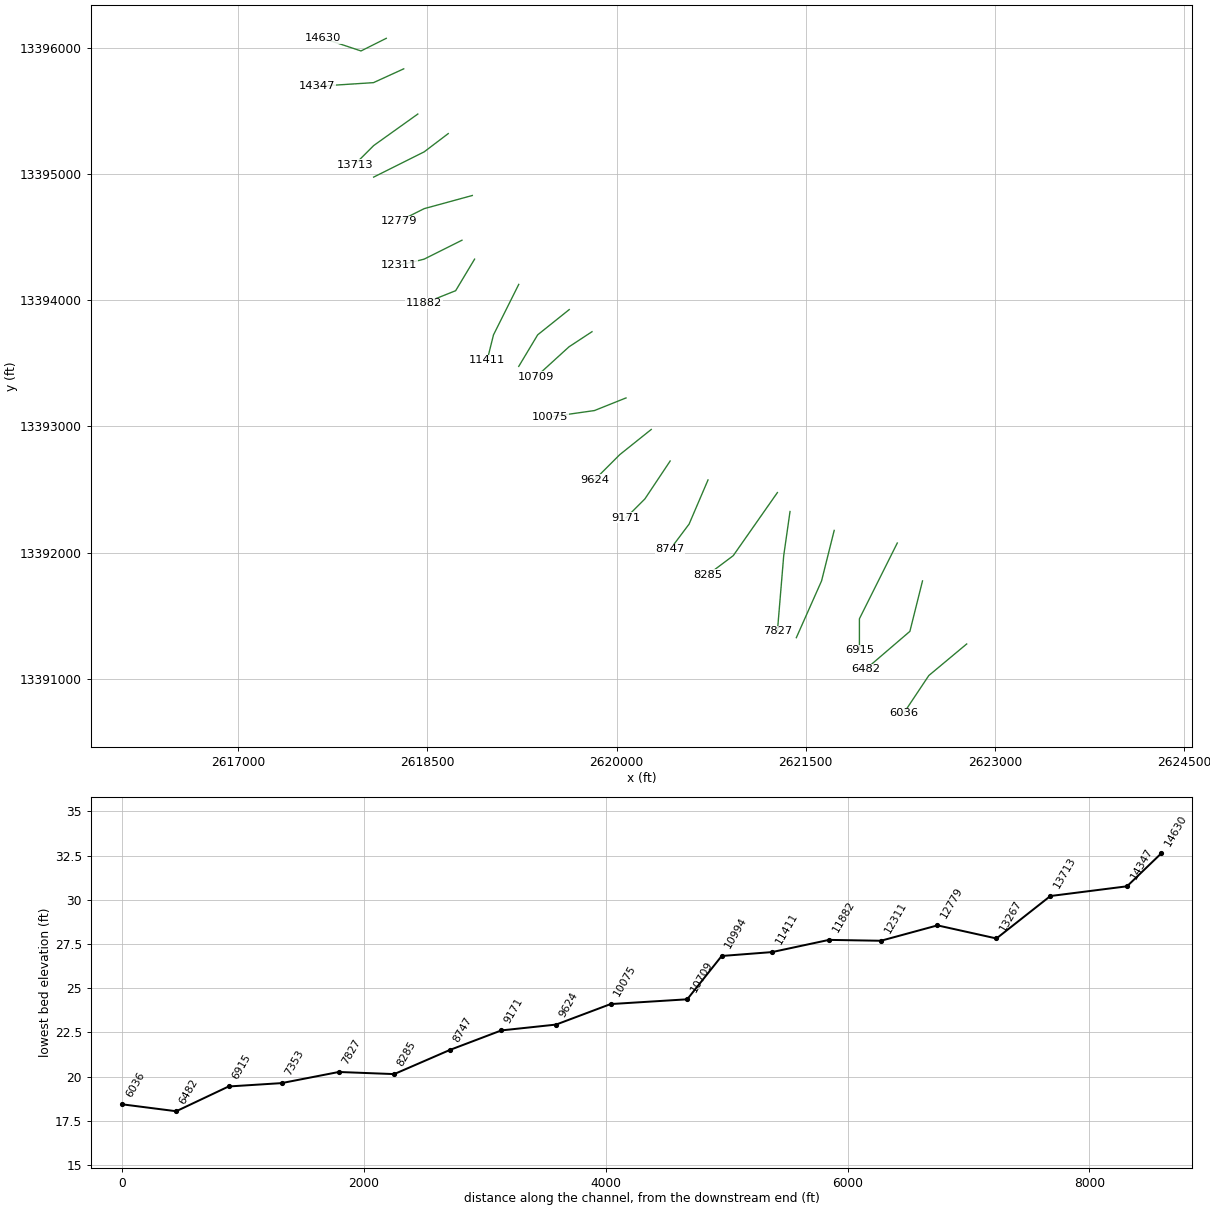
HEC-RAS study DRY KUY CREEK.prj: DRY KUY CREEK Detailed Study

--- DRY KUY CREEK.g01 (geometry) --- (continued)

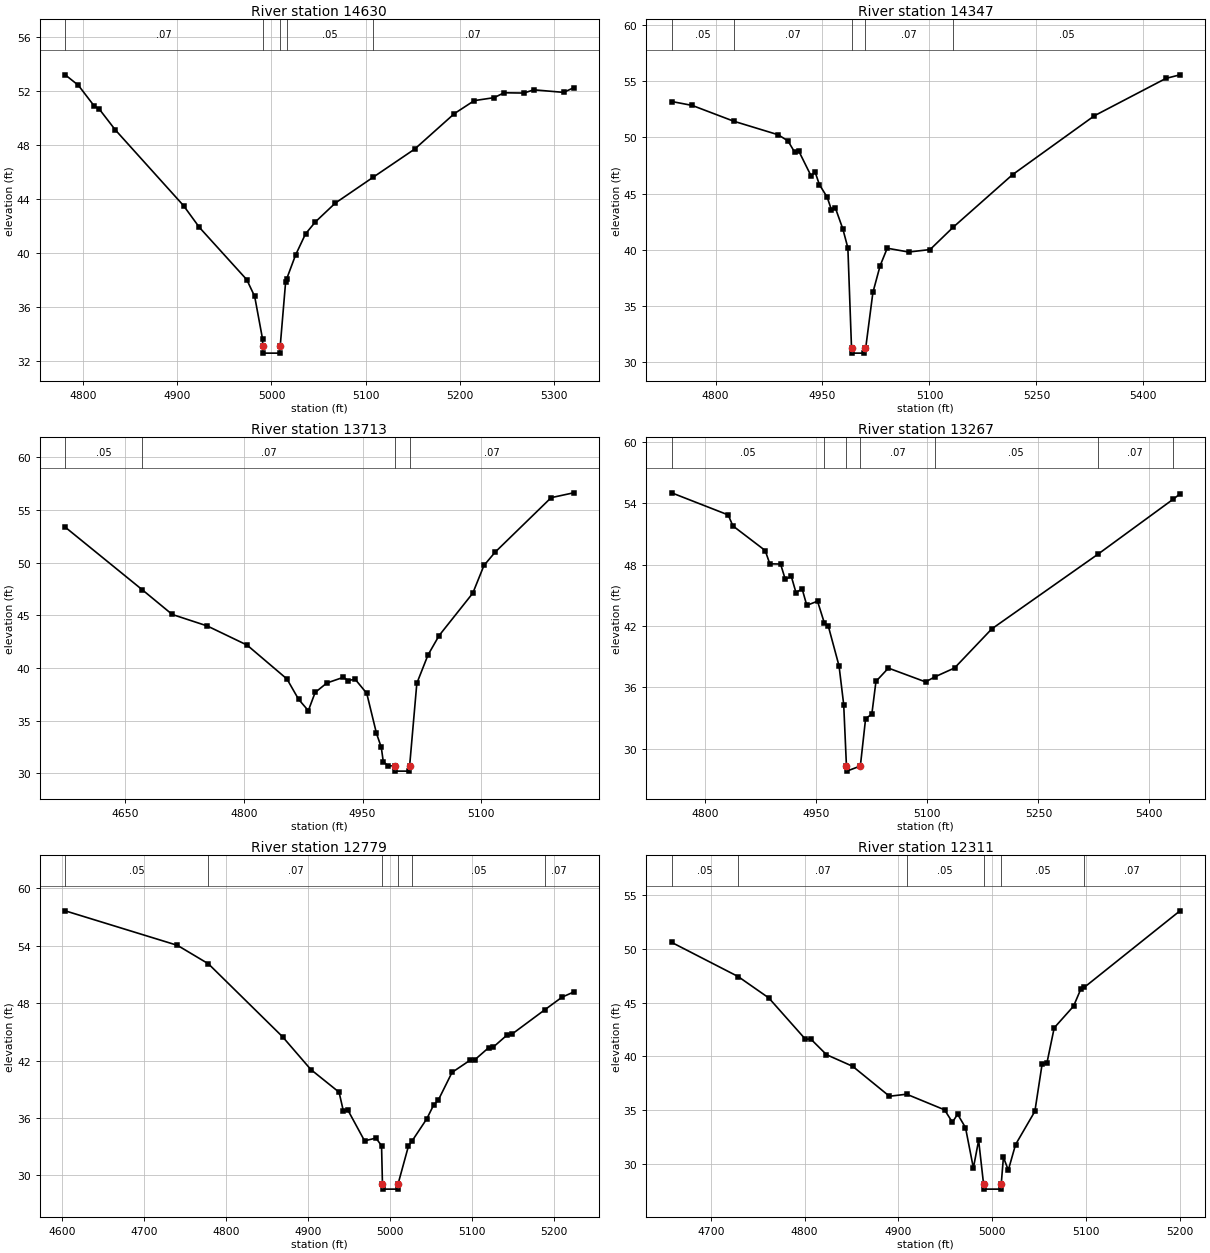
Type RM Length L Ch R = 1,14630,283,283,283
BEGIN DESCRIPTION:
DRY KUY CREEK 30.0
END DESCRIPTION:
XS GIS Cut Line= 3
      2618174.97     13396074.98      2617975.00     13395975.00
      2617675.00     13396075.00
#Sta/Elev= 30
  4781.0   53.23  4794.9   52.46  4811.7   50.93  4817.3   50.68  4834.1   49.16
  4906.7   43.54  4923.5   41.93  4973.8   38.06  4982.2   36.82  4990.6   33.65
  4990.7   33.12  4991.2   32.62  5008.8   32.62  5009.3   33.12  5015.1   37.92
  5016.3   38.14  5025.6   39.88  5036.2   41.45  5046.7   42.34  5067.8   43.73
  5107.9   45.64  5152.1   47.73  5194.3   50.36  5215.4   51.32  5236.5   51.54
  5247.0   51.90  5268.1   51.88  5278.6   52.12  5310.3   51.93  5320.8   52.27
#Mann=5,-1,0
  4781.0    0.07       0  4990.7    0.05       0  5009.3    0.07       0
  5016.3    0.05       0  5107.9    0.07       0
Bank Sta=4990.7,5009.3
Exp/Cntr=0.3,0.1

Type RM Length L Ch R = 1,14347,634,634,634
BEGIN DESCRIPTION:
Mapping XS e8f44d62
END DESCRIPTION:
XS GIS Cut Line= 3
      2618313.41     13395833.26      2618073.82     13395723.88
      2617625.23     13395694.86
#Sta/Elev= 30
  4738.5   53.21  4767.3   52.86  4825.6   51.45  4888.0   50.24  4901.6   49.69
  4911.0   48.69  4916.5   48.82  4934.1   46.56  4939.6   46.93  4945.6   45.80
  4956.6   44.67  4962.6   43.54  4968.1   43.71  4978.6   41.83  4985.6   40.15
  4990.7   31.26  4991.2   30.76  5008.9   30.76  5009.4   31.26  5010.7   31.26
  5020.7   36.17  5030.8   38.55  5040.8   40.12  5070.8   39.78  5100.9   40.00
  5132.9   41.97  5216.5   46.68  5331.4   51.94  5431.6   55.27  5451.4   55.59
#Mann=5,-1,0
  4738.5    0.05       0  4825.6    0.07       0  4990.7    0.05       0
  5009.4    0.07       0  5132.9    0.05       0
Bank Sta=4990.7,5009.4
Exp/Cntr=0.3,0.1

Type RM Length L Ch R = 1,13713,446,446,446
BEGIN DESCRIPTION:
DRY KUY CREEK 28.0
END DESCRIPTION:
XS GIS Cut Line= 3
      2618425.00     13395475.00      2618075.00     13395225.00
      2617924.97     13395074.97
#Sta/Elev= 30
  4574.2   53.38  4671.3   47.45  4709.4   45.09  4753.6   44.00  4804.0   42.18
  4854.4   38.96  4869.1   37.03  4881.4   35.95  4890.0   37.68  4904.8   38.58
  4925.7   39.12  4931.8   38.80  4940.4   38.95  4955.2   37.60  4967.5   33.80
  4973.6   32.46  4976.1   31.11  4982.2   30.71  4990.7   30.71  4991.2   30.21
  5008.9   30.21  5009.4   30.71  5018.5   38.55  5032.6   41.24  5046.7   43.09
  5089.2   47.11  5103.3   49.74  5117.5   51.01  5188.2   56.18  5216.5   56.64
#Mann=4,-1,0
  4574.2    0.05       0  4671.3    0.07       0  4990.7    0.05       0
  5009.4    0.07       0
Bank Sta=4990.7,5009.4
Exp/Cntr=0.3,0.1

Type RM Length L Ch R = 1,13267,488,488,488
BEGIN DESCRIPTION:
DRY KUY CREEK 27.0
END DESCRIPTION:
XS GIS Cut Line= 3
      2618666.04     13395319.89      2618475.00     13395175.00
      2618074.98     13394974.99
#Sta/Elev= 30
  4754.4   55.01  4830.8   52.85  4837.1   51.78  4880.8   49.37  4887.0   48.07
  4901.6   48.05  4907.9   46.56  4916.1   46.84  4922.4   45.26  4930.7   45.63
  4937.0   44.01  4951.5   44.42  4960.7   42.30  4966.1   41.98  4980.6   38.09
  4986.9   34.31  4990.6   28.31  4991.1   27.81  5009.4   28.31  5016.5   32.95
  5024.9   33.37  5030.5   36.58  5047.3   37.88  5097.6   36.53  5109.7   37.01
  5136.7   37.89  5187.0   41.71  5330.1   48.99  5431.7   54.36  5441.4   54.90
#Mann=7,-1,0
  4754.4    0.05       0  4960.7    0.07       0  4990.6    0.05       0
  5009.4    0.07       0  5109.7    0.05       0  5330.1    0.07       0
  5431.7    0.05       0
Bank Sta=4990.6,5009.4
Exp/Cntr=0.3,0.1

Type RM Length L Ch R = 1,12779,468,468,468
BEGIN DESCRIPTION:
DRY KUY CREEK 26.0
END DESCRIPTION:
XS GIS Cut Line= 3
      2618857.00     13394829.42      2618475.00     13394725.00
      2618275.02     13394625.01
#Sta/Elev= 30
  4603.9   57.66  4740.7   54.05  4778.4   52.12  4868.8   44.49  4903.3   41.06
  4937.7   38.69  4943.0   36.70  4948.1   36.87  4968.8   33.60  4982.7   33.89
  4989.5   33.09  4990.6   29.05  4991.1   28.55  5009.0   28.55  5009.5   29.05
  5022.3   33.06  5026.4   33.55  5044.6   35.90  5053.0   37.35  5058.6   37.85
  5075.4   40.76  5097.7   42.05  5103.3   42.09  5120.1   43.35  5125.7   43.41
  5142.5   44.67  5148.1   44.74  5188.8   47.33  5209.5   48.63  5223.5   49.16
#Mann=6,-1,0
  4603.9    0.05       0  4778.4    0.07       0  4990.6    0.05       0
  5009.5    0.07       0  5026.4    0.05       0  5188.8    0.07       0
Bank Sta=4990.6,5009.5
Exp/Cntr=0.3,0.1

Type RM Length L Ch R = 1,12311,429,429,429
BEGIN DESCRIPTION:
DRY KUY CREEK 25.0
END DESCRIPTION:
XS GIS Cut Line= 3
      2618774.97     13394474.98      2618475.00     13394325.00
      2618275.03     13394275.01
#Sta/Elev= 30
  4658.4   50.58  4729.2   47.41  4761.8   45.43  4800.9   41.59  4806.5   41.62
  4823.3   40.16  4851.2   39.08  4890.4   36.30  4908.7   36.49  4949.1   35.04
  4957.4   33.89  4963.0   34.63  4971.4   33.39  4979.8   29.64  4985.4   32.21
  4990.6   28.18  4991.1   27.68  5009.0   27.68  5009.5   28.18  5011.8   30.64
  5017.0   29.44  5024.7   31.81  5045.3   34.90  5053.0   39.28  5058.2   39.41
  5065.9   42.65  5086.5   44.66  5094.3   46.26  5098.1   46.42  5199.9   53.51
#Mann=6,-1,0
  4658.4    0.05       0  4729.2    0.07       0  4908.7    0.05       0
  4990.6    0.05       0  5009.5    0.05       0  5098.1    0.07       0
Bank Sta=4990.6,5009.5
Exp/Cntr=0.3,0.1

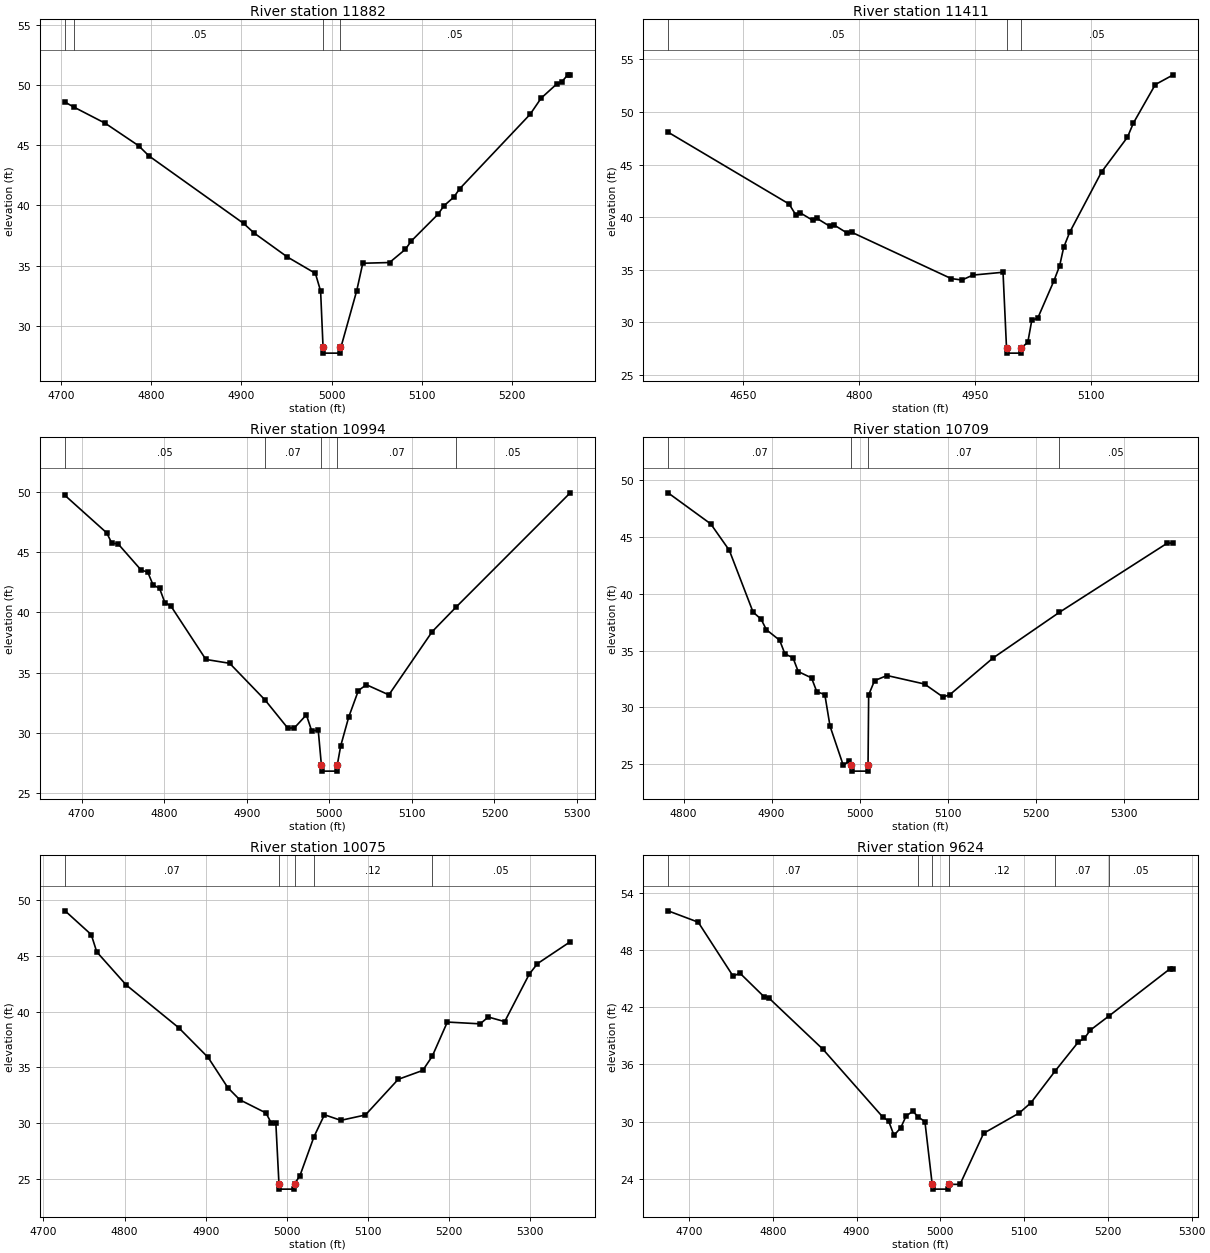
Type RM Length L Ch R = 1,11882,471,471,471
BEGIN DESCRIPTION:
DRY KUY CREEK 24.0
END DESCRIPTION:
XS GIS Cut Line= 3
      2618874.98     13394324.96      2618725.00     13394075.00
      2618474.96     13393974.99
#Sta/Elev= 30
  4704.2   48.59  4713.7   48.19  4748.9   46.83  4785.8   44.97  4797.5   44.11
  4902.4   38.51  4914.1   37.71  4951.0   35.72  4982.1   34.36  4987.9   32.89
  4990.6   28.23  4991.1   27.73  5009.0   27.73  5009.5   28.23  5010.5   28.23
  5028.0   32.92  5034.7   35.20  5064.4   35.26  5081.9   36.35  5088.6   37.05
  5118.2   39.27  5124.9   39.98  5135.7   40.69  5142.4   41.40  5220.5   47.58
  5232.7   48.92  5250.2   50.11  5255.5   50.27  5262.3   50.86  5265.0   50.86
#Mann=4,-1,0
  4704.2    0.07       0  4713.7    0.05       0  4990.6    0.05       0
  5009.5    0.05       0
Bank Sta=4990.6,5009.5
Exp/Cntr=0.3,0.1

Type RM Length L Ch R = 1,11411,417,417,417
BEGIN DESCRIPTION:
DRY KUY CREEK 23.0
END DESCRIPTION:
XS GIS Cut Line= 3
      2619224.98     13394124.96      2619025.00     13393725.00
      2618975.01     13393525.02
#Sta/Elev= 30
  4552.8   48.08  4709.3   41.24  4717.7   40.24  4723.3   40.42  4740.0   39.68
  4745.6   39.86  4762.4   39.10  4768.0   39.22  4784.7   38.46  4790.3   38.55
  4918.9   34.14  4932.9   34.00  4946.9   34.47  4986.0   34.74  4990.5   27.54
  4991.0   27.04  5009.0   27.04  5009.5   27.54  5018.0   28.06  5023.2   30.17
  5030.9   30.37  5051.5   33.87  5059.2   35.35  5064.4   37.10  5072.1   38.53
  5113.4   44.29  5146.9   47.60  5154.6   48.95  5182.9   52.61  5206.1   53.54
#Mann=3,-1,0
  4552.8    0.05       0  4990.5    0.05       0  5009.5    0.05       0
Bank Sta=4990.5,5009.5
Exp/Cntr=0.3,0.1

Type RM Length L Ch R = 1,10994,285,285,285
BEGIN DESCRIPTION:
DRY KUY CREEK 22.0
END DESCRIPTION:
XS GIS Cut Line= 3
      2619625.01     13393925.01      2619375.00     13393725.00
      2619225.01     13393475.01
#Sta/Elev= 30
  4680.0   49.70  4730.4   46.60  4736.8   45.72  4744.0   45.70  4772.1   43.51
  4780.1   43.34  4786.5   42.29  4794.5   41.98  4800.9   40.80  4808.1   40.53
  4850.5   36.09  4879.3   35.77  4922.1   32.73  4949.7   30.39  4957.7   30.41
  4972.2   31.49  4978.6   30.17  4986.6   30.20  4990.4   27.32  4990.9   26.82
  5009.1   26.82  5009.6   27.32  5013.8   28.92  5023.5   31.31  5035.2   33.51
  5044.9   33.99  5072.1   33.15  5124.6   38.40  5153.4   40.43  5291.7   49.92
#Mann=5,-1,0
  4680.0    0.05       0  4922.1    0.07       0  4990.4    0.05       0
  5009.6    0.07       0  5153.4    0.05       0
Bank Sta=4990.4,5009.6
Exp/Cntr=0.3,0.1

Type RM Length L Ch R = 1,10709,634,634,634
BEGIN DESCRIPTION:
Mapping XS b1a1b651
END DESCRIPTION:
XS GIS Cut Line= 3
      2619805.58     13393749.91      2619623.30     13393630.13
      2619360.27     13393390.54
#Sta/Elev= 30
  4782.4   48.91  4830.9   46.17  4852.0   43.84  4879.0   38.39  4888.1   37.77
  4894.1   36.84  4909.2   35.91  4915.2   34.70  4924.3   34.37  4930.3   33.15
  4945.4   32.59  4951.4   31.37  4960.5   31.12  4966.4   28.34  4981.5   24.87
  4987.5   25.25  4990.4   24.87  4990.9   24.37  5009.1   24.37  5009.6   24.87
  5010.3   31.09  5017.0   32.35  5031.2   32.80  5073.8   32.05  5094.7   30.91
  5102.2   31.09  5151.5   34.34  5226.9   38.37  5349.7   44.48  5356.3   44.48
#Mann=4,-1,0
  4782.4    0.07       0  4990.4    0.05       0  5009.6    0.07       0
  5226.9    0.05       0
Bank Sta=4990.4,5009.6
Exp/Cntr=0.3,0.1

Type RM Length L Ch R = 1,10075,451,451,451
BEGIN DESCRIPTION:
DRY KUY CREEK 20.0
END DESCRIPTION:
XS GIS Cut Line= 3
      2620075.02     13393225.01      2619825.00     13393125.00
      2619475.04     13393075.01
#Sta/Elev= 30
  4726.6   49.02  4758.9   46.89  4765.7   45.34  4802.0   42.38  4866.6   38.56
  4903.0   35.89  4927.2   33.19  4942.0   32.10  4974.3   30.92  4981.1   29.98
  4986.5   29.98  4990.3   24.60  4990.8   24.10  5009.2   24.10  5009.7   24.60
  5016.1   25.29  5033.6   28.81  5046.4   30.76  5066.6   30.26  5096.9   30.74
  5137.3   33.93  5167.6   34.73  5179.3   36.00  5197.9   39.06  5238.3   38.90
  5248.4   39.51  5268.6   39.10  5298.9   43.35  5309.0   44.29  5349.4   46.25
#Mann=5,-1,0
  4726.6    0.07       0  4990.3    0.05       0  5009.7    0.07       0
  5033.6    0.12       0  5179.3    0.05       0
Bank Sta=4990.3,5009.7
Exp/Cntr=0.3,0.1

Type RM Length L Ch R = 1,9624,453,453,453
BEGIN DESCRIPTION:
DRY KUY CREEK 19.0
END DESCRIPTION:
XS GIS Cut Line= 3
      2620275.01     13392975.01      2620025.00     13392775.00
      2619825.01     13392575.01
#Sta/Elev= 30
  4675.0   52.09  4711.0   50.90  4752.7   45.24  4760.7   45.57  4789.5   43.10
  4795.1   42.98  4859.9   37.59  4931.1   30.51  4938.3   30.07  4944.7   28.57
  4952.7   29.36  4959.2   30.60  4967.2   31.10  4973.9   30.47  4981.6   30.02
  4990.3   23.44  4990.8   22.94  5009.3   22.94  5009.8   23.44  5023.5   23.44
  5051.7   28.79  5094.2   30.91  5108.3   32.00  5137.3   35.34  5164.9   38.37
  5171.9   38.73  5179.0   39.59  5201.8   41.11  5274.5   46.04  5278.0   46.04
#Mann=6,-1,0
  4675.0    0.07       0  4973.9    0.12       0  4990.3    0.05       0
  5009.8    0.12       0  5137.3    0.07       0  5201.8    0.05       0
Bank Sta=4990.3,5009.8
Exp/Cntr=0.3,0.1

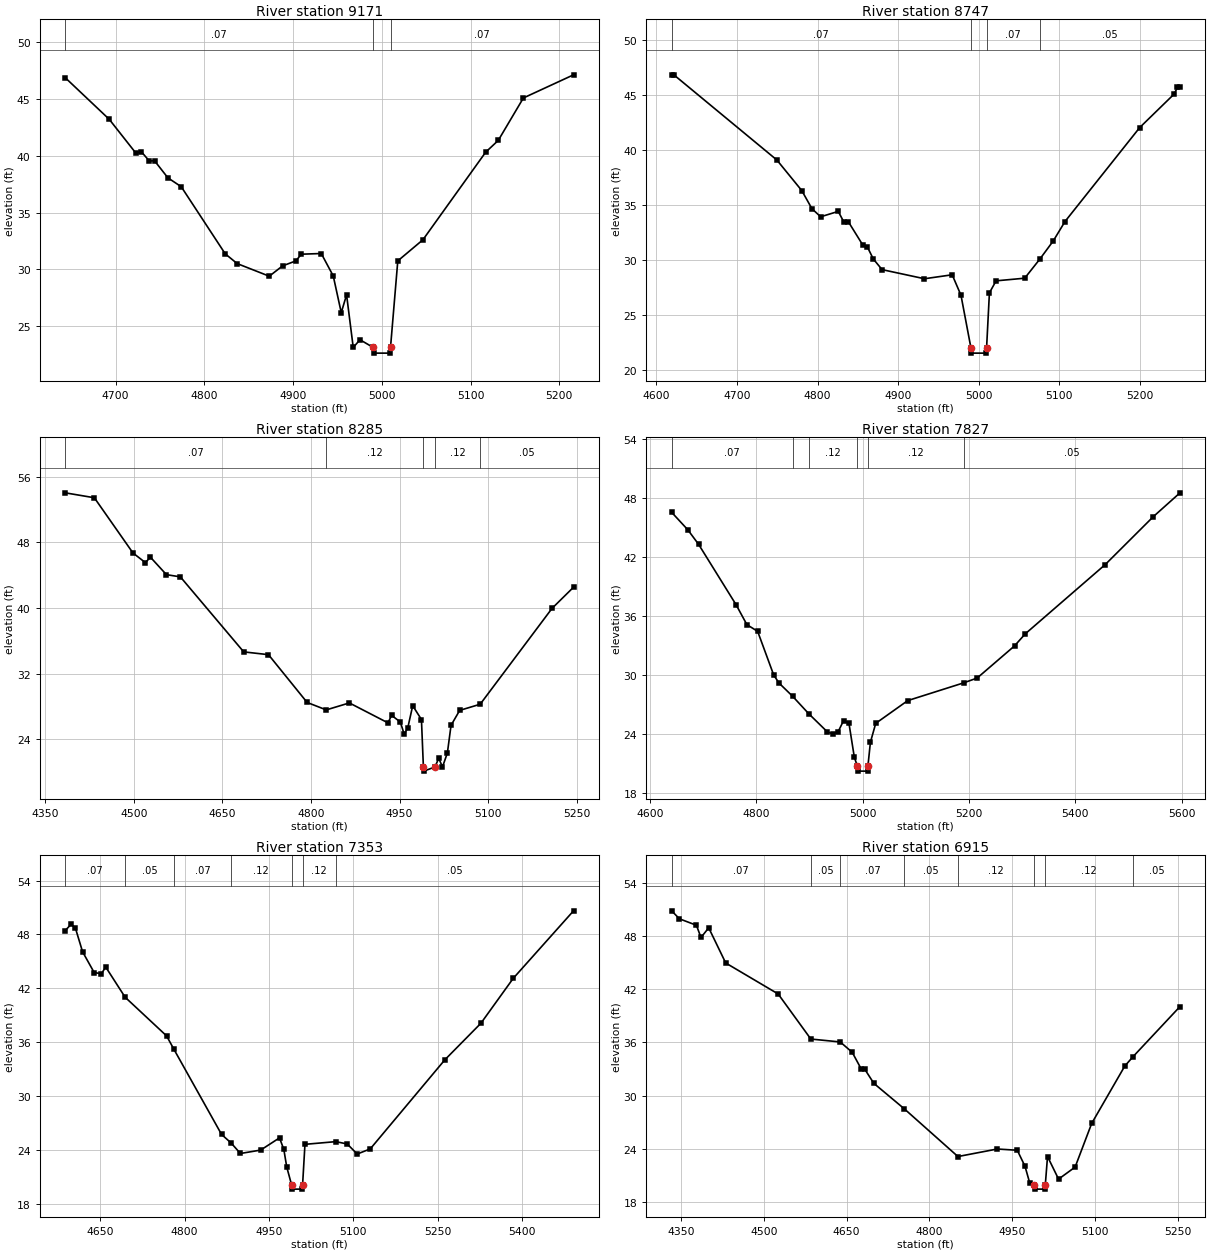
Type RM Length L Ch R = 1,9171,424,424,424
BEGIN DESCRIPTION:
DRY KUY CREEK 18.0
END DESCRIPTION:
XS GIS Cut Line= 3
      2620425.02     13392725.04      2620225.00     13392425.00
      2620075.02     13392275.02
#Sta/Elev= 30
  4643.3   46.89  4692.9   43.22  4723.0   40.23  4729.0   40.37  4738.0   39.55
  4744.0   39.56  4759.0   38.06  4774.0   37.28  4823.6   31.36  4837.1   30.50
  4873.2   29.39  4888.2   30.30  4903.2   30.74  4909.3   31.33  4931.8   31.39
  4945.3   29.41  4954.3   26.18  4960.3   27.75  4967.8   23.11  4975.4   23.79
  4990.3   23.11  4990.8   22.61  5009.3   22.61  5009.8   23.11  5018.0   30.74
  5046.3   32.60  5117.0   40.32  5131.2   41.36  5159.5   45.10  5216.0   47.14
#Mann=3,-1,0
  4643.3    0.07       0  4990.3    0.05       0  5009.8    0.07       0
Bank Sta=4990.3,5009.8
Exp/Cntr=0.3,0.1

Type RM Length L Ch R = 1,8747,462,462,462
BEGIN DESCRIPTION:
DRY KUY CREEK 17.0
END DESCRIPTION:
XS GIS Cut Line= 3
      2620724.99     13392574.98      2620575.00     13392225.00
      2620424.98     13392024.97
#Sta/Elev= 30
  4619.0   46.84  4621.7   46.84  4749.5   39.09  4780.4   36.31  4793.1   34.65
  4803.9   33.92  4825.7   34.41  4832.9   33.41  4838.4   33.45  4856.5   31.31
  4862.0   31.15  4869.2   30.08  4880.1   29.11  4932.7   28.28  4967.1   28.64
  4978.0   26.78  4990.3   22.01  4990.8   21.51  5009.3   21.51  5009.8   22.01
  5013.3   27.00  5021.6   28.09  5057.1   28.33  5076.1   30.09  5092.5   31.72
  5107.1   33.49  5199.8   42.04  5242.5   45.09  5246.6   45.69  5249.8   45.69
#Mann=4,-1,0
  4619.0    0.07       0  4990.3    0.05       0  5009.8    0.07       0
  5076.1    0.05       0
Bank Sta=4990.3,5009.8
Exp/Cntr=0.3,0.1

Type RM Length L Ch R = 1,8285,458,458,458
BEGIN DESCRIPTION:
DRY KUY CREEK 16.0
END DESCRIPTION:
XS GIS Cut Line= 3
      2621275.01     13392475.01      2620925.00     13391975.00
      2620725.03     13391825.02
#Sta/Elev= 30
  4384.1   54.05  4433.4   53.45  4498.8   46.72  4519.7   45.55  4528.4   46.20
  4555.4   44.08  4579.0   43.81  4686.2   34.67  4728.1   34.33  4793.5   28.51
  4825.9   27.60  4865.0   28.45  4930.4   26.02  4936.5   26.94  4951.3   26.12
  4957.8   24.64  4963.9   25.42  4972.2   28.11  4987.0   26.43  4990.3   20.64
  4990.8   20.14  5009.8   20.64  5016.3   21.71  5022.6   20.64  5030.9   22.36
  5037.1   25.72  5051.7   27.54  5086.4   28.29  5208.0   39.97  5244.4   42.55
#Mann=5,-1,0
  4384.1    0.07       0  4825.9    0.12       0  4990.3    0.05       0
  5009.8    0.12       0  5086.4    0.05       0
Bank Sta=4990.3,5009.8
Exp/Cntr=0.3,0.1

Type RM Length L Ch R = 1,7827,474,474,474
BEGIN DESCRIPTION:
DRY KUY CREEK 15.0
END DESCRIPTION:
XS GIS Cut Line= 3
      2621375.00     13392324.98      2621325.00     13391975.00
      2621275.00     13391375.01
#Sta/Elev= 30
  4641.0   46.53  4671.3   44.76  4691.5   43.29  4762.2   37.14  4782.4   35.13
  4802.6   34.45  4832.9   30.00  4843.0   29.19  4868.5   27.85  4898.8   26.08
  4933.9   24.23  4944.0   24.05  4954.1   24.28  4964.2   25.39  4974.3   25.11
  4984.4   21.66  4990.2   20.76  4990.7   20.26  5009.4   20.26  5009.9   20.76
  5014.6   23.19  5024.6   25.11  5084.8   27.42  5189.9   29.22  5215.3   29.71
  5285.5   32.97  5305.6   34.19  5456.1   41.23  5546.4   46.09  5596.6   48.51
#Mann=6,-1,0
  4641.0    0.07       0  4868.5   0.035       0  4898.8    0.12       0
  4990.2   0.035       0  5009.9    0.12       0  5189.9    0.05       0
Bank Sta=4990.2,5009.9
Exp/Cntr=0.3,0.1

Type RM Length L Ch R = 1,7353,438,438,438
BEGIN DESCRIPTION:
DRY KUY CREEK 14.0
END DESCRIPTION:
XS GIS Cut Line= 3
      2621725.00     13392174.98      2621625.00     13391775.00
      2621425.01     13391325.03
#Sta/Elev= 30
  4587.4   48.43  4597.7   49.12  4605.4   48.74  4618.3   46.07  4638.9   43.76
  4651.8   43.62  4659.5   44.37  4694.0   41.01  4767.8   36.70  4780.3   35.27
  4865.7   25.72  4882.7   24.77  4899.2   23.60  4935.3   23.98  4968.8   25.34
  4976.5   24.05  4981.7   22.09  4990.2   20.13  4990.7   19.63  5009.4   19.63
  5009.9   20.13  5014.1   24.62  5069.0   24.92  5089.3   24.66  5107.1   23.54
  5130.3   24.11  5263.0   34.03  5327.3   38.11  5384.8   43.11  5492.1   50.63
#Mann=7,-1,0
  4587.4    0.07       0  4694.0    0.05       0  4780.3    0.07       0
  4882.7    0.12       0  4990.2    0.05       0  5009.9    0.12       0
  5069.0    0.05       0
Bank Sta=4990.2,5009.9
Exp/Cntr=0.3,0.1

Type RM Length L Ch R = 1,6915,433,433,433
BEGIN DESCRIPTION:
DRY KUY CREEK 13.0
END DESCRIPTION:
XS GIS Cut Line= 3
      2622225.02     13392075.03      2621925.00     13391475.00
      2621925.00     13391224.95
#Sta/Elev= 30
  4333.0   50.87  4347.0   49.97  4377.8   49.24  4386.1   47.86  4400.1   48.95
  4430.9   44.98  4525.9   41.48  4585.1   36.39  4638.4   36.06  4660.1   34.89
  4676.8   32.96  4682.4   33.02  4699.2   31.39  4754.6   28.50  4851.6   23.12
  4922.8   23.97  4959.1   23.83  4973.1   22.02  4981.5   20.17  4990.2   19.94
  4990.7   19.44  5009.4   19.44  5009.9   19.94  5013.9   23.12  5033.9   20.57
  5063.9   21.93  5093.9   26.86  5153.9   33.34  5168.7   34.39  5253.9   40.06
#Mann=8,-1,0
  4333.0    0.07       0  4585.1    0.05       0  4638.4    0.07       0
  4754.6    0.05       0  4851.6    0.12       0  4990.2    0.05       0
  5009.9    0.12       0  5168.7    0.05       0
Bank Sta=4990.2,5009.9
Exp/Cntr=0.3,0.1

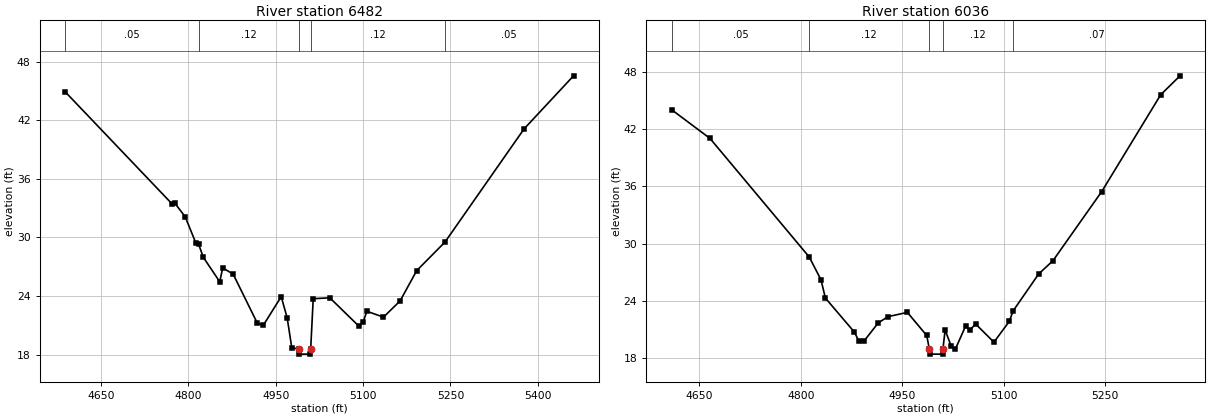
Type RM Length L Ch R = 1,6482,446,446,446
BEGIN DESCRIPTION:
DRY KUY CREEK 12.0
END DESCRIPTION:
XS GIS Cut Line= 3
      2622425.01     13391775.04      2622325.00     13391375.00
      2621975.02     13391075.02
#Sta/Elev= 30
  4588.2   44.92  4771.2   33.47  4776.4   33.52  4794.4   32.11  4812.4   29.46
  4817.3   29.33  4825.3   27.98  4853.7   25.45  4858.8   26.89  4876.9   26.22
  4918.1   21.23  4928.4   20.98  4959.3   23.93  4969.6   21.74  4977.4   18.71
  4990.2   18.54  4990.7   18.04  5009.4   18.04  5009.9   18.54  5014.3   23.72
  5042.8   23.81  5092.7   20.91  5099.9   21.33  5106.5   22.43  5135.0   21.83
  5163.5   23.49  5192.1   26.60  5240.6   29.52  5376.5   41.12  5461.5   46.56
#Mann=5,-1,0
  4588.2    0.05       0  4817.3    0.12       0  4990.2    0.05       0
  5009.9    0.12       0  5240.6    0.05       0
Bank Sta=4990.2,5009.9
Exp/Cntr=0.3,0.1

Type RM Length L Ch R = 1,6036,425,425,425
BEGIN DESCRIPTION:
DRY KUY CREEK 11.0
END DESCRIPTION:
XS GIS Cut Line= 3
      2622774.98     13391274.98      2622475.00     13391025.00
      2622275.02     13390725.03
#Sta/Elev= 30
  4609.3   44.01  4665.9   41.01  4812.5   28.60  4829.9   26.21  4836.4   24.30
  4879.4   20.72  4885.9   19.78  4893.7   19.82  4914.5   21.70  4928.8   22.35
  4957.5   22.80  4986.1   20.38  4990.1   18.93  4990.6   18.43  5009.5   18.43
  5010.0   18.93  5013.3   20.95  5022.3   19.26  5028.3   18.93  5043.4   21.35
  5049.4   20.93  5058.4   21.58  5085.4   19.68  5108.0   21.85  5113.8   22.96
  5151.5   26.82  5172.6   28.21  5244.7   35.45  5331.8   45.58  5360.3   47.56
#Mann=5,-1,0
  4609.3    0.05       0  4812.5    0.12       0  4990.1    0.05       0
  5010.0    0.12       0  5113.8    0.07       0
Bank Sta=4990.1,5010
Exp/Cntr=0.3,0.1