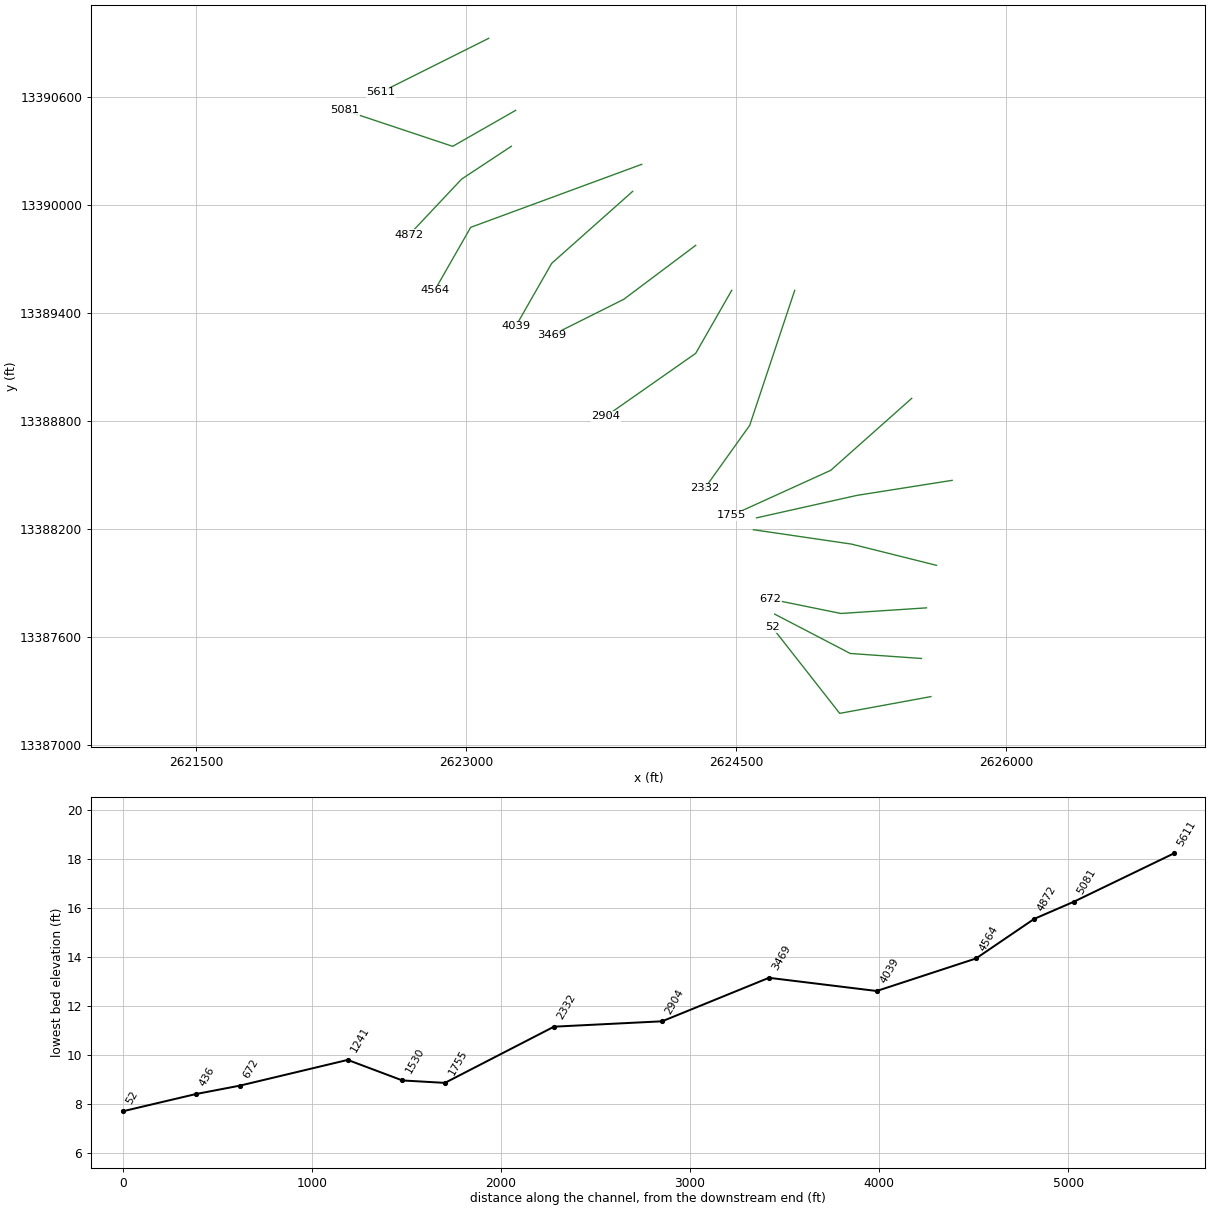
HEC-RAS study DRY KUY CREEK.prj: DRY KUY CREEK Detailed Study

--- DRY KUY CREEK.g01 (geometry) --- (continued)

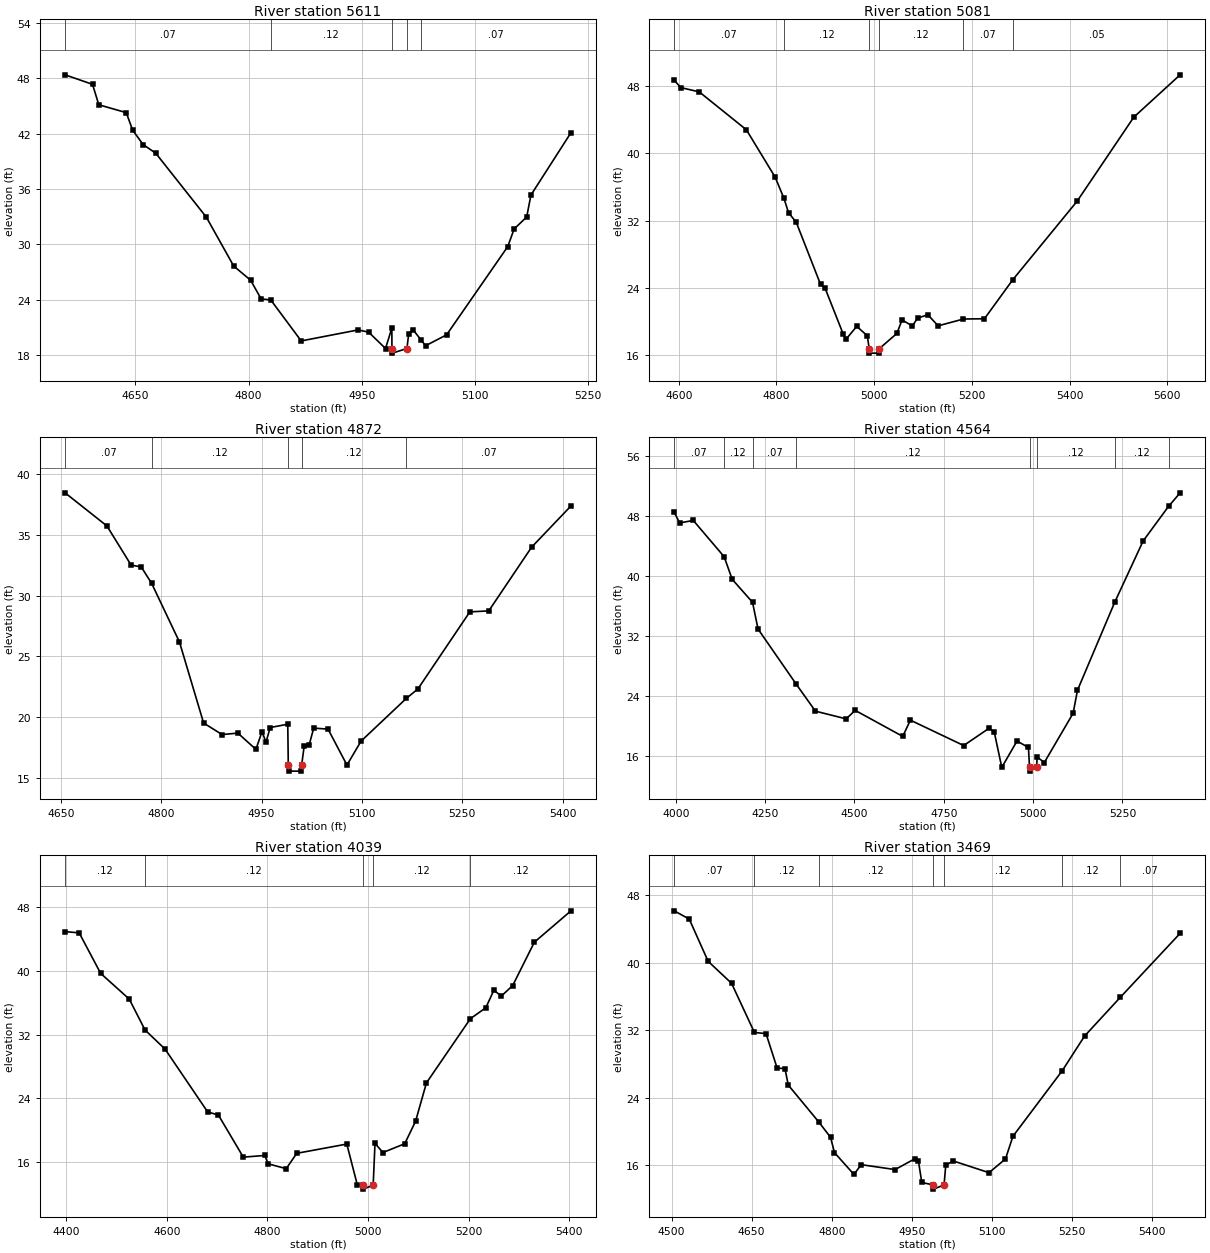
Type RM Length L Ch R = 1,5611,530,530,530
BEGIN DESCRIPTION:
DRY KUY CREEK 10.0
END DESCRIPTION:
XS GIS Cut Line= 3
      2623125.02     13390925.01      2622725.00     13390725.00
      2622525.04     13390625.02
#Sta/Elev= 30
  4556.7   48.35  4593.1   47.32  4601.4   45.11  4637.8   44.26  4646.2   42.38
  4660.1   40.81  4676.9   39.87  4744.0   32.95  4780.3   27.66  4802.7   26.13
  4816.7   24.10  4829.4   24.00  4869.8   19.56  4945.2   20.75  4959.2   20.51
  4981.6   18.74  4990.0   20.96  4990.1   18.74  4990.6   18.24  5010.0   18.74
  5012.3   20.33  5017.9   20.79  5028.4   19.70  5034.7   19.04  5062.6   20.22
  5143.7   29.77  5152.1   31.67  5168.8   32.97  5174.4   35.34  5227.5   42.09
#Mann=5,-1,0
  4556.7    0.07       0  4829.4    0.12       0  4990.1    0.05       0
  5010.0    0.12       0  5028.4    0.07       0
Bank Sta=4990.1,5010
Exp/Cntr=0.3,0.1

Type RM Length L Ch R = 1,5081,209,209,209
BEGIN DESCRIPTION:
DRY KUY CREEK 9.0
END DESCRIPTION:
XS GIS Cut Line= 3
      2623275.02     13390525.01      2622925.00     13390325.00
      2622324.99     13390525.00
#Sta/Elev= 30
  4590.8   48.65  4604.5   47.78  4641.9   47.28  4738.4   42.78  4797.4   37.15
  4815.5   34.62  4824.8   32.93  4840.6   31.79  4890.3   24.42  4899.6   23.97
  4936.3   18.58  4942.8   17.93  4964.4   19.44  4986.0   18.32  4990.0   16.76
  4990.5   16.26  5009.5   16.26  5010.0   16.76  5046.6   18.60  5057.2   20.20
  5078.3   19.48  5088.8   20.41  5109.9   20.82  5131.0   19.50  5182.9   20.31
  5225.8   20.34  5283.8   24.97  5415.6   34.30  5531.5   44.27  5626.4   49.30
#Mann=6,-1,0
  4590.8    0.07       0  4815.5    0.12       0  4990.0    0.05       0
  5010.0    0.12       0  5182.9    0.07       0  5283.8    0.05       0
Bank Sta=4990,5010
Exp/Cntr=0.3,0.1

Type RM Length L Ch R = 1,4872,308,308,308
BEGIN DESCRIPTION:
Mapping XS 7e76ce53
END DESCRIPTION:
XS GIS Cut Line= 3
      2623250.87     13390325.42      2622974.86     13390143.15
      2622683.21     13389833.27
#Sta/Elev= 30
  4656.3   38.47  4718.9   35.74  4755.0   32.52  4770.1   32.37  4785.7   31.02
  4827.3   26.19  4863.4   19.52  4891.0   18.57  4914.6   18.69  4941.6   17.35
  4950.7   18.81  4956.7   17.94  4962.9   19.15  4989.2   19.42  4990.0   16.06
  4990.5   15.56  5009.5   15.56  5010.0   16.06  5013.8   17.65  5021.1   17.70
  5028.0   19.10  5049.4   19.02  5077.7   16.06  5098.8   18.03  5166.7   21.56
  5183.7   22.32  5261.4   28.67  5289.7   28.75  5353.7   33.99  5412.6   37.39
#Mann=5,-1,0
  4656.3    0.07       0  4785.7    0.12       0  4990.0    0.05       0
  5010.0    0.12       0  5166.7    0.07       0
Bank Sta=4990,5010
Exp/Cntr=0.3,0.1

Type RM Length L Ch R = 1,4564,525,525,525
BEGIN DESCRIPTION:
DRY KUY CREEK 8.0
END DESCRIPTION:
XS GIS Cut Line= 3
      2623975.00     13390225.00      2623025.00     13389875.00
      2622825.02     13389525.03
#Sta/Elev= 30
  3995.9   48.51  4011.1   47.10  4049.2   47.43  4135.6   42.58  4158.0   39.57
  4214.9   36.50  4230.4   32.92  4337.6   25.53  4391.0   21.95  4477.0   20.92
  4502.1   22.06  4635.3   18.58  4656.6   20.75  4805.8   17.36  4876.6   19.66
  4891.1   19.21  4912.4   14.44  4955.0   17.96  4987.0   17.10  4990.0   14.44
  4990.5   13.94  5010.0   14.44  5011.2   15.83  5031.4   15.09  5112.0   21.67
  5124.2   24.75  5228.4   36.50  5307.8   44.68  5379.0   49.31  5411.4   51.12
#Mann=8,-1,0
  3995.9    0.07       0  4135.6    0.12       0  4214.9    0.07       0
  4337.6    0.12       0  4990.0    0.05       0  5010.0    0.12       0
  5228.4    0.12       0  5379.0    0.07       0
Bank Sta=4990,5010
Exp/Cntr=0.3,0.1

Type RM Length L Ch R = 1,4039,570,570,570
BEGIN DESCRIPTION:
DRY KUY CREEK 7.0
END DESCRIPTION:
XS GIS Cut Line= 3
      2623925.00     13390075.00      2623475.00     13389675.00
      2623274.99     13389324.99
#Sta/Elev= 30
  4397.9   44.97  4425.9   44.81  4468.6   39.72  4525.4   36.49  4556.7   32.61
  4596.5   30.21  4681.0   22.33  4702.7   21.90  4752.0   16.63  4794.7   16.84
  4801.4   15.79  4837.3   15.18  4858.2   17.11  4957.7   18.27  4978.7   13.11
  4989.9   13.11  4990.4   12.61  5010.1   13.11  5013.7   18.36  5029.5   17.21
  5072.7   18.31  5094.3   21.13  5115.9   25.96  5203.3   34.03  5233.9   35.40
  5249.8   37.59  5264.9   36.88  5287.2   38.18  5330.4   43.64  5403.1   47.58
#Mann=5,-1,0
  4397.9    0.12       0  4556.7    0.12       0  4989.9    0.05       0
  5010.1    0.12       0  5203.3    0.12       0
Bank Sta=4989.9,5010.1
Exp/Cntr=0.3,0.1

Type RM Length L Ch R = 1,3469,565,565,565
BEGIN DESCRIPTION:
DRY KUY CREEK 6.0
END DESCRIPTION:
XS GIS Cut Line= 3
      2624275.00     13389775.00      2623875.00     13389475.00
      2623475.01     13389275.01
#Sta/Elev= 30
  4505.0   46.15  4533.1   45.17  4568.5   40.16  4612.3   37.56  4655.1   31.73
  4676.9   31.59  4697.7   27.49  4712.3   27.45  4718.5   25.49  4775.4   21.13
  4797.7   19.29  4805.0   17.48  4841.5   14.89  4855.0   16.05  4918.5   15.47
  4955.0   16.73  4962.3   16.44  4968.5   13.94  4989.9   13.65  4990.4   13.15
  5010.2   13.65  5013.4   16.00  5027.4   16.49  5094.4   15.10  5125.2   16.73
  5139.2   19.42  5231.6   27.20  5273.3   31.30  5340.0   35.88  5452.2   43.48
#Mann=7,-1,0
  4505.0    0.07       0  4655.1    0.12       0  4775.4    0.12       0
  4989.9    0.05       0  5010.2    0.12       0  5231.6    0.12       0
  5340.0    0.07       0
Bank Sta=4989.9,5010.2
Exp/Cntr=0.3,0.1

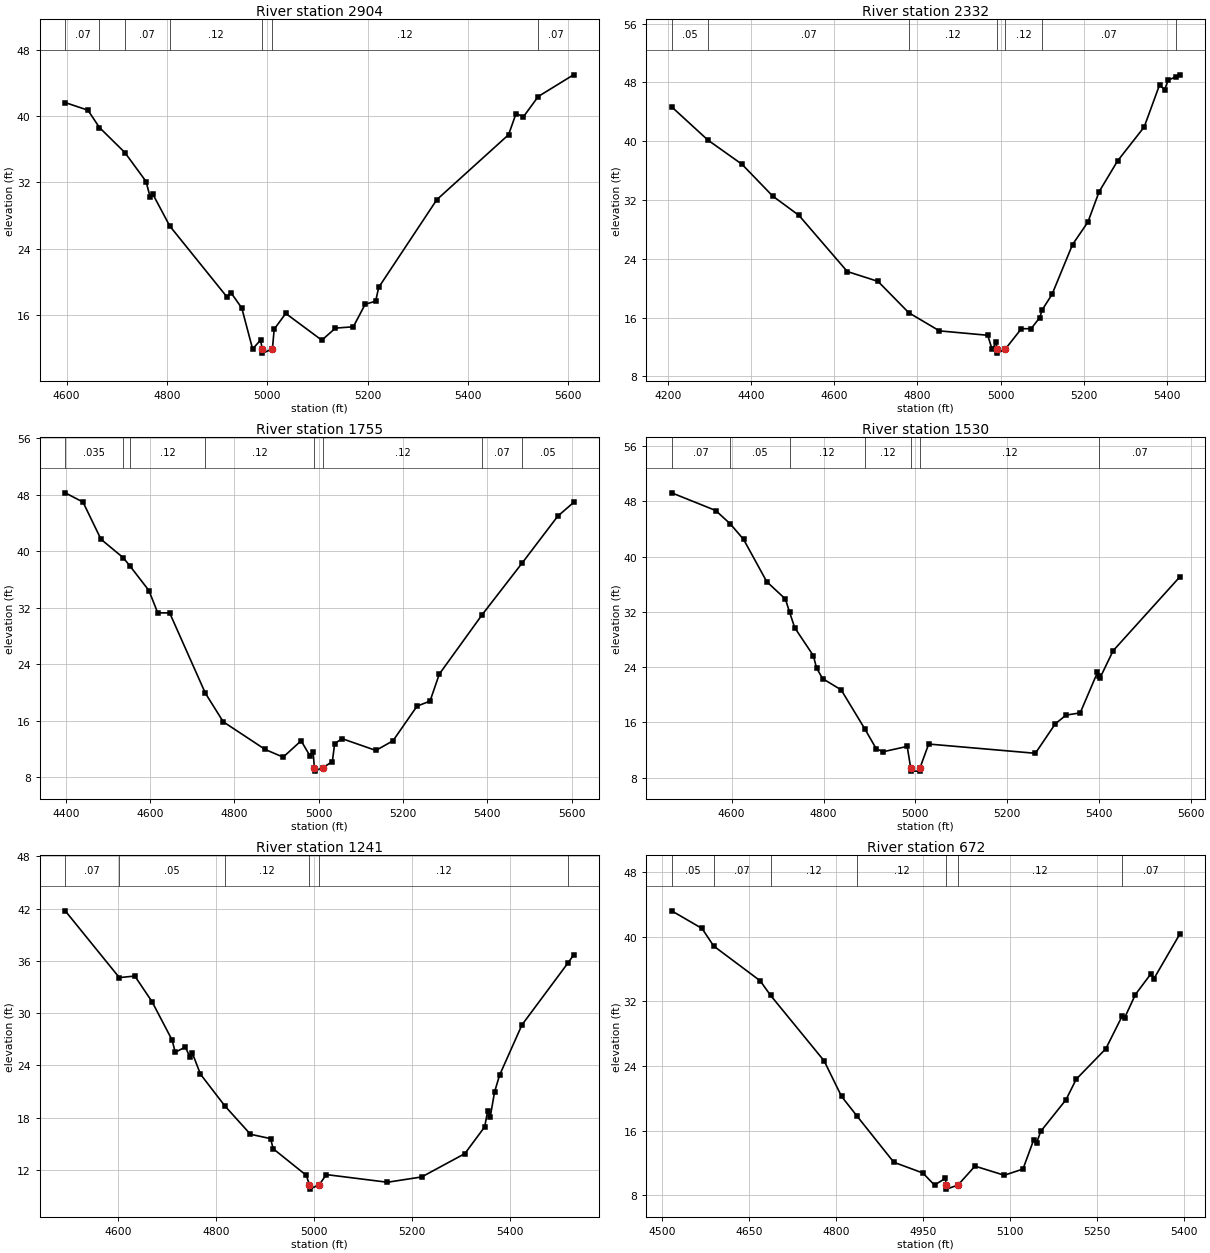
Type RM Length L Ch R = 1,2904,572,572,572
BEGIN DESCRIPTION:
DRY KUY CREEK 5.0
END DESCRIPTION:
XS GIS Cut Line= 3
      2624474.99     13389524.98      2624275.00     13389175.00
      2623775.01     13388825.01
#Sta/Elev= 30
  4597.1   41.62  4642.4   40.70  4665.3   38.61  4716.0   35.59  4758.3   32.09
  4766.2   30.26  4772.0   30.54  4805.4   26.73  4919.6   18.15  4927.5   18.67
  4949.1   16.82  4970.7   11.87  4986.5   12.94  4989.9   11.87  4990.4   11.37
  5010.2   11.87  5013.7   14.26  5036.8   16.16  5108.7   12.93  5135.8   14.39
  5171.5   14.55  5195.1   17.27  5216.0   17.64  5222.1   19.31  5338.0   29.90
  5481.0   37.74  5495.9   40.29  5510.7   39.91  5540.1   42.35  5610.5   44.97
#Mann=7,-1,0
  4597.1    0.07       0  4665.3    0.12       0  4716.0    0.07       0
  4805.4    0.12       0  4989.9    0.05       0  5010.2    0.12       0
  5540.1    0.07       0
Bank Sta=4989.9,5010.2
Exp/Cntr=0.3,0.1

Type RM Length L Ch R = 1,2332,577,577,577
BEGIN DESCRIPTION:
DRY KUY CREEK 4.0
END DESCRIPTION:
XS GIS Cut Line= 3
      2624825.00     13389525.01      2624575.00     13388775.00
      2624325.00     13388425.00
#Sta/Elev= 30
  4209.7   44.68  4296.6   40.16  4378.4   36.87  4452.2   32.54  4515.4   29.90
  4631.4   22.26  4705.1   20.92  4779.1   16.65  4852.7   14.18  4968.7   13.58
  4979.2   11.65  4989.7   12.67  4989.9   11.65  4990.4   11.15  5010.2   11.65
  5049.4   14.47  5072.8   14.48  5093.7   15.99  5099.1   17.01  5123.2   19.16
  5172.3   25.93  5209.2   28.99  5236.2   33.13  5280.5   37.32  5344.4   41.94
  5381.2   47.65  5393.5   47.03  5402.1   48.32  5421.0   48.78  5430.4   49.04
#Mann=7,-1,0
  4209.7    0.05       0  4296.6    0.07       0  4779.1    0.12       0
  4989.9    0.05       0  5010.2    0.12       0  5099.1    0.07       0
  5421.0    0.05       0
Bank Sta=4989.9,5010.2
Exp/Cntr=0.3,0.1

Type RM Length L Ch R = 1,1755,225,225,225
BEGIN DESCRIPTION:
DRY KUY CREEK 3.0
END DESCRIPTION:
XS GIS Cut Line= 3
      2625474.99     13388924.99      2625025.00     13388525.00
      2624475.02     13388275.01
#Sta/Elev= 30
  4398.6   48.28  4440.8   46.97  4483.5   41.70  4536.2   39.09  4552.3   37.91
  4597.2   34.44  4618.1   31.28  4646.5   31.26  4731.1   19.90  4773.6   15.84
  4873.1   11.92  4915.8   10.83  4958.4   13.15  4979.3   11.02  4986.9   11.53
  4989.8    9.35  4990.3    8.85  5010.3    9.35  5032.5   10.20  5038.0   12.75
  5055.6   13.45  5135.8   11.78  5176.4   13.15  5233.5   18.06  5264.3   18.77
  5286.3   22.60  5387.7   30.99  5483.7   38.40  5567.5   44.98  5604.8   46.91
#Mann=8,-1,0
  4398.6   0.035       0  4536.2    0.05       0  4552.3    0.12       0
  4731.1    0.12       0  4989.8    0.05       0  5010.3    0.12       0
  5387.7    0.07       0  5483.7    0.05       0
Bank Sta=4989.8,5010.3
Exp/Cntr=0.3,0.1

Type RM Length L Ch R = 1,1530,289,289,289
BEGIN DESCRIPTION:
Mapping XS 38e7b7f9
END DESCRIPTION:
XS GIS Cut Line= 3
      2625699.70     13388469.54      2625171.91     13388386.21
      2624612.84     13388261.20
#Sta/Elev= 30
  4469.3   49.23  4565.2   46.67  4597.0   44.73  4625.9   42.49  4676.5   36.36
  4717.0   33.86  4726.0   31.98  4737.3   29.71  4777.8   25.67  4784.9   23.88
  4798.0   22.34  4838.5   20.71  4890.7   14.98  4914.8   12.19  4929.6   11.75
  4982.3   12.53  4989.8    9.45  4990.3    8.95  5009.8    8.95  5010.3    9.45
  5029.1   12.87  5261.5   11.53  5304.9   15.80  5328.4   17.06  5359.1   17.38
  5396.8   23.25  5400.3   22.68  5402.0   22.40  5430.8   26.37  5576.5   37.09
#Mann=7,-1,0
  4469.3    0.07       0  4597.0    0.05       0  4726.0    0.12       0
  4890.7    0.12       0  4989.8    0.05       0  5010.3    0.12       0
  5400.3    0.07       0
Bank Sta=4989.8,5010.3
Exp/Cntr=0.3,0.1

Type RM Length L Ch R = 1,1241,569,569,569
BEGIN DESCRIPTION:
Mapping XS 6207eab7
END DESCRIPTION:
XS GIS Cut Line= 3
      2625612.87     13387997.32      2625140.66     13388115.38
      2624595.53     13388195.24
#Sta/Elev= 30
  4491.6   41.75  4602.1   34.08  4633.7   34.26  4668.7   31.33  4709.9   26.90
  4716.2   25.50  4736.8   26.11  4746.0   24.98  4751.1   25.42  4767.7   22.99
  4817.3   19.36  4869.7   16.09  4910.9   15.59  4916.1   14.43  4984.1   11.36
  4989.8   10.29  4990.3    9.79  5010.3   10.29  5024.5   11.46  5149.5   10.58
  5219.4   11.19  5307.5   13.87  5347.9   16.94  5354.1   18.80  5359.1   18.03
  5368.1   20.95  5378.2   22.86  5424.0   28.65  5518.2   35.78  5529.3   36.67
#Mann=6,-1,0
  4491.6    0.07       0  4602.1    0.05       0  4817.3    0.12       0
  4989.8    0.05       0  5010.3    0.12       0  5518.2    0.07       0
Bank Sta=4989.8,5010.3
Exp/Cntr=0.3,0.1

Type RM Length L Ch R = 1,672,236,236,236
BEGIN DESCRIPTION:
Mapping XS 241f4b17
END DESCRIPTION:
XS GIS Cut Line= 3
      2625557.31     13387761.21      2625081.63     13387729.96
      2624689.67     13387809.74
#Sta/Elev= 30
  4516.6   43.23  4569.0   41.04  4589.0   38.87  4669.2   34.56  4687.2   32.75
  4779.5   24.64  4809.5   20.24  4836.4   17.78  4899.7   12.07  4949.8   10.74
  4969.9    9.24  4988.8   10.09  4989.8    9.24  4990.3    8.74  5010.3    9.24
  5039.7   11.59  5090.3   10.46  5122.5   11.23  5140.9   14.83  5146.0   14.48
  5153.1   15.90  5196.6   19.81  5214.4   22.37  5265.4   26.14  5293.5   30.18
  5297.7   29.95  5316.4   32.86  5343.2   35.43  5348.3   34.82  5393.3   40.39
#Mann=7,-1,0
  4516.6    0.05       0  4589.0    0.07       0  4687.2    0.12       0
  4836.4    0.12       0  4989.8    0.05       0  5010.3    0.12       0
  5293.5    0.07       0
Bank Sta=4989.8,5010.3
Exp/Cntr=0.3,0.1

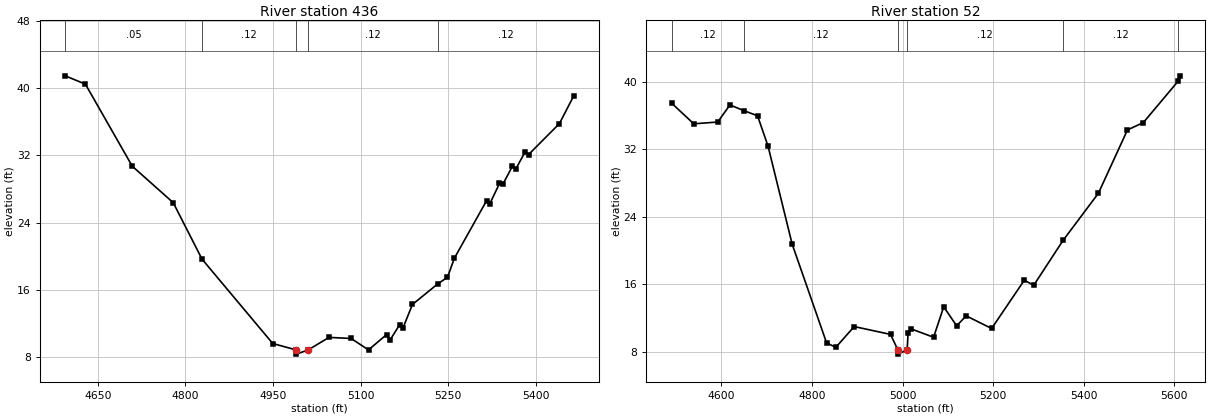
Type RM Length L Ch R = 1,436,384,384,384
BEGIN DESCRIPTION:
Mapping XS 71e89fa6
END DESCRIPTION:
XS GIS Cut Line= 3
      2625529.53     13387479.96      2625133.72     13387507.74
      2624713.54     13387726.50
#Sta/Elev= 30
  4594.2   41.47  4628.8   40.48  4709.0   30.73  4779.2   26.39  4828.5   19.68
  4949.6    9.65  4989.7    8.89  4990.2    8.39  5010.3    8.89  5045.9   10.38
  5083.9   10.25  5113.6    8.89  5144.6   10.72  5150.2   10.03  5166.7   11.86
  5172.3   11.44  5188.8   14.29  5232.3   16.75  5248.8   17.52  5260.7   19.80
  5315.8   26.63  5321.4   26.27  5337.9   28.68  5343.5   28.56  5360.0   30.72
  5365.6   30.36  5382.1   32.47  5387.7   32.11  5440.5   35.79  5464.7   39.04
#Mann=5,-1,0
  4594.2    0.05       0  4828.5    0.12       0  4989.7    0.05       0
  5010.3    0.12       0  5232.3    0.12       0
Bank Sta=4989.7,5010.3
Exp/Cntr=0.3,0.1

Type RM Length L Ch R = 1,52,0,0,0
BEGIN DESCRIPTION:
DRY KUY CREEK 1.0
END DESCRIPTION:
XS GIS Cut Line= 3
      2625581.60     13387268.15      2625075.00     13387175.00
      2624699.86     13387653.35
#Sta/Elev= 30
  4490.0   37.45  4538.8   35.01  4591.8   35.22  4618.7   37.25  4649.9   36.56
  4679.7   35.96  4703.0   32.34  4756.1   20.75  4832.2    9.03  4852.6    8.49
  4893.2   10.96  4973.5   10.03  4989.7    8.19  4990.2    7.69  5010.3    8.19
  5012.3   10.25  5018.7   10.69  5068.6    9.69  5091.0   13.30  5119.5   11.05
  5140.7   12.23  5196.8   10.73  5269.0   16.45  5289.9   15.86  5354.8   21.19
  5432.7   26.77  5496.9   34.28  5532.1   35.16  5609.4   40.10  5613.0   40.70
#Mann=6,-1,0
  4490.0    0.12       0  4649.9    0.12       0  4989.7    0.05       0
  5010.3    0.12       0  5354.8    0.12       0  5609.4    0.07       0
Bank Sta=4989.7,5010.3
Exp/Cntr=0.3,0.1

Chan Stop Cuts=-1