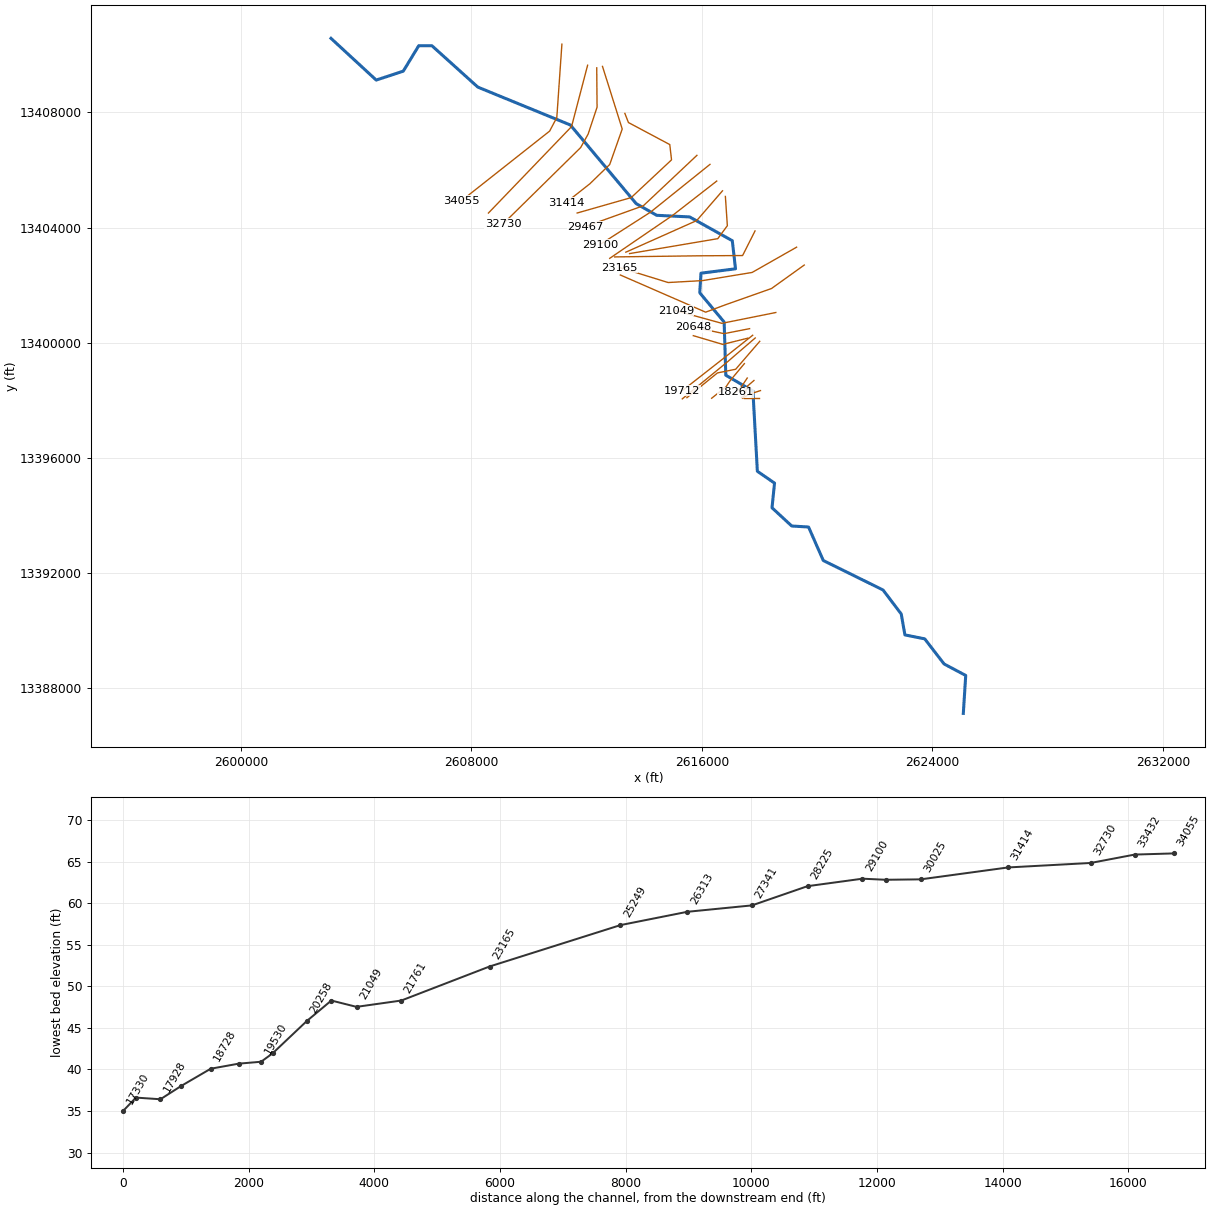
--- DRY KUY CREEK.prj (project) ---

Proj Title=DRY KUY CREEK Base Level Engineering
Current Plan=p01
Default Exp/Contr=0.3,0.1
English Units
Geom File=g01
Flow File=f01
Plan File=p01
Y Axis Title=Elevation
X Axis Title(PF)=Main Channel Distance
X Axis Title(XS)=Station
BEGIN DESCRIPTION:
DRY KUY CREEK
END DESCRIPTION:
DSS Export Rating Curves= 0
DSS Export Rating Curve Sorted= 0
DSS Export Volume Flow Curves= 0
DXF OffsetX= 0
DXF OffsetY= 0
DXF ScaleX= 1
DXF ScaleY= 10

--- DRY KUY CREEK.p01 (plan) ---

Plan Title=Multiple Run
Program Version=4.10
Short Identifier=Multiple
Geom File=g01
Flow File=f01
Subcritical Flow
K Sum by GR= 0
Std Step Tol= 0.01
Critical Tol= 0.01
Num of Std Step Trials= 20
Max Error Tol= 0.3
Flow Tol Ratio= 0.001
Split Flow NTrial= 30
Split Flow Tol= 0.02
Split Flow Ratio= 0.02
Log Output Level= 0
Friction Slope Method= 1
Unsteady Friction Slope Method= 2
Unsteady Bridges Friction Slope Method= 1
Parabolic Critical Depth
Global Vel Dist= 1 , 1 , 1
Global Log Level= 0
CheckData=True
Encroach Param=-1 ,0,0, 0
BEGIN DESCRIPTION:
Multiple Run
END DESCRIPTION:
Computation Interval=1HOUR
Output Interval=1HOUR
Run HTab= 0
Run UNet= 0
Run PostProcess= 0
Run WQNet= 0
UNET Theta= 1
UNET Theta Warmup= 1
UNET ZTol= 0.02
UNET ZSATol= 0.05
UNET MxIter= 20
UNET MaxInSteps= 0
UNET DtIC= 0
UNET DtMin= 0
UNET MaxCRTS= 20
UNET WFStab= 2
UNET SFStab= 1
UNET WFX= 1
UNET SFX= 1
UNET DSS MLevel= 4
UNET DZMax Abort= 100
UNET Convert EG Bridges= 0
UNET Use Existing IB Tables=-1
UNET Froude Reduction=False
UNET Froude Limit= 1
UNET Froude Power= 10
UNET Time Slicing=0,0, 5
UNET Junction Losses=0
Instantaneous Interval=1HOUR
Write IC File= 0
Write IC File at Sim End=0
Echo Input=False
Echo Parameters=False
Echo Output=False
Write Detailed= 0
WQ AD Non Conservative
WQ ULTIMATE=-1
WQ Max Comp Step=1HOUR
WQ Output Interval=15MIN
WQ Output Selected Increments= 0
WQ Output face flow=0
WQ Output face velocity=0
WQ Output face area=0
WQ Output face dispersion=0
WQ Output cell volume=0
WQ Output cell surface area=0
WQ Output cell continuity=0
WQ Output cumulative cell continuity=0
WQ Output face conc=0
WQ Output face dconc_dx=0
WQ Output face courant=0
WQ Output face peclet=0
WQ Output face adv mass=0
WQ Output face disp mass=0
WQ Output cell mass=0
WQ Output cell source sink temp=0
WQ Output cell source sink nsm=0
WQ Output MaxMinRange=-1
WQ Daily Max Min Mean=-1
WQ Daily Range=0
WQ Daily Time=0
WQ Create Restart=0
WQ Fixed Restart=0
WQ System Summary=0
WQ Use Fixed Temperature=0
Sorting and Armoring Iterations= 10
XS Update Threshold= 0.02
Hydraulics Update Threshold= 0.02
Energy Slope Method= 1
Volume Change Method= 0
XS Weighting Method= 0
Number of US Weighted Cross Sections= 1
Number of DS Weighted Cross Sections= 1
Upstream XS Weight=0.25
Main XS Weight=0.5
Downstream XS Weight=0.25
Number of DS XS's Weighted with US Boundary= 1
Upstream Boundary Weight= 1
Weight of XSs Associated with US Boundary= 0
Number of US XS's Weighted with DS Boundary= 1
Downstream Boundary Weight= 0.5
Weight of XSs Associated with DS Boundary= 0.5
Sediment Output Level= 4
Mass or Volume Output= 0
Output Increment Type= 1
Profile and TS Output Increment= 10
XS Output Flag= 0
XS Output Increment= 10
Disregard all LS=0
Disregard all Conn=0
Disregard all Breaches=0
Disregard all Pumps=0

--- DRY KUY CREEK.f01 (steady flow) ---

Flow Title=Multiple
Number of Profiles=7
Profile Names=10-year,25-year,50-year,1pct_min,100-year,1pct_plu,500-year
River Rch & RM= DRY KUY CREEK,Reach-1,34055
     749    1146    1482     924    1844    3678    2822
River Rch & RM= DRY KUY CREEK,Reach-1,30025
     866    1337    1740    1091    2177    4344    3373
River Rch & RM= DRY KUY CREEK,Reach-1,26313
     978    1522    1992    1256    2506    5001    3926
River Rch & RM= DRY KUY CREEK,Reach-1,23165
    1217    1923    2543    1620    3232    6450    5167
River Rch & RM= DRY KUY CREEK,Reach-1,19712
    2055    3334    4492    2911    5808   11589    9610
River Rch & RM= DRY KUY CREEK,Reach-1,13267
    2259    3684    4980    3238    6460   12890   10759
River Rch & RM= DRY KUY CREEK,Reach-1,6036
    2429    3979    5394    3517    7018   14003   11755
Boundary for River Rch & Prof#=DRY KUY CREEK,Reach-1,1
Up Type=0
Dn Type=3
Dn Slope=0.005
Boundary for River Rch & Prof#=DRY KUY CREEK,Reach-1,2
Up Type=0
Dn Type=3
Dn Slope=0.005
Boundary for River Rch & Prof#=DRY KUY CREEK,Reach-1,3
Up Type=0
Dn Type=3
Dn Slope=0.005
Boundary for River Rch & Prof#=DRY KUY CREEK,Reach-1,4
Up Type=0
Dn Type=3
Dn Slope=0.005
Boundary for River Rch & Prof#=DRY KUY CREEK,Reach-1,5
Up Type=0
Dn Type=3
Dn Slope=0.005
Boundary for River Rch & Prof#=DRY KUY CREEK,Reach-1,6
Up Type=0
Dn Type=3
Dn Slope=0.005
Boundary for River Rch & Prof#=DRY KUY CREEK,Reach-1,7
Up Type=0
Dn Type=3
Dn Slope=0.005

--- DRY KUY CREEK.g01 (geometry) ---

Geom Title=Existing Conditions
Program Version=4.10

River Reach=DRY KUY CREEK   ,Reach-1
Reach XY= 30
        2603125.       13410575.      2604695.03     13409125.06
      2605634.68      13409435.2      2606172.57     13410319.48
      2606627.42     13410319.46      2608222.55     13408880.47
      2611434.79     13407564.48      2613718.81     13404832.82
      2614430.93     13404427.24      2615573.44     13404371.24
      2617055.21     13403545.09      2617167.33     13402568.48
      2615968.57     13402416.98      2615926.05     13401735.44
      2616772.93     13400719.14      2616830.37      13398872.3
      2617771.56     13398323.81       2617925.7     13395535.76
      2618521.96     13395123.58      2618433.99     13394267.99
      2619118.27     13393634.11       2619702.7     13393598.73
      2620214.51     13392435.52      2622288.25     13391411.39
      2622919.65      13390577.7       2623047.3     13389851.27
      2623735.08     13389713.91      2624407.87      13388841.3
      2625158.59      13388441.8        2625075.       13387125.

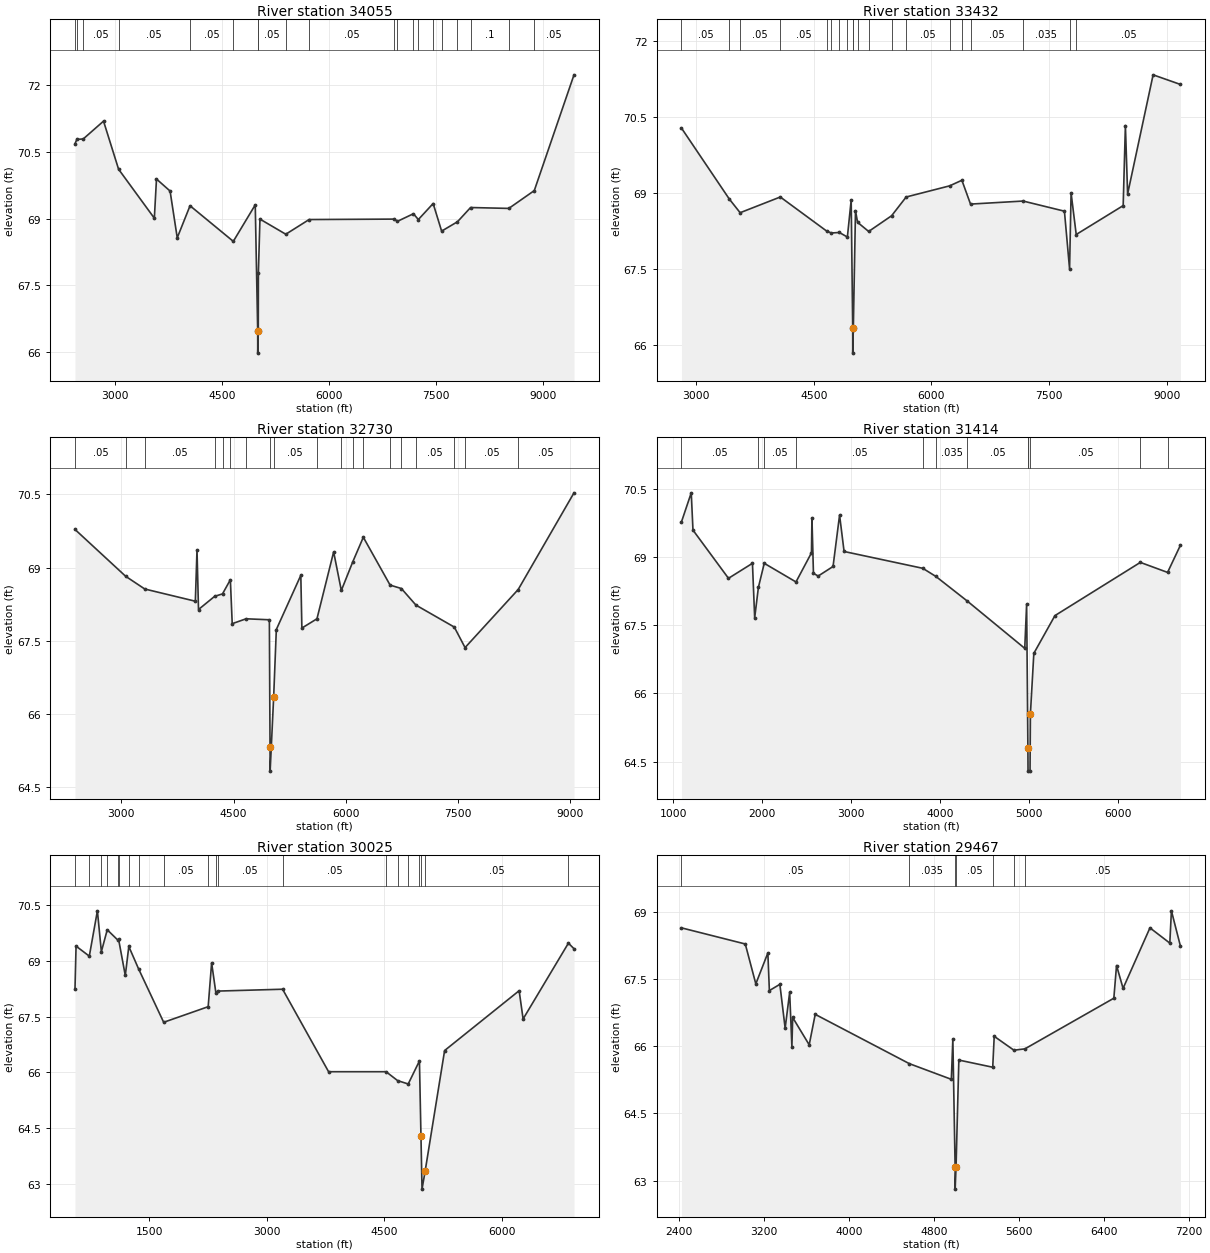
Type RM Length L Ch R = 1 ,34055   ,623,623,623
BEGIN DESCRIPTION:
Mapping XS e25f44ca
END DESCRIPTION:
XS GIS Cut Line= 4
       2611140.7     13410373.71       2610964.3      13407823.3
       2610714.8     13407352.44      2607655.22     13404934.43
#Sta/Elev= 30
  2443.5   70.68  2469.1   70.78    2559   70.79  2843.2   71.19  3054.1   70.11
  3554.9   69.01  3584.9   69.89  3775.4   69.62  3875.6   68.57  4054.8   69.29
  4660.8   68.49  4968.2   69.31  5002.5   66.48    5003   65.98  5010.4   66.48
  5012.1   67.79  5034.1   68.99    5396   68.65  5722.7   68.98  6914.2   68.99
  6959.9   68.94  7183.5   69.11  7252.5   68.98  7459.8   69.34  7578.6   68.72
  7800.5   68.93  7984.1   69.25  8519.6   69.23  8876.4   69.63  9432.6   72.23
#Mann= 20 ,-1 , 0
  2443.5    .035       0  2469.1     .05       0    2559     .05       0
  3054.1     .05       0  4054.8     .05       0  4660.8     .05       0
  5002.5     .04       0  5010.4     .05       0    5396    .035       0
  5722.7     .05       0  6914.2    .035       0  6959.9     .05       0
  7183.5    .035       0  7252.5     .05       0  7459.8     .05       0
  7578.6      .1       0  7800.5     .05       0  7984.1      .1       0
  8519.6     .05       0  8876.4     .05       0
Bank Sta=5002.5,5010.4
XS Rating Curve= 0 ,0
Exp/Cntr=0.3,0.1

Type RM Length L Ch R = 1 ,33432   ,702,702,702
BEGIN DESCRIPTION:
Mapping XS 43d3dddd
END DESCRIPTION:
XS GIS Cut Line= 3
      2612033.17     13409640.39      2611475.71     13407508.33
       2608590.6     13404505.87
#Sta/Elev= 30
  2809.6   70.28    3420   68.88  3558.3   68.61  4070.9   68.92  4660.7   68.25
  4721.4   68.21  4824.2   68.22  4926.9   68.13  4975.4   68.86  4994.8   66.34
  4995.3   65.84  5002.9   66.34  5030.4   68.65  5057.2   68.42  5198.6   68.24
  5491.2   68.55  5677.1   68.92  6232.2   69.14  6388.1   69.25  6498.2   68.78
  7169.8   68.84  7696.6   68.64  7762.3    67.5  7781.5      69    7847   68.18
  8446.3   68.75  8474.6   70.33  8502.9   68.98  8828.3   71.33  9177.3   71.14
#Mann= 20 ,-1 , 0
  2809.6     .05       0    3420     .05       0  3558.3     .05       0
  4070.9     .05       0  4660.7     .05       0  4721.4     .05       0
  4824.2     .05       0  4926.9     .05       0  4994.8     .04       0
  5002.9     .05       0  5057.2     .05       0  5198.6     .05       0
  5491.2    .035       0  5677.1     .05       0  6232.2     .05       0
  6388.1     .05       0  6498.2     .05       0  7169.8    .035       0
  7762.3    .035       0    7847     .05       0
Bank Sta=4994.8,5002.9
XS Rating Curve= 0 ,0
Exp/Cntr=0.3,0.1

Type RM Length L Ch R = 1 ,32730   ,1316,1316,1316
BEGIN DESCRIPTION:
Mapping XS 44671194
END DESCRIPTION:
XS GIS Cut Line= 5
        2612350.     13409549.98       2612361.5     13408184.38
      2612051.61     13407248.27      2611791.19     13406779.52
      2609100.03     13404130.84
#Sta/Elev= 30
  2383.1   69.78  3060.3   68.82    3315   68.56  3990.4   68.31  4012.4   69.36
  4032.5   68.14  4248.2   68.41  4353.1   68.46    4458   68.75  4482.8   67.85
  4667.8   67.95  4978.8   67.93  4987.7   65.33  4989.2   64.83    5036   66.34
  5071.8   67.73  5398.8   68.84    5413   67.76  5614.4   67.95  5837.3   69.32
  5939.8   68.53  6093.5   69.12  6233.5   69.62  6591.2   68.64  6741.7   68.57
  6936.7   68.23  7448.7   67.78  7592.1   67.36  8301.8   68.55    9047   70.53
#Mann= 19 ,-1 , 0
  2383.1     .05       0  3060.3     .05       0    3315     .05       0
  4248.2    .035       0  4353.1     .05       0    4458     .05       0
  4667.8     .05       0  4987.7     .04       0    5036     .05       0
  5614.4     .05       0  5939.8     .05       0  6093.5     .05       0
  6233.5     .05       0  6591.2     .05       0  6741.7     .05       0
  6936.7     .05       0  7448.7     .12       0  7592.1     .05       0
  8301.8     .05       0
Bank Sta=4987.7,5036
XS Rating Curve= 0 ,0
Exp/Cntr=0.3,0.1

Type RM Length L Ch R = 1 ,31414   ,1389,1389,1389
BEGIN DESCRIPTION:
Mapping XS c5c41804
END DESCRIPTION:
XS GIS Cut Line= 5
      2612550.01     13409599.96       2613234.9     13407424.73
      2612799.99     13406191.17      2612112.71     13405523.53
       2611279.1     13404866.45
#Sta/Elev= 30
  1093.9   69.77  1203.9   70.41  1223.4   69.59  1622.3   68.53  1891.8   68.86
  1916.8   67.66  1958.5   68.33  2024.4   68.86    2381   68.45    2555   69.09
  2560.3   69.86  2577.3   68.64  2630.3   68.58  2797.5   68.79  2870.9   69.92
  2921.6   69.12  3806.3   68.75  3954.1   68.57    4306   68.03    4952   66.99
  4973.1   67.96  4987.4   64.79  4988.9   64.29  5011.4   64.29  5015.6   65.55
  5054.1   66.88  5291.3   67.71  6251.1   68.88  6557.2   68.66    6702   69.26
#Mann= 12 ,-1 , 0
  1093.9     .05       0  1958.5     .05       0  2024.4     .05       0
    2381     .05       0  3806.3     .05       0  3954.1    .035       0
    4306     .05       0  4987.4     .04       0  4988.9     .04       0
  5015.6     .05       0  6251.1     .05       0  6557.2     .05       0
Bank Sta=4987.4,5015.6
XS Rating Curve= 0 ,0
Exp/Cntr=0.3,0.1

Type RM Length L Ch R = 1 ,30025   ,558,558,558
BEGIN DESCRIPTION:
Mapping XS ea8d28cf
END DESCRIPTION:
XS GIS Cut Line= 6
      2613326.89     13407967.45        2613450.       13407650.
      2614885.79     13406884.37      2614946.43     13406353.39
      2613547.01     13405042.79      2611670.19     13404506.56
#Sta/Elev= 30
   550.1   68.25   563.8    69.4   732.9   69.13   836.1   70.35   886.9   69.25
     962   69.84  1098.1   69.56  1106.2   69.59  1192.3   68.61  1237.3   69.39
  1361.5   68.79  1682.4   67.35  2250.6   67.77  2294.6   68.95  2349.1   68.14
    2371   68.19  3200.8   68.24  3787.9   66.02  4521.8   66.02  4669.6   65.78
  4804.7   65.69    4948   66.31  4967.4   64.29    4981   62.86    5022   63.36
  5269.4   66.59    6221    68.2  6271.6   67.44  6850.1   69.48  6921.4   69.33
#Mann= 20 ,-1 , 0
   550.1     .05       0   732.9     .05       0   886.9     .05       0
     962     .05       0  1098.1     .05       0  1106.2     .05       0
  1237.3     .05       0  1361.5     .05       0  1682.4     .05       0
  2250.6     .05       0  2349.1     .05       0    2371     .05       0
  3200.8     .05       0  4521.8     .05       0  4669.6     .05       0
  4804.7     .05       0    4948     .05       0  4967.4     .04       0
    5022     .05       0  6850.1     .05       0
Bank Sta=4967.4,5022
XS Rating Curve= 0 ,0
Exp/Cntr=0.3,0.1

Type RM Length L Ch R = 1 ,29467   ,367,367,367
BEGIN DESCRIPTION:
Mapping XS 1ad3fc03
END DESCRIPTION:
XS GIS Cut Line= 3
      2615827.82     13406510.78      2613969.61     13404760.15
      2611954.92     13404036.43
#Sta/Elev= 30
  2423.6   68.64  3023.9   68.28    3123   67.39  3236.3   68.08  3250.5   67.24
  3349.2   67.38  3398.9    66.4  3441.4    67.2  3462.4   65.99  3469.7   66.64
  3625.1   66.03  3681.7   66.71  4566.9   65.61  4962.2   65.26  4976.3   66.16
  4997.6   63.31  4998.1   62.81  5006.4   63.31  5032.7   65.69  5351.4   65.53
  5365.4   66.22  5550.7   65.91  5654.1   65.94  6490.6   67.07    6516    67.8
  6577.5   67.29  6830.3   68.64  7017.1    68.3  7032.2   69.02  7117.3   68.23
#Mann= 7 ,-1 , 0
  2423.6     .05       0  4566.9    .035       0  4997.6     .04       0
  5006.4     .05       0  5351.4     .05       0  5550.7     .05       0
  5654.1     .05       0
Bank Sta=4997.6,5006.4
XS Rating Curve= 0 ,0
Exp/Cntr=0.3,0.1

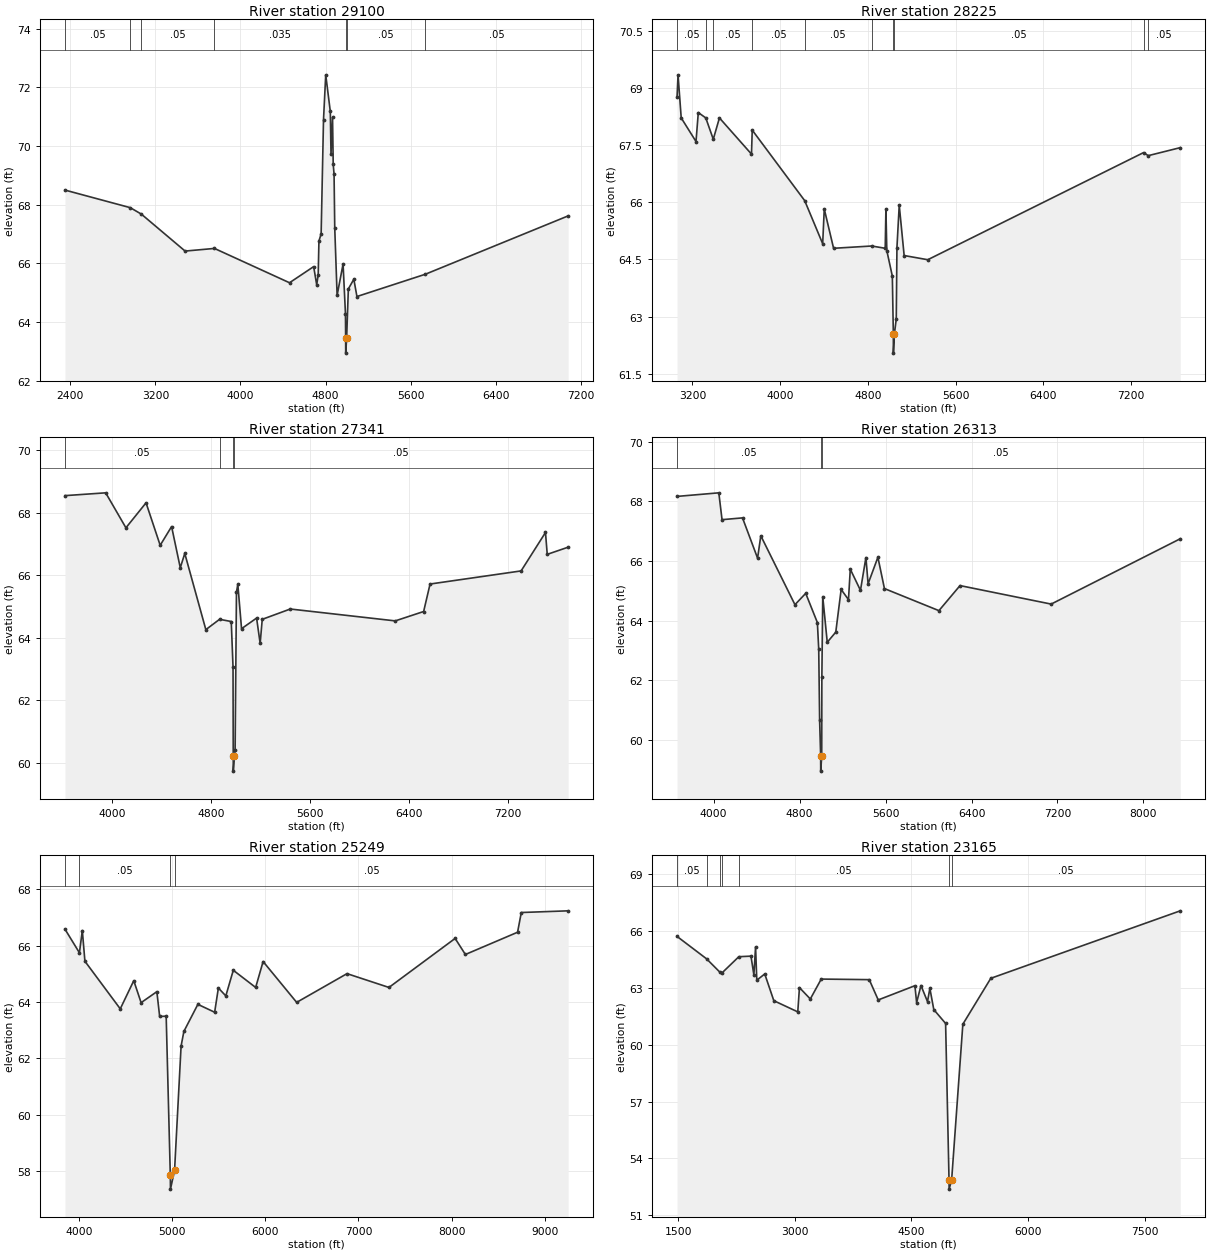
Type RM Length L Ch R = 1 ,29100   ,875,875,875
BEGIN DESCRIPTION:
Mapping XS 323480e5
END DESCRIPTION:
XS GIS Cut Line= 3
      2616282.23     13406197.22      2614215.45     13404536.08
      2612461.95     13403411.75
#Sta/Elev= 30
  2348.4    68.5  2963.1    67.9  3067.2   67.68  3478.8   66.42    3755   66.51
  4461.2   65.34  4688.4   65.89  4717.1   65.27  4731.2   65.61    4738   66.76
  4758.8   67.01  4781.1    70.9    4802   72.43  4845.1   71.18  4851.6   69.74
    4866   70.98  4872.4   69.38  4880.4   69.04  4886.8   67.21  4909.1   64.91
  4965.2   65.98  4987.5   64.29  4989.4   63.44  4989.9   62.94  4998.6   63.44
  5014.8   65.13  5066.4   65.46  5095.6   64.87  5739.2   65.63    7083   67.62
#Mann= 7 ,-1 , 0
  2348.4     .05       0  2963.1     .05       0  3067.2     .05       0
    3755    .035       0  4989.4     .04       0  4998.6     .05       0
  5739.2     .05       0
Bank Sta=4989.4,4998.6
XS Rating Curve= 0 ,0
Exp/Cntr=0.3,0.1

Type RM Length L Ch R = 1 ,28225   ,884,884,884
BEGIN DESCRIPTION:
Mapping XS 0bb24a92
END DESCRIPTION:
XS GIS Cut Line= 3
      2616515.82     13405616.64      2614984.98     13404424.95
        2612800.     13402931.51
#Sta/Elev= 30
    3060   68.75  3069.1   69.34    3098   68.21  3232.9   67.59  3253.7   68.35
  3321.9   68.21  3390.3   67.65  3446.4   68.21  3738.6   67.26  3745.3   67.89
  4223.5   66.04  4387.4   64.91  4401.9   65.82  4486.9   64.79  4834.5   64.85
  4957.4   64.79  4963.8   65.82  4971.9   64.73  5022.3   64.06  5031.5   62.54
    5032   62.04  5041.1   62.54  5058.2   62.94  5064.3   64.81  5085.2   65.92
    5130    64.6  5345.3   64.49  7312.1    67.3  7354.9   67.22  7646.6   67.43
#Mann= 10 ,-1 , 0
    3060     .05       0  3321.9     .05       0  3390.3     .05       0
  3745.3     .05       0  4223.5     .05       0  4834.5     .05       0
  5031.5     .04       0  5041.1     .05       0  7312.1     .05       0
  7354.9     .05       0
Bank Sta=5031.5,5041.1
XS Rating Curve= 0 ,0
Exp/Cntr=0.3,0.1

Type RM Length L Ch R = 1 ,27341   ,1028,1028,1028
BEGIN DESCRIPTION:
Mapping XS a5110d64
END DESCRIPTION:
XS GIS Cut Line= 3
      2616715.46     13405278.09      2615821.37     13404245.11
      2613360.79      13403146.2
#Sta/Elev= 30
  3621.9   68.55  3950.6   68.64    4114   67.52  4276.3   68.32  4390.4   66.96
  4482.5   67.56  4552.7   66.24  4588.9    66.7  4758.9   64.26  4869.7   64.59
    4964   64.52  4978.3   63.06    4980   60.23  4980.5   59.73  4989.7   60.23
  4995.1    60.4    5006   65.46    5017   65.71    5047   64.29  5168.5   64.63
  5197.2   63.82  5214.1   64.59  5440.3   64.92  6287.4   64.54  6516.5   64.84
  6568.4   65.72  7303.1   66.14  7499.8   67.37    7514   66.67  7682.9    66.9
#Mann= 4 ,-1 , 0
  3621.9     .05       0  4869.7     .05       0    4980     .04       0
  4989.7     .05       0
Bank Sta=4980,4989.7
XS Rating Curve= 0 ,0
Exp/Cntr=0.3,0.1

Type RM Length L Ch R = 1 ,26313   ,1064,1064,1064
BEGIN DESCRIPTION:
Mapping XS 23564807
END DESCRIPTION:
XS GIS Cut Line= 4
       2616815.6      13405082.9      2616884.06     13404065.77
      2616551.54     13403615.89      2613490.37     13403097.55
#Sta/Elev= 30
    3659   68.17  4047.8   68.29  4077.8   67.39  4268.3   67.45  4408.6    66.1
  4438.7   66.85  4756.4   64.54  4856.6   64.92  4965.2   63.94  4977.8   63.04
  4986.1   60.66  4995.7   59.46  4996.2   58.96  5005.6   59.46  5006.9    62.1
  5015.1   64.81    5057   63.28  5136.4   63.62  5186.5   65.05  5254.6   64.71
  5271.5   65.73  5366.2   65.02  5416.9   66.12  5437.2   65.24  5528.5   66.13
  5589.3   65.08  6096.4   64.34  6292.8   65.18  7141.1   64.56  8342.6   66.75
#Mann= 3 ,-1 , 0
    3659     .05       0  4995.7     .04       0  5005.6     .05       0
Bank Sta=4995.7,5005.6
XS Rating Curve= 0 ,0
Exp/Cntr=0.3,0.1

Type RM Length L Ch R = 1 ,25249   ,2084,2084,2084
BEGIN DESCRIPTION:
Mapping XS 65e80852
END DESCRIPTION:
XS GIS Cut Line= 4
      2617844.86     13403884.53      2617413.61     13403029.65
      2615915.78     13403020.54      2612972.29     13402981.85
#Sta/Elev= 30
  3851.1   66.59  4006.4   65.75  4037.4   66.54  4065.3   65.45  4444.5   63.76
  4589.4   64.76  4668.2   63.98  4837.2   64.37  4867.2   63.49  4937.2    63.5
  4981.5   57.86  4983.2   57.36  5027.2   58.03  5097.2   62.44  5127.2   62.96
  5277.2   63.92  5457.2   63.64  5497.2    64.5  5577.2   64.22  5657.2   65.13
  5897.2   64.52  5977.2   65.44  6337.2   63.99  6877.3   65.01  7327.3   64.52
  8037.4   66.26  8147.4   65.69  8707.4   66.48  8747.4   67.18  9250.2   67.24
#Mann= 4 ,-1 , 0
  3851.1    .035       0  4006.4     .05       0  4981.5     .04       0
  5027.2     .05       0
Bank Sta=4981.5,5027.2
XS Rating Curve= 0 ,0
Exp/Cntr=0.3,0.1

Type RM Length L Ch R = 1 ,23165   ,1404,1404,1404
BEGIN DESCRIPTION:
Mapping XS 6aa52359
END DESCRIPTION:
XS GIS Cut Line= 5
      2619288.02     13403320.29       2617744.7     13402442.29
      2616023.41     13402158.67      2614829.38     13402092.02
      2613145.36     13402612.85
#Sta/Elev= 30
  1481.5   65.71  1861.2   64.53  2036.6   63.81  2064.2    63.8    2277   64.64
  2433.4   64.67  2470.8   63.68  2492.5   65.16  2508.3    63.4  2610.7   63.73
  2727.5   62.32  3035.8   61.73  3057.5   63.01  3197.3   62.41  3337.9   63.46
  3956.1   63.43  4071.7   62.36  4543.9   63.11    4566   62.22  4622.1   63.12
  4706.1   62.27  4736.5   62.97  4787.2   61.85  4939.2   61.12  4983.2   52.88
  4984.7   52.38  5017.1   52.88  5161.2   61.08  5520.9    63.5  7960.2   67.06
#Mann= 7 ,-1 , 0
  1481.5     .05       0  1861.2     .07       0  2036.6     .05       0
  2064.2     .07       0    2277     .05       0  4983.2     .04       0
  5017.1     .05       0
Bank Sta=4983.2,5017.1
XS Rating Curve= 0 ,0
Exp/Cntr=0.3,0.1

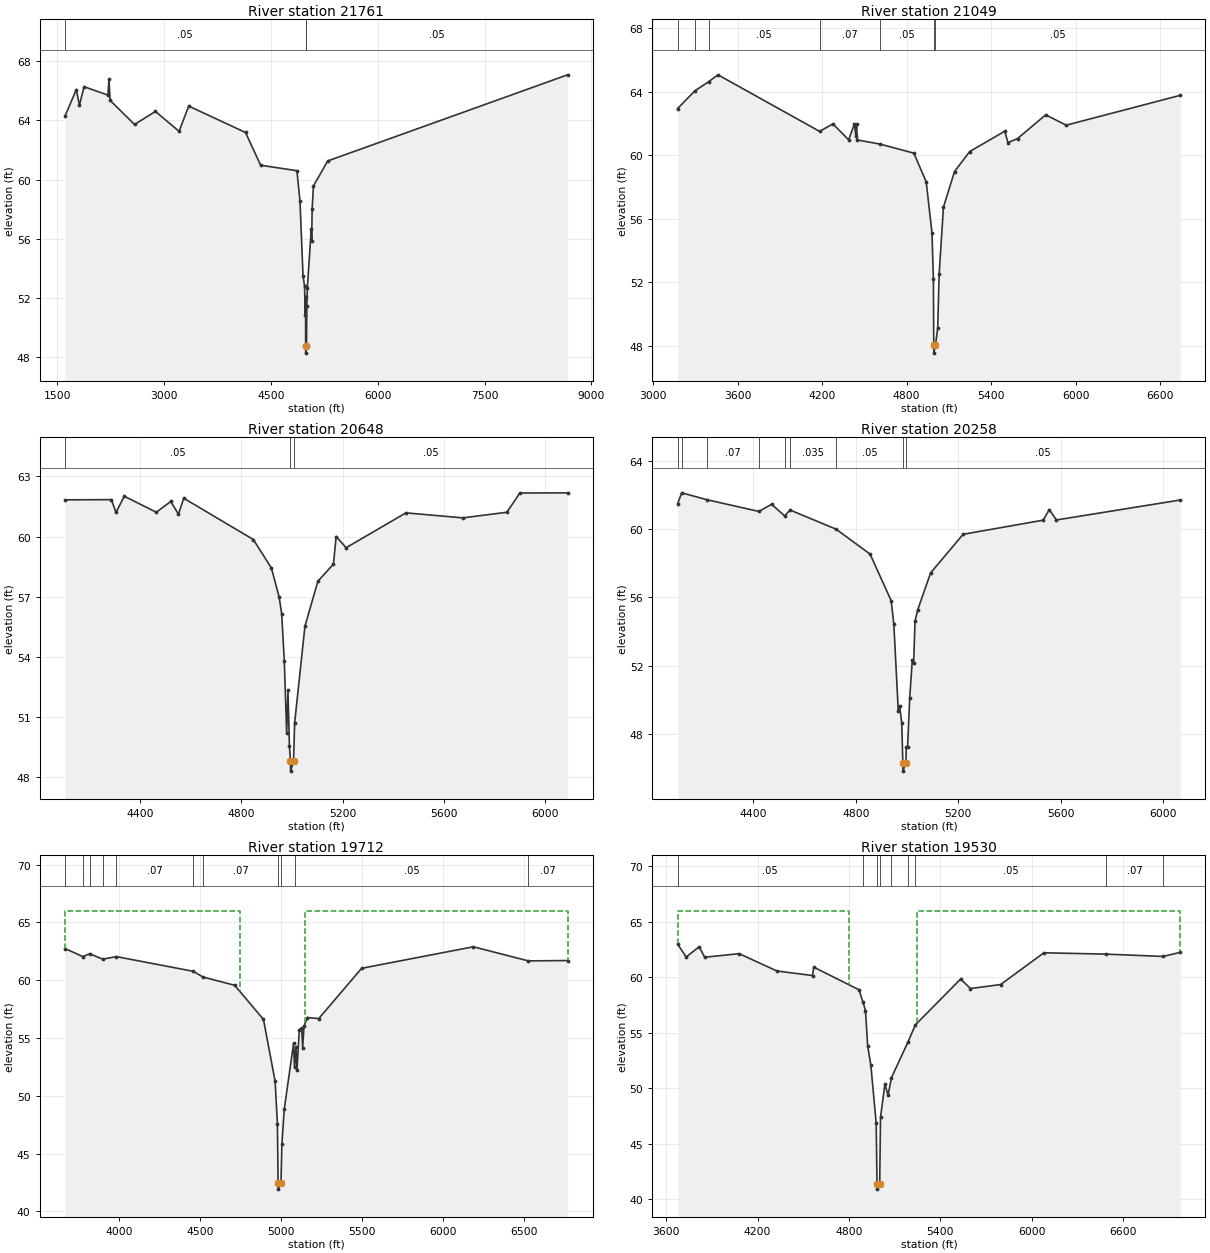
Type RM Length L Ch R = 1 ,21761   ,712,712,712
BEGIN DESCRIPTION:
Mapping XS d84984b3
END DESCRIPTION:
XS GIS Cut Line= 5
        2619554.     13402699.96      2618416.85     13401883.99
      2616818.56     13401319.15      2616131.06     13401062.21
      2613169.38      13402354.1
#Sta/Elev= 30
  1604.4   64.27    1764   66.07  1808.2   65.02  1873.3   66.27  2208.5    65.7
  2223.3   66.78    2238   65.35  2581.8   63.72  2875.3    64.6  3207.5   63.26
  3343.1   64.96  4140.8   63.18  4352.9   60.97  4862.9    60.6  4905.8   58.54
  4948.5   53.52  4969.9   52.82  4978.8   50.89  4984.1   52.11  4985.4   48.79
  4985.9   48.29  4997.1   48.79  5001.9    51.5  5009.1   52.67  5064.3   56.68
  5069.7   55.87  5076.6   58.01  5094.6   59.57    5296   61.26  8664.3   67.07
#Mann= 3 ,-1 , 0
  1604.4     .05       0  4985.4     .05       0  4997.1     .05       0
Bank Sta=4985.4,4997.1
XS Rating Curve= 0 ,0
Exp/Cntr=0.3,0.1

Type RM Length L Ch R = 1 ,21049   ,401,401,401
BEGIN DESCRIPTION:
Mapping XS a4105589
END DESCRIPTION:
XS GIS Cut Line= 3
      2618566.08     13401050.41      2616694.95     13400674.24
      2615093.38     13401116.95
#Sta/Elev= 30
  3173.5   62.93  3297.1   64.05  3392.9   64.61  3460.2   65.05  4181.9   61.49
  4276.2   61.96  4388.3   60.96  4429.2   61.95  4439.2    61.2  4444.3   61.97
  4449.6   60.95  4610.9   60.69  4851.2   60.12  4939.2   58.31    4980   55.11
  4990.2   52.18  4992.7   48.03  4993.2   47.53  5004.8   48.03  5020.8   49.11
    5031    52.5  5061.6   56.72  5140.1   58.96    5248   60.22    5497    61.5
  5519.7   60.78  5588.4   61.04  5787.5   62.53  5933.7   61.88  6743.7   63.76
#Mann= 7 ,-1 , 0
  3173.5     .05       0  3297.1    .035       0  3392.9     .05       0
  4181.9     .07       0  4610.9     .05       0  4992.7     .05       0
  5004.8     .05       0
Bank Sta=4992.7,5004.8
XS Rating Curve= 0 ,0
Exp/Cntr=0.3,0.1

Type RM Length L Ch R = 1 ,20648   ,390,390,390
BEGIN DESCRIPTION:
Mapping XS 951e8649
END DESCRIPTION:
XS GIS Cut Line= 3
      2617655.07     13400489.36       2616769.6     13400315.74
      2615710.61     13400541.42
#Sta/Elev= 30
  4103.6   61.83  4287.1   61.84  4305.3    61.2    4338   62.01  4464.7   61.21
  4521.5   61.75    4552   61.11  4572.8   61.91  4847.6   59.85  4918.9   58.43
  4949.5   56.98  4959.7   56.13  4969.9    53.8  4979.4   50.17  4984.5   52.36
  4990.2   49.54  4994.3   48.79  4994.8   48.29  5006.5   48.79  5010.8    50.7
  5051.5   55.52  5102.7   57.77    5164   58.62  5174.8      60  5214.1   59.44
  5450.3   61.18  5675.2   60.93    5849   61.21  5900.2   62.17  6088.7   62.18
#Mann= 3 ,-1 , 0
  4103.6     .05       0  4994.3     .05       0  5006.5     .05       0
Bank Sta=4994.3,5006.5
XS Rating Curve= 0 ,0
Exp/Cntr=0.3,0.1

Type RM Length L Ch R = 1 ,20258   ,546,546,546
BEGIN DESCRIPTION:
Mapping XS bfe3ce24
END DESCRIPTION:
XS GIS Cut Line= 3
      2617594.27     13400159.49       2616726.2     13399942.47
      2615701.89     13400246.29
#Sta/Elev= 30
    4104   61.48  4119.7   62.13  4220.3   61.72  4421.4   61.04  4471.1   61.46
    4522   60.78  4543.4   61.12  4723.1      60  4855.7   58.54  4938.2   55.81
  4948.5   54.42  4965.8   49.36    4971   49.64  4979.4   48.65  4983.6   46.33
  4984.1   45.83  4995.8   46.33  4996.8   47.22    5002   47.22  5010.5   50.12
  5020.5   52.31  5025.7   52.15  5031.3   54.62  5041.8   55.28  5092.1   57.44
  5219.1    59.7    5532   60.53  5555.4   61.15  5583.4   60.54  6067.2   61.71
#Mann= 9 ,-1 , 0
    4104     .07       0  4119.7     .05       0  4220.3     .07       0
  4421.4    .035       0    4522     .05       0  4543.4    .035       0
  4723.1     .05       0  4983.6     .05       0  4995.8     .05       0
Bank Sta=4983.6,4995.8
XS Rating Curve= 0 ,0
Exp/Cntr=0.3,0.1

Type RM Length L Ch R = 1 ,19712   ,182,182,182
BEGIN DESCRIPTION:
Mapping XS 33a536ca
END DESCRIPTION:
XS GIS Cut Line= 3
       2617763.2     13400259.95      2616718.95     13399431.84
      2615324.35     13398339.06
#Sta/Elev= 30
  3666.7   62.74  3777.6   62.04    3820   62.29  3900.3   61.82  3984.5   62.04
  4459.3   60.77  4518.2   60.28    4715   59.56  4892.9   56.61    4965   51.25
    4979    47.6  4983.5   42.43    4984   41.93    5001   42.43  5006.6   45.79
  5021.1   48.82  5078.9   54.54  5084.7   52.45  5093.4   54.24  5099.7   52.24
  5114.2   55.71  5128.7    55.9    5135   54.13  5143.1   56.02  5163.9   56.77
  5234.5   56.68  5499.3   61.03  6189.2   62.89  6528.7   61.67  6771.2    61.7
#Mann= 11 ,-1 , 0
  3666.7     .07       0  3777.6     .05       0    3820     .07       0
  3900.3     .05       0  3984.5     .07       0  4459.3     .05       0
  4518.2     .07       0  4983.5     .05       0    5001     .07       0
  5084.7     .05       0  6528.7     .07       0
#XS Ineff= 2 ,-1
    3667    4750      66    5150    7000      66
Permanent Ineff=
       F       F
Bank Sta=4983.5,5001
XS Rating Curve= 0 ,0
Exp/Cntr=0.3,0.1

Type RM Length L Ch R = 1 ,19530   ,357,357,357
BEGIN DESCRIPTION:
Mapping XS 409d762f
END DESCRIPTION:
XS GIS Cut Line= 3
      2617852.63     13400167.08       2616858.7     13399312.05
      2615319.53     13398050.36
#Sta/Elev= 30
  3674.7      63  3731.2   61.84  3816.7   62.77  3851.9   61.82  4079.1   62.14
  4327.1   60.58  4560.8   60.17  4568.4   60.93  4865.8   58.89  4892.1   57.77
  4908.6   57.01  4922.9   53.83  4943.7    52.1  4978.8   46.89  4984.2   41.43
  4984.7   40.93  5001.8   41.43  5007.4   47.42  5036.1   50.39  5056.9   49.39
  5078.9   50.96  5187.1   54.17  5236.2   55.73  5533.7   59.86    5598      59
  5796.1   59.36  6080.3   62.22  6487.3    62.1  6863.6   61.89    6976   62.26
#Mann= 9 ,-1 , 0
  3674.7     .05       0  4892.1     .07       0  4984.2     .05       0
  5001.8     .07       0  5078.9     .05       0  5187.1     .07       0
  5236.2     .05       0  6487.3     .07       0  6863.6     .05       0
#XS Ineff= 2 ,-1
    3674    4800      66    5250    6977      66
Permanent Ineff=
       F       F
Bank Sta=4984.2,5001.8
XS Rating Curve= 0 ,0
Exp/Cntr=0.3,0.1

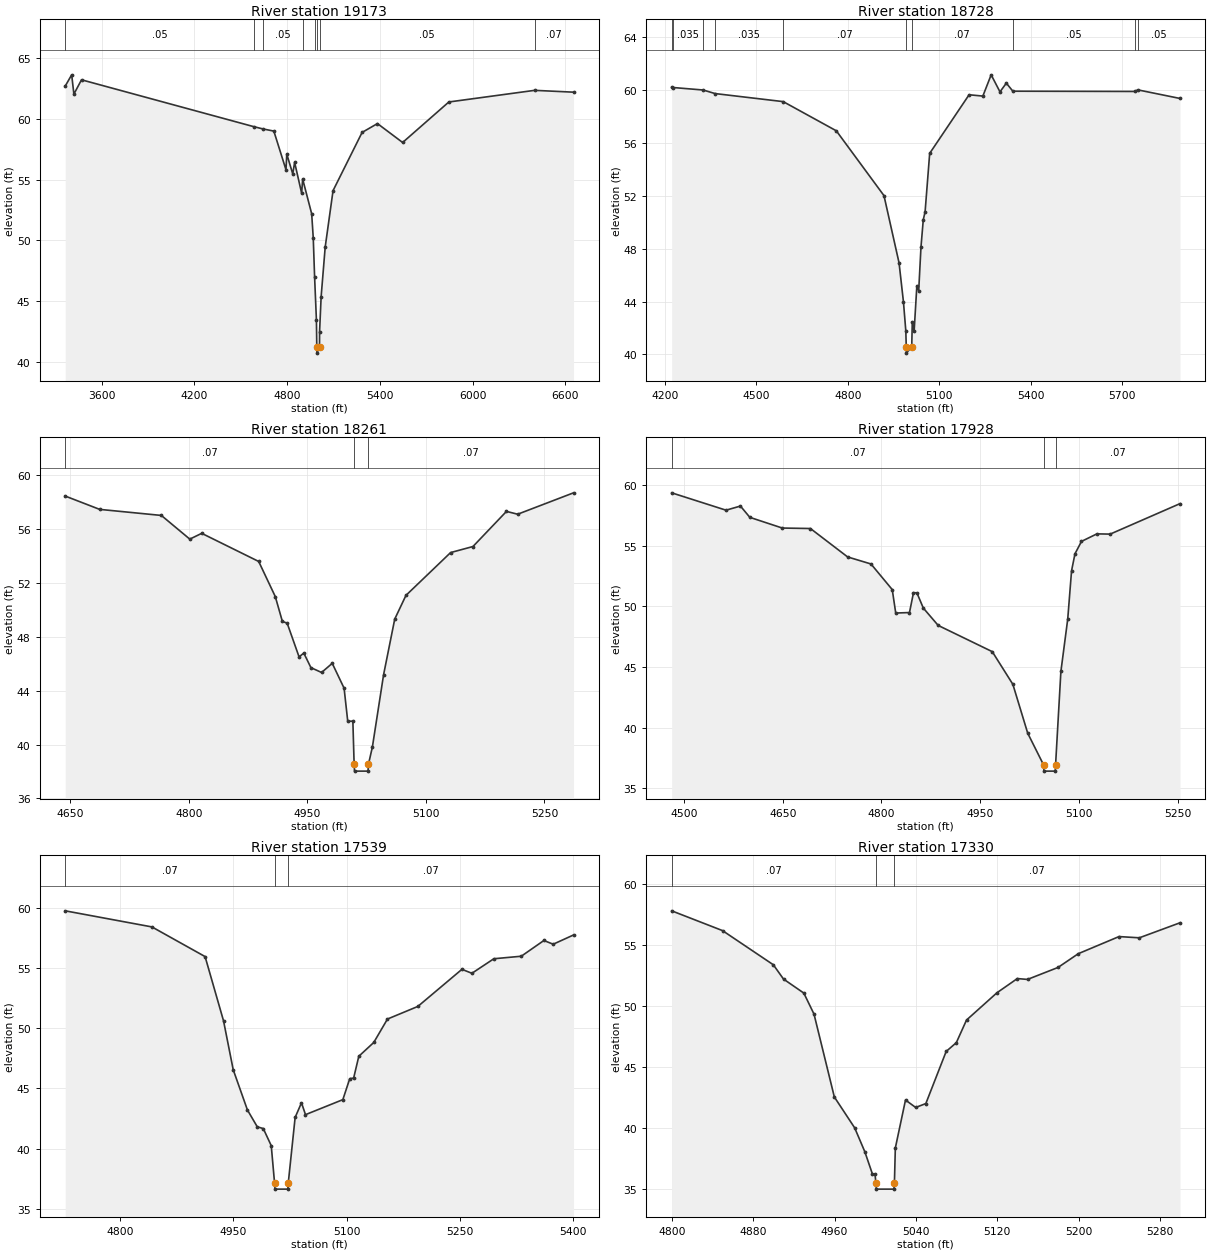
Type RM Length L Ch R = 1 ,19173   ,445,445,445
BEGIN DESCRIPTION:
Mapping XS 33a7b9ef
END DESCRIPTION:
XS GIS Cut Line= 4
      2618008.91     13400049.93      2617173.51     13399079.83
      2616540.54     13398951.95      2615481.54     13398093.06
#Sta/Elev= 30
  3363.7   62.72  3405.6   63.65  3419.9   62.06  3469.2   63.24  4582.8   59.38
  4642.6   59.19  4713.8   59.01  4792.4   55.82  4797.5   57.11  4836.2   55.48
  4848.3   56.43  4893.9   53.88  4900.2   55.06  4958.7   52.19  4968.9   50.19
  4977.7   46.95  4989.3   43.45  4991.8    41.2  4992.3    40.7  5009.4    41.2
  5009.7   42.44  5019.9   45.36  5046.2   49.45    5097    54.1  5284.9    58.9
  5384.3   59.63  5547.3   58.07  5846.2   61.41  6401.3   62.37  6653.2   62.22
#Mann= 8 ,-1 , 0
  3363.7     .05       0  4582.8    .035       0  4642.6     .05       0
  4900.2     .07       0  4977.7     .05       0  4991.8     .05       0
  5009.4     .05       0  6401.3     .07       0
Bank Sta=4991.8,5009.4
XS Rating Curve= 0 ,0
Exp/Cntr=0.3,0.1

Type RM Length L Ch R = 1 ,18728   ,467,467,467
BEGIN DESCRIPTION:
DRY KUY CREEK 39.0
END DESCRIPTION:
XS GIS Cut Line= 4
      2617475.01     13399275.01        2616975.       13398675.
       2616837.8     13398469.19      2616338.66     13398072.44
#Sta/Elev= 30
    4223   60.22  4226.9   60.21  4326.1   60.02  4365.4   59.75  4588.6   59.14
  4762.6   56.93  4918.8   52.02  4968.2   46.93  4982.6   43.98  4990.4   41.77
  4991.8   40.59  4992.3   40.09  5009.8   40.59  5011.6   42.47  5017.6   41.74
  5026.6    45.2  5032.6   44.81  5040.1   48.13  5047.6   50.19  5053.6    50.8
  5068.6   55.22  5197.8   59.66  5242.9   59.56  5270.1   61.17    5299   59.88
  5319.8   60.54  5341.2   59.93  5740.5   59.91    5751   60.03    5889   59.38
#Mann= 10 ,-1 , 0
    4223     .05       0  4226.9    .035       0  4326.1     .05       0
  4365.4    .035       0  4588.6     .07       0  4991.8     .05       0
  5009.8     .07       0  5341.2     .05       0  5740.5    .035       0
    5751     .05       0
Bank Sta=4991.8,5009.8
XS Rating Curve= 0 ,0
Exp/Cntr=0.3,0.1

Type RM Length L Ch R = 1 ,18261   ,333,333,333
BEGIN DESCRIPTION:
DRY KUY CREEK 38.0
END DESCRIPTION:
XS GIS Cut Line= 3
        2617575.       13398775.        2617375.       13398475.
        2617175.       13398275.
#Sta/Elev= 30
  4643.5   58.47  4687.1   57.48  4765.2   57.03  4801.2   55.27  4816.3    55.7
  4888.4   53.61  4909.4      51  4918.4   49.15  4924.4   49.03  4939.5   46.52
  4945.5    46.8  4954.5   45.72    4968   45.36  4981.5   46.04  4996.5   44.19
  5001.1   41.74  5007.6   41.74  5009.2   38.53  5009.7   38.03  5026.8   38.03
  5027.3   38.53  5032.3   39.82  5046.5    45.2  5060.6   49.33  5074.8   51.09
  5131.3   54.27  5159.6   54.72    5202   57.33  5216.2   57.12  5286.9   58.71
#Mann= 3 ,-1 , 0
  4643.5     .07       0  5009.2     .05       0  5027.3     .07       0
Bank Sta=5009.2,5027.3
XS Rating Curve= 0 ,0
Exp/Cntr=0.3,0.1

Type RM Length L Ch R = 1 ,17928   ,389,389,389
BEGIN DESCRIPTION:
Mapping XS 5a97d377
END DESCRIPTION:
XS GIS Cut Line= 5
      2617807.49     13398689.66      2617580.93     13398494.34
      2617528.84     13398330.28      2617474.16     13398145.38
      2617375.19     13398101.11
#Sta/Elev= 30
  4481.2   59.34  4563.8   57.91  4585.7   58.25    4600   57.32  4649.3   56.44
  4692.1    56.4  4748.6   54.06  4784.1   53.48  4816.4   51.37  4821.7   49.44
  4842.6   49.48  4848.7   51.12  4853.9    51.1  4863.6   49.85  4886.2   48.42
  4968.4   46.26  4999.7   43.57  5022.3   39.54  5046.5   36.92    5047   36.42
  5064.1   36.42  5064.6   36.92  5072.7   44.63  5083.1   48.95  5088.9   52.92
  5094.1   54.32    5104   55.34  5127.4   55.96  5147.6   55.94  5253.7   58.45
#Mann= 3 ,-1 , 0
  4481.2     .07       0  5046.5     .05       0  5064.6     .07       0
Bank Sta=5046.5,5064.6
XS Rating Curve= 0 ,0
Exp/Cntr=0.3,0.1

Type RM Length L Ch R = 1 ,17539   ,209,209,209
BEGIN DESCRIPTION:
Mapping XS 96e6ac23
END DESCRIPTION:
XS GIS Cut Line= 3
      2618034.05     13398338.09       2617627.8     13398205.28
      2617422.06     13398072.45
#Sta/Elev= 30
  4727.9   59.79  4842.6   58.45  4912.9   55.98  4937.3   50.63  4950.1   46.56
  4968.9   43.21  4981.9   41.81  4989.9   41.66  5000.4   40.24  5004.8   37.12
  5005.3   36.62  5022.4   36.62  5022.9   37.12    5032   42.59  5040.4   43.81
  5045.7   42.82  5095.1   44.07  5104.2   45.81  5109.4   45.87  5116.2   47.68
    5136   48.83  5154.1   50.78  5194.3   51.83  5252.6   54.92  5265.8   54.59
  5294.8    55.8  5331.1   56.01    5361   57.32  5373.3   57.01  5400.2   57.78
#Mann= 3 ,-1 , 0
  4727.9     .07       0  5004.8     .05       0  5022.9     .07       0
Bank Sta=5004.8,5022.9
XS Rating Curve= 0 ,0
Exp/Cntr=0.3,0.1

Type RM Length L Ch R = 1 ,17330   ,426,426,426
BEGIN DESCRIPTION:
DRY KUY CREEK 36.0
END DESCRIPTION:
XS GIS Cut Line= 3
      2617975.02       13398075.        2617775.       13398075.
      2617475.02       13398075.
#Sta/Elev= 30
  4799.8   57.78  4849.8   56.16  4899.8   53.36  4909.8   52.19  4929.8   51.04
  4939.8   49.32  4959.8   42.53  4979.8      40  4989.8   38.04  4997.3   36.21
  4999.8   36.21  5000.7   35.48  5001.2   34.98  5018.4   34.98  5018.9   35.48
  5019.8   38.35  5029.8   42.28  5039.8   41.67  5049.8   41.99  5069.8   46.26
  5079.8   46.98  5089.8   48.83  5119.8   51.07  5139.8   52.23  5149.8   52.16
  5179.8   53.14  5199.8   54.27  5239.8   55.67  5259.8   55.57  5299.8    56.8
#Mann= 3 ,-1 , 0
  4799.8     .07       0  5000.7     .05       0  5018.9     .07       0
Bank Sta=5000.7,5018.9
XS Rating Curve= 0 ,0
Exp/Cntr=0.3,0.1