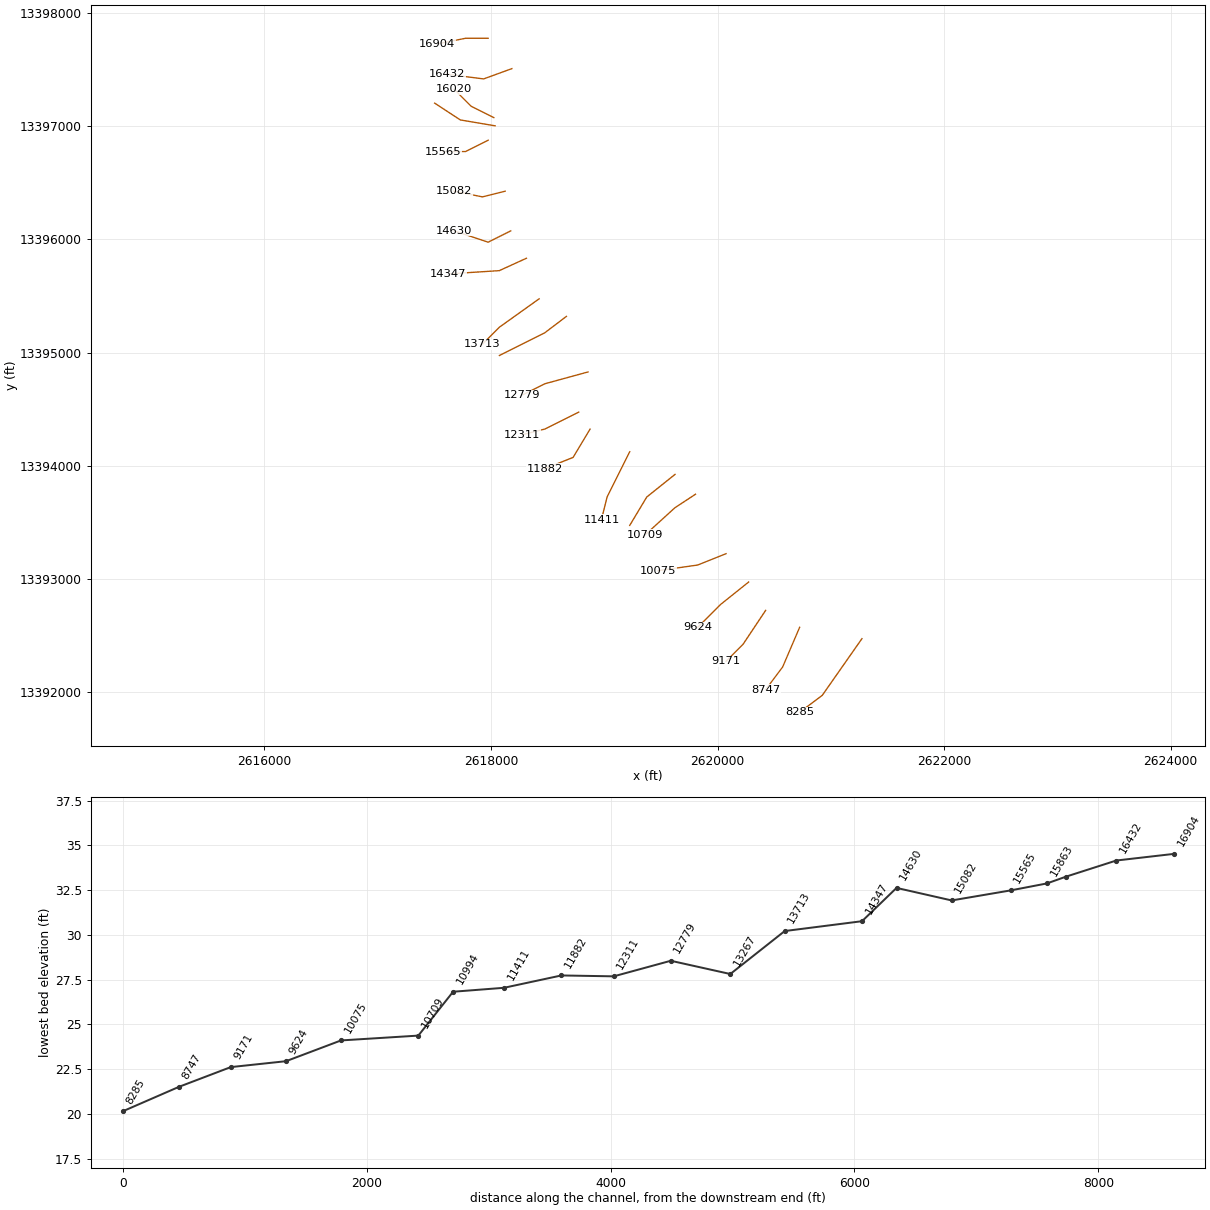
HEC-RAS study DRY KUY CREEK.prj: DRY KUY CREEK Base Level Engineering

--- DRY KUY CREEK.g01 (geometry) --- (continued)

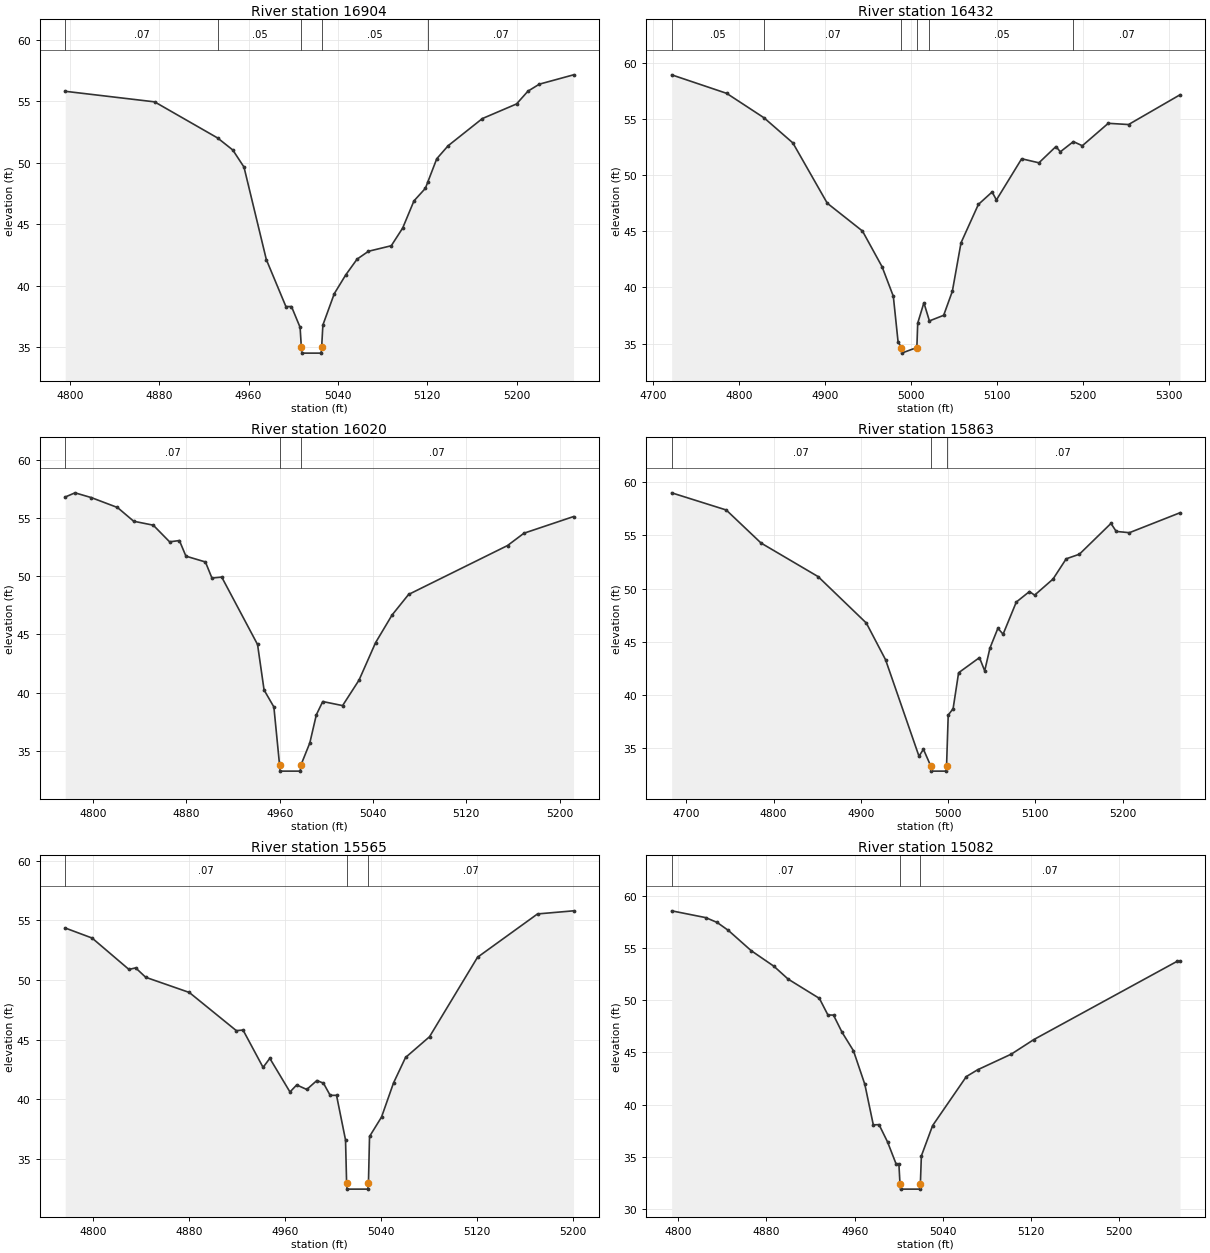
Type RM Length L Ch R = 1 ,16904   ,472,472,472
BEGIN DESCRIPTION:
DRY KUY CREEK 35.0
END DESCRIPTION:
XS GIS Cut Line= 3
      2617974.97       13397775.        2617775.       13397775.
      2617525.02       13397725.
#Sta/Elev= 30
  4795.9   55.83  4875.9   54.97  4932.3   52.03  4945.9   51.05  4955.9   49.66
  4975.9   42.13  4993.4   38.31  4998.4   38.31  5006.1   36.62  5007.2   35.02
  5007.7   34.52  5024.9   34.52  5025.4   35.02  5026.5   36.81  5036.7   39.36
  5046.9   40.88  5057.1   42.17  5067.3   42.81  5087.7   43.26  5097.9    44.7
    5108   46.91  5118.2   47.93  5120.4   48.45  5128.4   50.34  5138.6    51.4
  5169.2   53.61  5199.8    54.8    5210   55.84  5220.2   56.41  5250.8   57.17
#Mann= 5 ,-1 , 0
  4795.9     .07       0  4932.3     .05       0  5007.2     .05       0
  5025.4     .05       0  5120.4     .07       0
Bank Sta=5007.2,5025.4
XS Rating Curve= 0 ,0
Exp/Cntr=0.3,0.1

Type RM Length L Ch R = 1 ,16432   ,412,412,412
BEGIN DESCRIPTION:
Mapping XS 894fb749
END DESCRIPTION:
XS GIS Cut Line= 3
      2618185.12     13397507.37      2617935.09     13397416.22
      2617612.19     13397457.88
#Sta/Elev= 30
  4721.2   58.95  4785.2    57.3  4828.7   55.12  4862.3   52.88  4902.3   47.51
  4943.3   45.03  4966.1   41.85  4979.2   39.22  4984.7   35.18  4988.4   34.65
  4988.9   34.15  5006.6   34.65  5007.6   36.82  5014.8   38.64  5021.2   37.02
  5037.8   37.52  5047.9   39.66    5058   43.98  5078.2    47.4  5094.2   48.51
  5099.2    47.8  5128.6   51.47  5148.7   51.11  5168.5   52.56  5173.6   52.09
  5188.8      53  5199.2   52.63  5229.4   54.63    5253   54.52  5312.9   57.17
#Mann= 6 ,-1 , 0
  4721.2     .05       0  4828.7     .07       0  4988.4     .05       0
  5006.6     .07       0  5021.2     .05       0  5188.8     .07       0
Bank Sta=4988.4,5006.6
XS Rating Curve= 0 ,0
Exp/Cntr=0.3,0.1

Type RM Length L Ch R = 1 ,16020   ,157,157,157
BEGIN DESCRIPTION:
DRY KUY CREEK 33.0
END DESCRIPTION:
XS GIS Cut Line= 3
      2618025.03     13397074.98        2617825.       13397175.
      2617674.98     13397325.02
#Sta/Elev= 30
  4776.1    56.8  4784.5   57.16  4798.5   56.75  4820.9    55.9  4834.8   54.72
  4851.6   54.38  4865.6   52.95    4874   53.06  4879.6   51.72  4896.3   51.22
  4901.9   49.84  4910.3   49.92    4941   44.13  4946.6   40.22    4955   38.76
  4959.9   33.75  4960.4   33.25  4977.6   33.25  4978.1   33.75  4985.8   35.67
  4991.4   38.09  4996.9   39.23  5013.9   38.88    5028   41.07  5042.2   44.29
  5056.3   46.66  5070.5   48.43  5155.3   52.63  5169.4   53.69  5211.9   55.12
#Mann= 3 ,-1 , 0
  4776.1     .07       0  4959.9     .05       0  4978.1     .07       0
Bank Sta=4959.9,4978.1
XS Rating Curve= 0 ,0
Exp/Cntr=0.3,0.1

Type RM Length L Ch R = 1 ,15863   ,298,298,298
BEGIN DESCRIPTION:
Mapping XS 3d102124
END DESCRIPTION:
XS GIS Cut Line= 3
      2618036.62     13397002.16      2617729.36     13397054.24
       2617502.8     13397202.68
#Sta/Elev= 30
  4683.3   58.98  4745.8   57.37  4785.7   54.27  4851.1   51.12  4906.4   46.76
  4928.4   43.32  4966.7   34.27  4971.8   34.92  4980.1   33.37  4980.6   32.87
  4997.8   32.87  4998.3   33.37  5000.2   38.13  5005.8   38.73  5012.1    42.1
    5036   43.52    5042   42.28    5048   44.41  5057.1   46.27  5063.1   45.72
  5078.2   48.73  5093.3   49.72  5099.2   49.38  5120.3   50.89  5135.4   52.79
  5150.5   53.22  5186.7   56.11  5192.7   55.36  5207.8   55.24  5265.8   57.11
#Mann= 3 ,-1 , 0
  4683.3     .07       0  4980.1     .05       0  4998.3     .07       0
Bank Sta=4980.1,4998.3
XS Rating Curve= 0 ,0
Exp/Cntr=0.3,0.1

Type RM Length L Ch R = 1 ,15565   ,483,483,483
BEGIN DESCRIPTION:
DRY KUY CREEK 32.0
END DESCRIPTION:
XS GIS Cut Line= 3
      2617975.02     13396875.01        2617775.       13396775.
      2617575.03       13396775.
#Sta/Elev= 30
  4776.8   54.36  4799.2   53.52  4829.9   50.89  4835.5   51.02  4843.9   50.23
  4880.2   48.96  4919.4   45.76    4925   45.81  4941.7   42.68  4947.3   43.44
  4964.1   40.62  4969.7   41.21  4978.1   40.83  4986.5   41.58    4992   41.36
  4997.6   40.34  5002.9   40.34  5010.4    36.6  5011.3   32.98  5011.8   32.48
    5029   32.48  5029.5   32.98  5030.4   36.89  5040.4   38.52  5050.4   41.38
  5060.4   43.51  5080.4   45.25  5120.4   51.91  5170.4   55.54  5200.4    55.8
#Mann= 3 ,-1 , 0
  4776.8     .07       0  5011.3     .05       0  5029.5     .07       0
Bank Sta=5011.3,5029.5
XS Rating Curve= 0 ,0
Exp/Cntr=0.3,0.1

Type RM Length L Ch R = 1 ,15082   ,452,452,452
BEGIN DESCRIPTION:
DRY KUY CREEK 31.0
END DESCRIPTION:
XS GIS Cut Line= 3
      2618124.96     13396424.99        2617925.       13396375.
      2617674.96     13396425.01
#Sta/Elev= 30
    4794   58.55  4824.9    57.9  4835.2   57.44  4845.5   56.67  4866.1   54.74
  4886.7   53.25  4899.6   52.02    4928   50.17  4935.7   48.59  4940.8   48.57
  4948.6   46.92  4958.9   45.16  4969.2   41.95  4976.9   38.07  4982.1   38.09
  4989.8   36.44  4997.5   34.35  5000.1   34.35  5001.1   32.42  5001.6   31.92
  5019.1   31.92  5019.6   32.42  5020.5    35.1  5030.7      38  5061.3   42.69
  5071.5   43.34  5102.1   44.84  5122.5   46.23  5252.5   53.72  5255.1   53.72
#Mann= 3 ,-1 , 0
    4794     .07       0  5001.1     .05       0  5019.6     .07       0
Bank Sta=5001.1,5019.6
XS Rating Curve= 0 ,0
Exp/Cntr=0.3,0.1

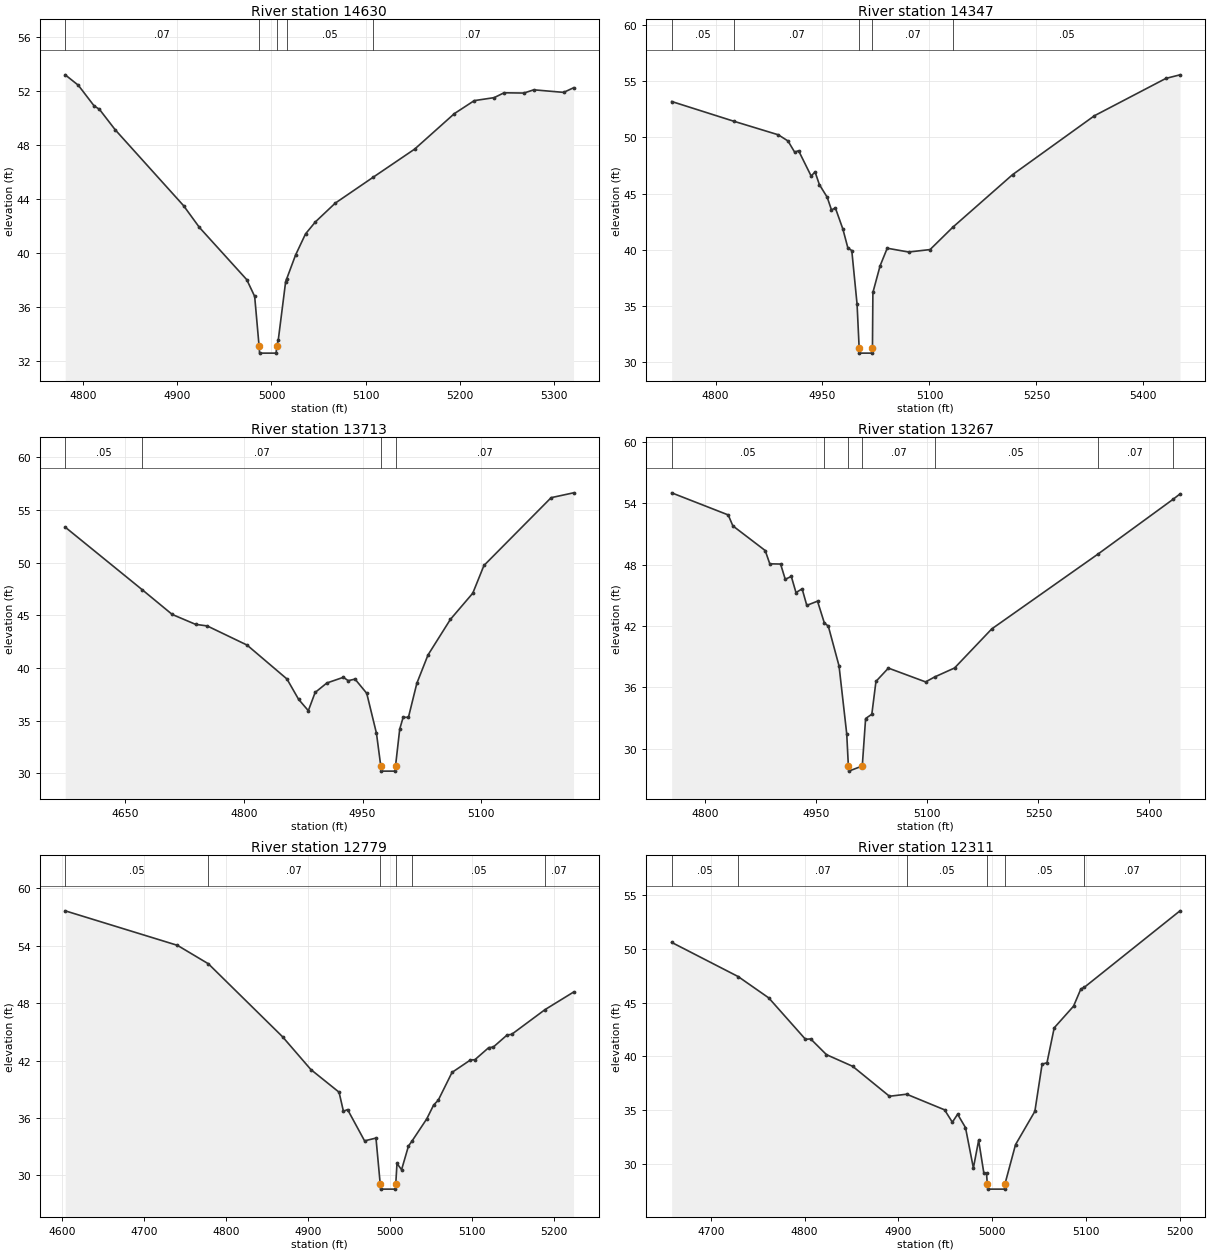
Type RM Length L Ch R = 1 ,14630   ,283,283,283
BEGIN DESCRIPTION:
DRY KUY CREEK 30.0
END DESCRIPTION:
XS GIS Cut Line= 3
      2618174.97     13396074.98        2617975.       13395975.
        2617675.       13396075.
#Sta/Elev= 30
    4781   53.23  4794.9   52.46  4811.7   50.93  4817.3   50.68  4834.1   49.16
  4906.7   43.54  4923.5   41.93  4973.8   38.06  4982.2   36.82  4986.9   33.12
  4987.4   32.62    5005   32.62  5005.5   33.12  5007.2   33.56  5015.1   37.92
  5016.3   38.14  5025.6   39.88  5036.2   41.45  5046.7   42.34  5067.8   43.73
  5107.9   45.64  5152.1   47.73  5194.3   50.36  5215.4   51.32  5236.5   51.54
    5247    51.9  5268.1   51.88  5278.6   52.12  5310.3   51.93  5320.8   52.27
#Mann= 5 ,-1 , 0
    4781     .07       0  4986.9     .05       0  5005.5     .07       0
  5016.3     .05       0  5107.9     .07       0
Bank Sta=4986.9,5005.5
XS Rating Curve= 0 ,0
Exp/Cntr=0.3,0.1

Type RM Length L Ch R = 1 ,14347   ,634,634,634
BEGIN DESCRIPTION:
Mapping XS e8f44d62
END DESCRIPTION:
XS GIS Cut Line= 3
      2618313.41     13395833.26      2618073.82     13395723.88
      2617625.23     13395694.86
#Sta/Elev= 30
  4738.5   53.21  4825.6   51.45    4888   50.24  4901.6   49.69    4911   48.69
  4916.5   48.82  4934.1   46.56  4939.6   46.93  4945.6    45.8  4956.6   44.67
  4962.6   43.54  4968.1   43.71  4978.6   41.83  4985.6   40.15  4991.1   39.91
  4998.5   35.13  5001.4   31.26  5001.9   30.76  5019.6   30.76  5020.1   31.26
  5020.7   36.17  5030.8   38.55  5040.8   40.12  5070.8   39.78  5100.9      40
  5132.9      42  5216.5   46.68  5331.4   51.94  5431.6   55.27  5451.4   55.59
#Mann= 5 ,-1 , 0
  4738.5     .05       0  4825.6     .07       0  5001.4     .05       0
  5020.1     .07       0  5132.9     .05       0
Bank Sta=5001.4,5020.1
XS Rating Curve= 0 ,0
Exp/Cntr=0.3,0.1

Type RM Length L Ch R = 1 ,13713   ,446,446,446
BEGIN DESCRIPTION:
DRY KUY CREEK 28.0
END DESCRIPTION:
XS GIS Cut Line= 3
        2618425.       13395475.        2618075.       13395225.
      2617924.97     13395074.97
#Sta/Elev= 30
  4574.2   53.38  4671.3   47.45  4709.4   45.09  4738.9   44.15  4753.6      44
    4804   42.18  4854.4   38.96  4869.1   37.03  4881.4   35.95    4890   37.68
  4904.8   38.58  4925.7   39.12  4931.8    38.8  4940.4   38.95  4955.2    37.6
  4967.5    33.8  4972.9   30.71  4973.4   30.21  4991.1   30.21  4991.6   30.71
  4996.9   34.21  5001.2   35.32  5007.9   35.32  5018.5   38.55  5032.6   41.24
  5060.9   44.62  5089.2   47.11  5103.3   49.74  5188.2   56.18  5216.5   56.64
#Mann= 4 ,-1 , 0
  4574.2     .05       0  4671.3     .07       0  4972.9     .05       0
  4991.6     .07       0
Bank Sta=4972.9,4991.6
XS Rating Curve= 0 ,0
Exp/Cntr=0.3,0.1

Type RM Length L Ch R = 1 ,13267   ,488,488,488
BEGIN DESCRIPTION:
DRY KUY CREEK 27.0
END DESCRIPTION:
XS GIS Cut Line= 3
      2618666.04     13395319.89        2618475.       13395175.
      2618074.98     13394974.99
#Sta/Elev= 30
  4754.4   55.01  4830.8   52.85  4837.1   51.78  4880.8   49.37    4887   48.07
  4901.6   48.05  4907.9   46.56  4916.1   46.84  4922.4   45.26  4930.7   45.63
    4937   44.01  4951.5   44.42  4960.7    42.3  4966.1   41.98  4980.6   38.09
    4991   31.44  4993.2   28.31  4993.7   27.81    5012   28.31  5016.5   32.95
  5024.9   33.37  5030.5   36.58  5047.3   37.88  5097.6   36.53  5109.7   37.01
  5136.7   37.89    5187   41.71  5330.1      49  5431.7   54.36  5441.4    54.9
#Mann= 7 ,-1 , 0
  4754.4     .05       0  4960.7     .07       0  4993.2     .05       0
    5012     .07       0  5109.7     .05       0  5330.1     .07       0
  5431.7     .05       0
Bank Sta=4993.2,5012
XS Rating Curve= 0 ,0
Exp/Cntr=0.3,0.1

Type RM Length L Ch R = 1 ,12779   ,468,468,468
BEGIN DESCRIPTION:
DRY KUY CREEK 26.0
END DESCRIPTION:
XS GIS Cut Line= 3
        2618857.     13394829.42        2618475.       13394725.
      2618275.02     13394625.01
#Sta/Elev= 30
  4603.9   57.66  4740.7   54.05  4778.4   52.12  4868.8   44.49  4903.3   41.06
  4937.7   38.69    4943    36.7  4948.1   36.87  4968.8    33.6  4982.7   33.89
  4987.9   29.05  4988.4   28.55  5006.3   28.55  5006.8   29.05  5008.3   31.24
  5013.9   30.58  5022.3   33.06  5026.4   33.55  5044.6    35.9    5053   37.35
  5058.6   37.85  5075.4   40.76  5097.7   42.05  5103.3   42.09  5120.1   43.35
  5125.7   43.41  5142.5   44.67  5148.1   44.74  5188.8   47.33  5223.5   49.16
#Mann= 6 ,-1 , 0
  4603.9     .05       0  4778.4     .07       0  4987.9     .05       0
  5006.8     .07       0  5026.4     .05       0  5188.8     .07       0
Bank Sta=4987.9,5006.8
XS Rating Curve= 0 ,0
Exp/Cntr=0.3,0.1

Type RM Length L Ch R = 1 ,12311   ,429,429,429
BEGIN DESCRIPTION:
DRY KUY CREEK 25.0
END DESCRIPTION:
XS GIS Cut Line= 3
      2618774.97     13394474.98        2618475.       13394325.
      2618275.03     13394275.01
#Sta/Elev= 30
  4658.4   50.58  4729.2   47.41  4761.8   45.43  4800.9   41.59  4806.5   41.62
  4823.3   40.16  4851.2   39.08  4890.4    36.3  4908.7   36.49  4949.1   35.04
  4957.4   33.89    4963   34.63  4971.4   33.39  4979.8   29.64  4985.4   32.21
    4991   29.14  4993.8   29.14  4994.6   28.18  4995.1   27.68    5013   27.68
  5013.5   28.18  5024.7   31.81  5045.3    34.9    5053   39.28  5058.2   39.41
  5065.9   42.65  5086.5   44.66  5094.3   46.26  5098.1   46.42  5199.9   53.51
#Mann= 6 ,-1 , 0
  4658.4     .05       0  4729.2     .07       0  4908.7     .05       0
  4994.6     .05       0  5013.5     .05       0  5098.1     .07       0
Bank Sta=4994.6,5013.5
XS Rating Curve= 0 ,0
Exp/Cntr=0.3,0.1

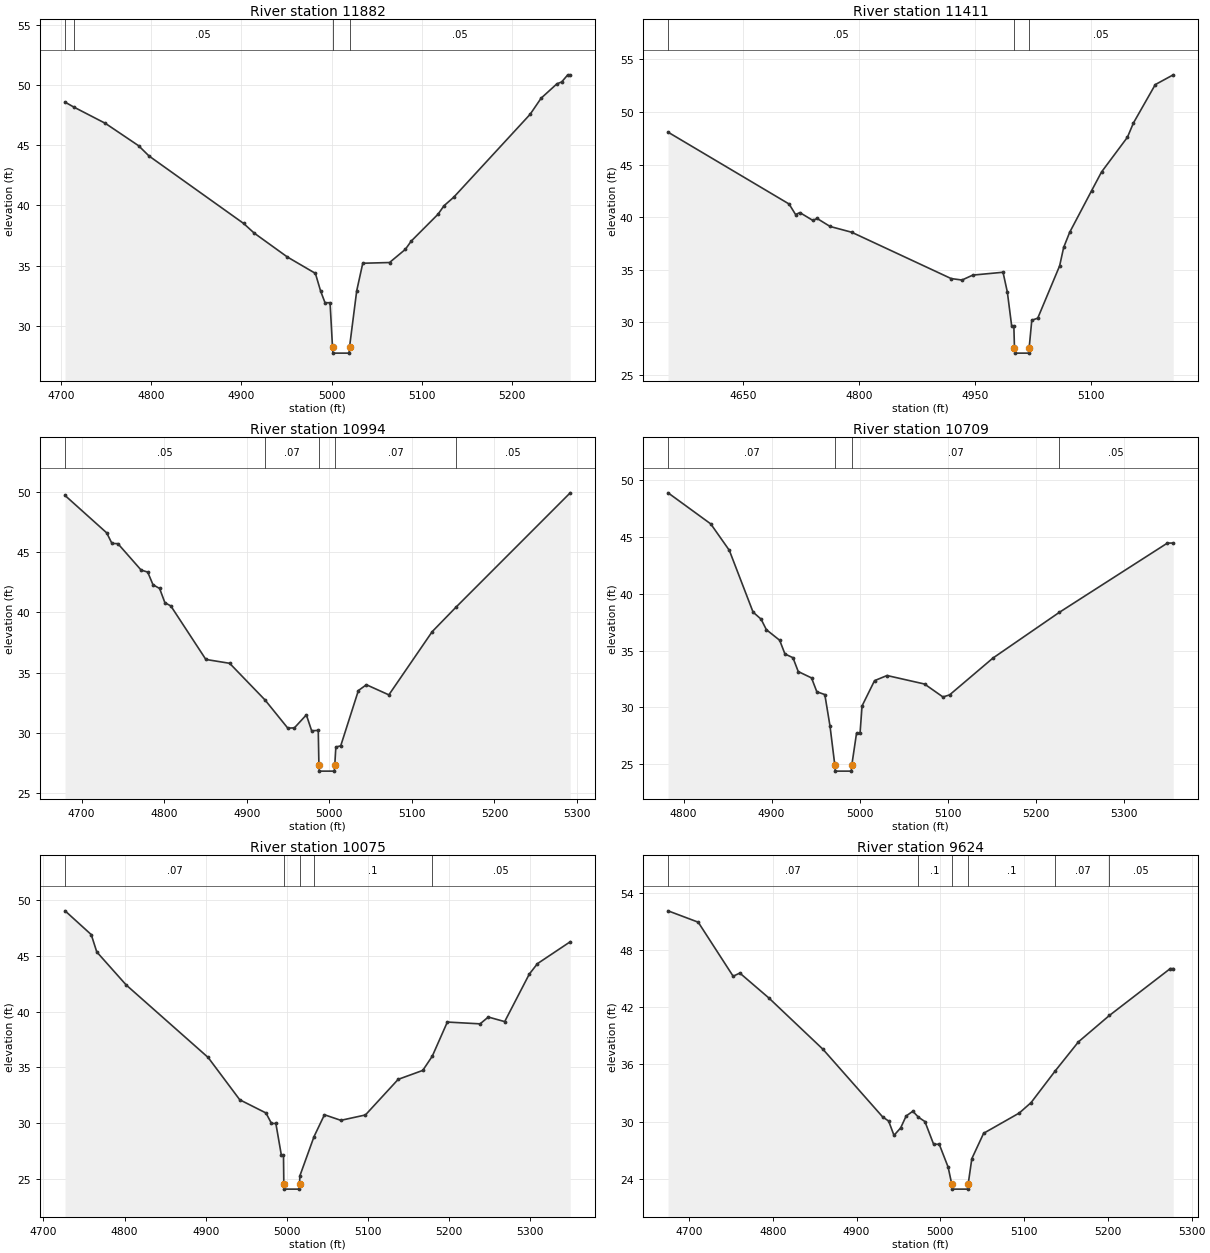
Type RM Length L Ch R = 1 ,11882   ,471,471,471
BEGIN DESCRIPTION:
DRY KUY CREEK 24.0
END DESCRIPTION:
XS GIS Cut Line= 3
      2618874.98     13394324.96        2618725.       13394075.
      2618474.96     13393974.99
#Sta/Elev= 30
  4704.2   48.59  4713.7   48.19  4748.9   46.83  4785.8   44.97  4797.5   44.11
  4902.4   38.51  4914.1   37.71    4951   35.72  4982.1   34.36  4987.9   32.89
  4992.8   31.92  4998.4   31.92  5001.1   28.23  5001.6   27.73  5019.5   27.73
    5020   28.23    5028   32.92  5034.7    35.2  5064.4   35.26  5081.9   36.35
  5088.6   37.05  5118.2   39.27  5124.9   39.98  5135.7   40.69  5220.5   47.58
  5232.7   48.92  5250.2   50.11  5255.5   50.27  5262.3   50.86    5265   50.86
#Mann= 4 ,-1 , 0
  4704.2     .07       0  4713.7     .05       0  5001.1     .05       0
    5020     .05       0
Bank Sta=5001.1,5020
XS Rating Curve= 0 ,0
Exp/Cntr=0.3,0.1

Type RM Length L Ch R = 1 ,11411   ,417,417,417
BEGIN DESCRIPTION:
DRY KUY CREEK 23.0
END DESCRIPTION:
XS GIS Cut Line= 3
      2619224.98     13394124.96        2619025.       13393725.
      2618975.01     13393525.02
#Sta/Elev= 30
  4552.8   48.08  4709.3   41.24  4717.7   40.24  4723.3   40.42    4740   39.68
  4745.6   39.86  4762.4    39.1  4790.3   38.55  4918.9   34.14  4932.9      34
  4946.9   34.47    4986   34.74  4991.6   32.85  4997.2   29.61    5000   29.61
  5000.8   27.54  5001.3   27.04  5019.3   27.04  5019.8   27.54  5023.2   30.17
  5030.9   30.37  5059.2   35.35  5064.4    37.1  5072.1   38.53  5100.5    42.5
  5113.4   44.29  5146.9    47.6  5154.6   48.95  5182.9   52.61  5206.1   53.54
#Mann= 3 ,-1 , 0
  4552.8     .05       0  5000.8     .05       0  5019.8     .05       0
Bank Sta=5000.8,5019.8
XS Rating Curve= 0 ,0
Exp/Cntr=0.3,0.1

Type RM Length L Ch R = 1 ,10994   ,285,285,285
BEGIN DESCRIPTION:
DRY KUY CREEK 22.0
END DESCRIPTION:
XS GIS Cut Line= 3
      2619625.01     13393925.01        2619375.       13393725.
      2619225.01     13393475.01
#Sta/Elev= 30
    4680    49.7  4730.4    46.6  4736.8   45.72    4744    45.7  4772.1   43.51
  4780.1   43.34  4786.5   42.29  4794.5   41.98  4800.9    40.8  4808.1   40.53
  4850.5   36.09  4879.3   35.77  4922.1   32.73  4949.7   30.39  4957.7   30.41
  4972.2   31.49  4978.6   30.17  4986.6    30.2  4987.4   27.32  4987.9   26.82
  5006.1   26.82  5006.6   27.32  5007.9   28.82  5013.8   28.92  5035.2   33.51
  5044.9   33.99  5072.1   33.15  5124.6    38.4  5153.4   40.43  5291.7   49.92
#Mann= 5 ,-1 , 0
    4680     .05       0  4922.1     .07       0  4987.4     .05       0
  5006.6     .07       0  5153.4     .05       0
Bank Sta=4987.4,5006.6
XS Rating Curve= 0 ,0
Exp/Cntr=0.3,0.1

Type RM Length L Ch R = 1 ,10709   ,634,634,634
BEGIN DESCRIPTION:
Mapping XS b1a1b651
END DESCRIPTION:
XS GIS Cut Line= 3
      2619805.58     13393749.91       2619623.3     13393630.13
      2619360.27     13393390.54
#Sta/Elev= 30
  4782.4   48.91  4830.9   46.17    4852   43.84    4879   38.39  4888.1   37.77
  4894.1   36.84  4909.2   35.91  4915.2    34.7  4924.3   34.37  4930.3   33.15
  4945.4   32.59  4951.4   31.37  4960.5   31.12  4966.4   28.34  4971.9   24.87
  4972.4   24.37  4990.6   24.37  4991.1   24.87  4996.5    27.7  5000.5    27.7
  5002.8   30.12    5017   32.35  5031.2    32.8  5073.8   32.05  5094.7   30.91
  5102.2   31.09  5151.5   34.34  5226.9   38.37  5349.7   44.48  5356.3   44.48
#Mann= 4 ,-1 , 0
  4782.4     .07       0  4971.9     .05       0  4991.1     .07       0
  5226.9     .05       0
Bank Sta=4971.9,4991.1
XS Rating Curve= 0 ,0
Exp/Cntr=0.3,0.1

Type RM Length L Ch R = 1 ,10075   ,451,451,451
BEGIN DESCRIPTION:
DRY KUY CREEK 20.0
END DESCRIPTION:
XS GIS Cut Line= 3
      2620075.02     13393225.01        2619825.       13393125.
      2619475.04     13393075.01
#Sta/Elev= 30
  4726.6   49.02  4758.9   46.89  4765.7   45.34    4802   42.38    4903   35.89
    4942    32.1  4974.3   30.92  4981.1   29.98  4986.5   29.98  4993.2   27.17
  4995.9   27.17  4996.3    24.6  4996.8    24.1  5015.2    24.1  5015.7    24.6
  5016.1   25.29  5033.6   28.81  5046.4   30.76  5066.6   30.26  5096.9   30.74
  5137.3   33.93  5167.6   34.73  5179.3      36  5197.9   39.06  5238.3    38.9
  5248.4   39.51  5268.6    39.1  5298.9   43.35    5309   44.29  5349.4   46.25
#Mann= 5 ,-1 , 0
  4726.6     .07       0  4996.3     .05       0  5015.7     .07       0
  5033.6      .1       0  5179.3     .05       0
Bank Sta=4996.3,5015.7
XS Rating Curve= 0 ,0
Exp/Cntr=0.3,0.1

Type RM Length L Ch R = 1 ,9624    ,453,453,453
BEGIN DESCRIPTION:
DRY KUY CREEK 19.0
END DESCRIPTION:
XS GIS Cut Line= 3
      2620275.01     13392975.01        2620025.       13392775.
      2619825.01     13392575.01
#Sta/Elev= 30
    4675   52.09    4711    50.9  4752.7   45.24  4760.7   45.57  4795.1   42.98
  4859.9   37.59  4931.1   30.51  4938.3   30.07  4944.7   28.57  4952.7   29.36
  4959.2    30.6  4967.2    31.1  4973.9   30.47  4981.6   30.02    4992   27.64
  4998.7   27.64  5009.3   25.25  5013.7   23.44  5014.2   22.94  5032.7   22.94
  5033.2   23.44  5037.6   26.13  5051.7   28.79  5094.2   30.91  5108.3      32
  5137.3   35.34  5164.9   38.37  5201.8   41.13  5274.5   46.04    5278   46.04
#Mann= 6 ,-1 , 0
    4675     .07       0  4973.9      .1       0  5013.7     .05       0
  5033.2      .1       0  5137.3     .07       0  5201.8     .05       0
Bank Sta=5013.7,5033.2
XS Rating Curve= 0 ,0
Exp/Cntr=0.3,0.1

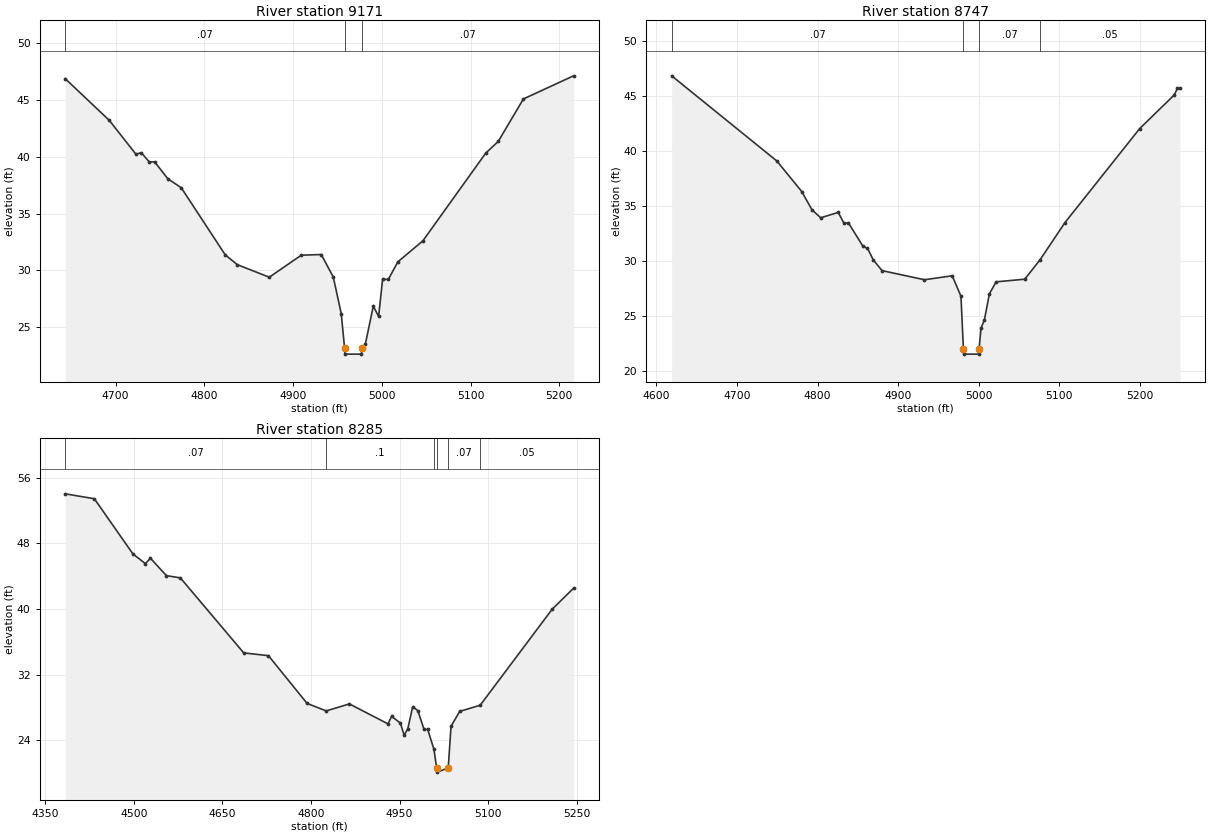
Type RM Length L Ch R = 1 ,9171    ,424,424,424
BEGIN DESCRIPTION:
DRY KUY CREEK 18.0
END DESCRIPTION:
XS GIS Cut Line= 3
      2620425.02     13392725.04        2620225.       13392425.
      2620075.02     13392275.02
#Sta/Elev= 30
  4643.3   46.89  4692.9   43.22    4723   40.23    4729   40.37    4738   39.55
    4744   39.56    4759   38.06    4774   37.28  4823.6   31.36  4837.1    30.5
  4873.2   29.39  4909.3   31.33  4931.8   31.39  4945.3   29.41  4954.3   26.18
  4958.1   23.11  4958.6   22.61  4977.1   22.61  4977.6   23.11  4981.4   23.48
  4990.4   26.83  4996.4   25.94  5000.9    29.2  5007.4    29.2    5018   30.74
  5046.3    32.6    5117   40.32  5131.2   41.36  5159.5    45.1    5216   47.14
#Mann= 3 ,-1 , 0
  4643.3     .07       0  4958.1     .05       0  4977.6     .07       0
Bank Sta=4958.1,4977.6
XS Rating Curve= 0 ,0
Exp/Cntr=0.3,0.1

Type RM Length L Ch R = 1 ,8747    ,462,462,462
BEGIN DESCRIPTION:
DRY KUY CREEK 17.0
END DESCRIPTION:
XS GIS Cut Line= 3
      2620724.99     13392574.98        2620575.       13392225.
      2620424.98     13392024.97
#Sta/Elev= 30
    4619   46.84  4749.5   39.09  4780.4   36.31  4793.1   34.65  4803.9   33.92
  4825.7   34.41  4832.9   33.41  4838.4   33.45  4856.5   31.31    4862   31.15
  4869.2   30.08  4880.1   29.11  4932.7   28.28  4967.1   28.64    4978   26.78
    4981   22.01  4981.5   21.51    5000   21.51  5000.5   22.01  5002.9   23.87
  5007.1   24.65  5013.3      27  5021.6   28.09  5057.1   28.33  5076.1   30.09
  5107.1   33.49  5199.8   42.04  5242.5   45.09  5246.6   45.69  5249.8   45.69
#Mann= 4 ,-1 , 0
    4619     .07       0    4981     .05       0  5000.5     .07       0
  5076.1     .05       0
Bank Sta=4981,5000.5
XS Rating Curve= 0 ,0
Exp/Cntr=0.3,0.1

Type RM Length L Ch R = 1 ,8285    ,458,458,458
BEGIN DESCRIPTION:
DRY KUY CREEK 16.0
END DESCRIPTION:
XS GIS Cut Line= 3
      2621275.01     13392475.01        2620925.       13391975.
      2620725.03     13391825.02
#Sta/Elev= 30
  4384.1   54.05  4433.4   53.45  4498.8   46.72  4519.7   45.55  4528.4    46.2
  4555.4   44.08    4579   43.81  4686.2   34.67  4728.1   34.33  4793.5   28.51
  4825.9    27.6    4865   28.45  4930.4   26.02  4936.5   26.94  4951.3   26.12
  4957.8   24.64  4963.9   25.42  4972.2   28.11  4980.9   27.63  4991.4   25.34
  4997.6   25.34  5008.1   22.93  5012.8   20.64  5013.3   20.14  5032.3   20.64
  5037.1   25.72  5051.7   27.54  5086.4   28.29    5208   39.97  5244.4   42.55
#Mann= 6 ,-1 , 0
  4384.1     .07       0  4825.9      .1       0  5008.1     .07       0
  5012.8     .05       0  5032.3     .07       0  5086.4     .05       0
Bank Sta=5012.8,5032.3
XS Rating Curve= 0 ,0
Exp/Cntr=0.3,0.1