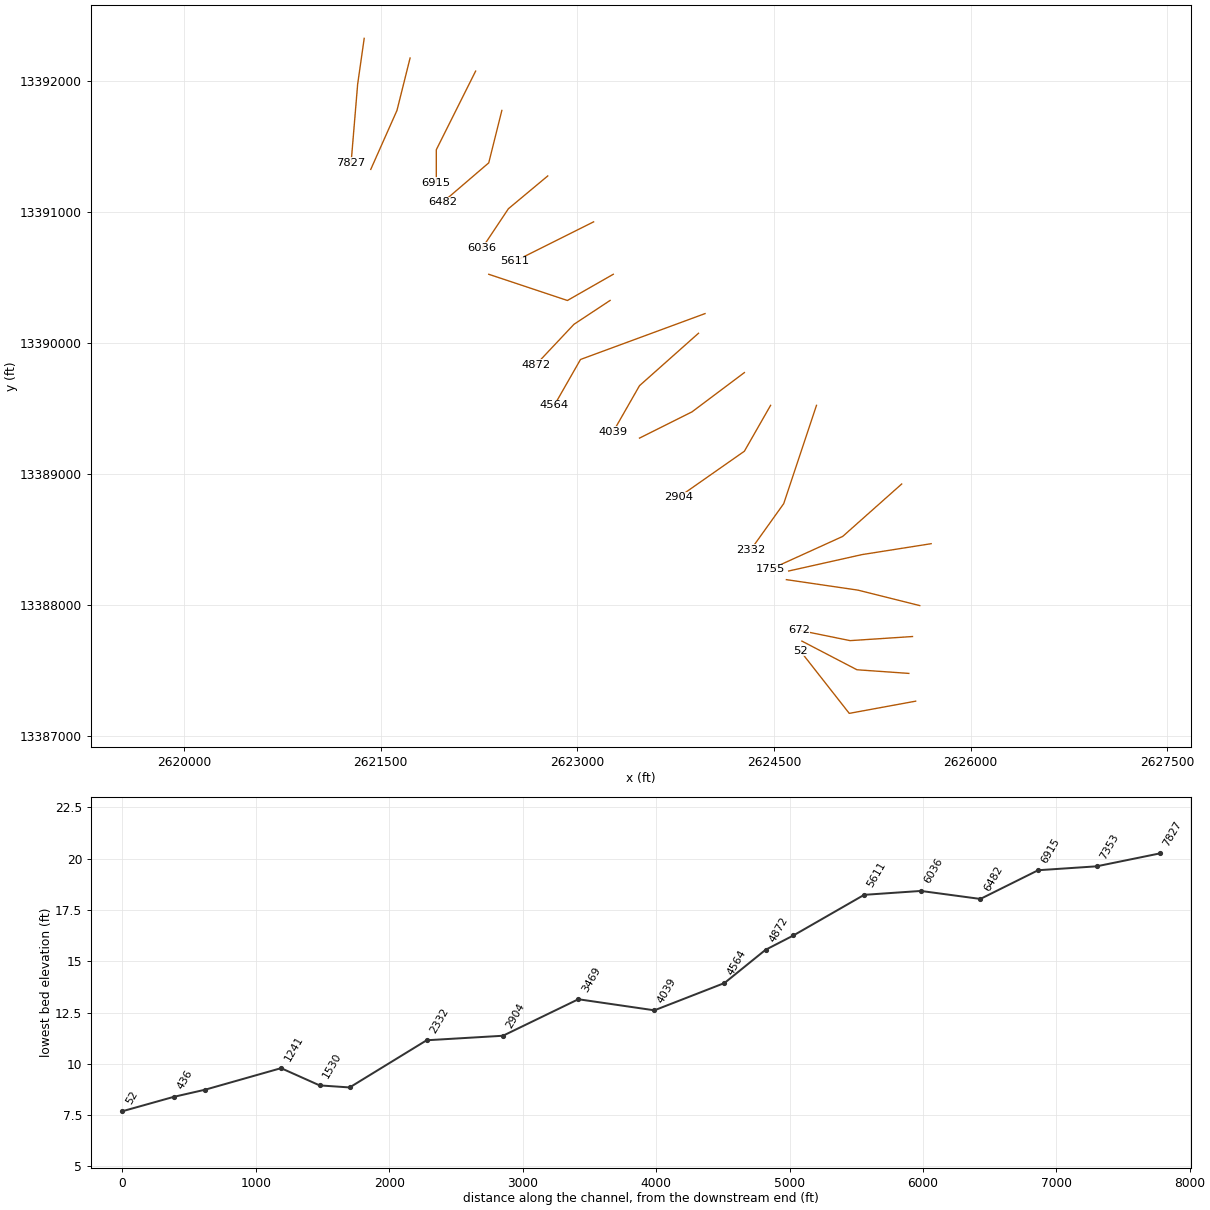
HEC-RAS study DRY KUY CREEK.prj: DRY KUY CREEK Base Level Engineering

--- DRY KUY CREEK.g01 (geometry) --- (continued)

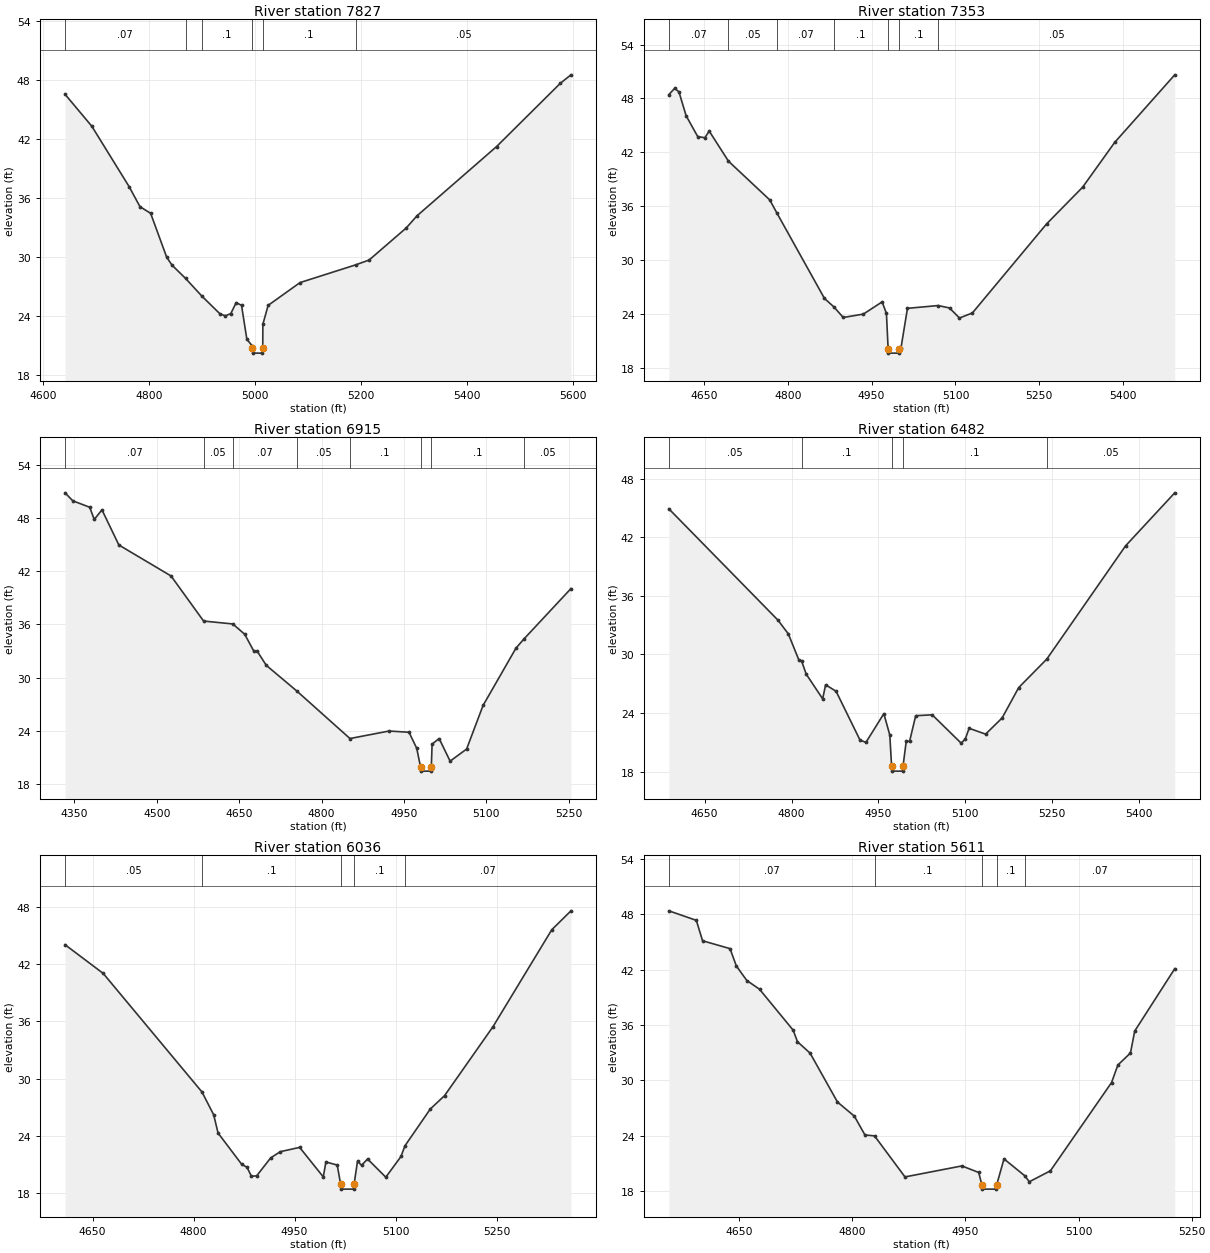
Type RM Length L Ch R = 1 ,7827    ,474,474,474
BEGIN DESCRIPTION:
DRY KUY CREEK 15.0
END DESCRIPTION:
XS GIS Cut Line= 3
        2621375.     13392324.98        2621325.       13391975.
        2621275.     13391375.01
#Sta/Elev= 30
    4641   46.53  4691.5   43.29  4762.2   37.14  4782.4   35.13  4802.6   34.45
  4832.9      30    4843   29.19  4868.5   27.85  4898.8   26.08  4933.9   24.23
    4944   24.05  4954.1   24.28  4964.2   25.39  4974.3   25.11  4984.4   21.66
  4994.5      21  4994.7   20.76  4995.2   20.26  5013.9   20.26  5014.4   20.76
  5014.6   23.19  5024.6   25.11  5084.8   27.42  5189.9   29.22  5215.3   29.71
  5285.5   32.97  5305.6   34.19  5456.1   41.23  5576.5   47.65  5596.6   48.51
#Mann= 6 ,-1 , 0
    4641     .07       0  4868.5    .035       0  4898.8      .1       0
  4994.7    .035       0  5014.4      .1       0  5189.9     .05       0
Bank Sta=4994.7,5014.4
XS Rating Curve= 0 ,0
Exp/Cntr=0.3,0.1

Type RM Length L Ch R = 1 ,7353    ,438,438,438
BEGIN DESCRIPTION:
DRY KUY CREEK 14.0
END DESCRIPTION:
XS GIS Cut Line= 3
        2621725.     13392174.98        2621625.       13391775.
      2621425.01     13391325.03
#Sta/Elev= 30
  4587.4   48.43  4597.7   49.12  4605.4   48.74  4618.3   46.07  4638.9   43.76
  4651.8   43.62  4659.5   44.37    4694   41.01  4767.8    36.7  4780.3   35.27
  4865.7   25.72  4882.7   24.77  4899.2    23.6  4935.3   23.98  4968.8   25.34
  4976.5   24.05  4979.5   20.13    4980   19.63  4998.7   19.63  4999.2   20.13
  5002.4   20.16  5014.1   24.62    5069   24.93  5089.3   24.66  5107.1   23.54
  5130.3   24.11    5263   34.03  5327.3   38.11  5384.8   43.11  5492.1   50.63
#Mann= 7 ,-1 , 0
  4587.4     .07       0    4694     .05       0  4780.3     .07       0
  4882.7      .1       0  4979.5     .05       0  4999.2      .1       0
    5069     .05       0
Bank Sta=4979.5,4999.2
XS Rating Curve= 0 ,0
Exp/Cntr=0.3,0.1

Type RM Length L Ch R = 1 ,6915    ,433,433,433
BEGIN DESCRIPTION:
DRY KUY CREEK 13.0
END DESCRIPTION:
XS GIS Cut Line= 3
      2622225.02     13392075.03        2621925.       13391475.
        2621925.     13391224.95
#Sta/Elev= 30
    4333   50.87    4347   49.97  4377.8   49.24  4386.1   47.86  4400.1   48.95
  4430.9   44.98  4525.9   41.48  4585.1   36.39  4638.4   36.06  4660.1   34.89
  4676.8   32.96  4682.4   33.02  4699.2   31.39  4754.6    28.5  4851.6   23.12
  4922.8   23.97  4959.1   23.83  4973.1   22.02    4980   19.94  4980.5   19.44
  4999.2   19.44  4999.7   19.94  5001.1   22.49  5013.9   23.12  5033.9   20.57
  5063.9   21.93  5093.9   26.86  5153.9   33.34  5168.7   34.39  5253.9   40.06
#Mann= 8 ,-1 , 0
    4333     .07       0  4585.1     .05       0  4638.4     .07       0
  4754.6     .05       0  4851.6      .1       0    4980     .05       0
  4999.7      .1       0  5168.7     .05       0
Bank Sta=4980,4999.7
XS Rating Curve= 0 ,0
Exp/Cntr=0.3,0.1

Type RM Length L Ch R = 1 ,6482    ,446,446,446
BEGIN DESCRIPTION:
DRY KUY CREEK 12.0
END DESCRIPTION:
XS GIS Cut Line= 3
      2622425.01     13391775.04        2622325.       13391375.
      2621975.02     13391075.02
#Sta/Elev= 30
  4588.2   44.92  4776.4   33.52  4794.4   32.11  4812.4   29.46  4817.3   29.33
  4825.3   27.98  4853.7   25.45  4858.8   26.89  4876.9   26.22  4918.1   21.23
  4928.4   20.98  4959.3   23.93  4969.6   21.74  4972.7   18.54  4973.2   18.04
  4991.9   18.04  4992.4   18.54    4998    21.1  5003.8    21.1  5014.3   23.72
  5042.8   23.81  5092.7   20.91  5099.9   21.33  5106.5   22.43    5135   21.83
  5163.5   23.49  5192.1    26.6  5240.6   29.52  5376.5   41.12  5461.5   46.56
#Mann= 5 ,-1 , 0
  4588.2     .05       0  4817.3      .1       0  4972.7     .05       0
  4992.4      .1       0  5240.6     .05       0
Bank Sta=4972.7,4992.4
XS Rating Curve= 0 ,0
Exp/Cntr=0.3,0.1

Type RM Length L Ch R = 1 ,6036    ,425,425,425
BEGIN DESCRIPTION:
DRY KUY CREEK 11.0
END DESCRIPTION:
XS GIS Cut Line= 3
      2622774.98     13391274.98        2622475.       13391025.
      2622275.02     13390725.03
#Sta/Elev= 30
  4609.3   44.01  4665.9   41.01  4812.5    28.6  4829.9   26.21  4836.4    24.3
  4871.6   21.02  4879.4   20.72  4885.9   19.78  4893.7   19.82  4914.5    21.7
  4928.8   22.35  4957.5    22.8  4992.6   19.71  4996.5   21.27  5013.3   20.95
  5018.4   18.93  5018.9   18.43  5037.8   18.43  5038.3   18.93  5043.4   21.35
  5049.4   20.93  5058.4   21.58  5085.4   19.68    5108   21.85  5113.8   22.96
  5151.5   26.82  5172.6   28.21  5244.7   35.45  5331.8   45.58  5360.3   47.56
#Mann= 5 ,-1 , 0
  4609.3     .05       0  4812.5      .1       0  5018.4     .05       0
  5038.3      .1       0  5113.8     .07       0
Bank Sta=5018.4,5038.3
XS Rating Curve= 0 ,0
Exp/Cntr=0.3,0.1

Type RM Length L Ch R = 1 ,5611    ,530,530,530
BEGIN DESCRIPTION:
DRY KUY CREEK 10.0
END DESCRIPTION:
XS GIS Cut Line= 3
      2623125.02     13390925.01        2622725.       13390725.
      2622525.04     13390625.02
#Sta/Elev= 30
  4556.7   48.35  4593.1   47.32  4601.4   45.11  4637.8   44.26  4646.2   42.38
  4660.1   40.81  4676.9   39.87  4721.6   35.43  4727.2   34.19    4744   32.95
  4780.3   27.66  4802.7   26.13  4816.7    24.1  4829.4      24  4869.8   19.56
  4945.2   20.75  4967.6   20.04  4971.6   18.74  4972.1   18.24    4991   18.24
  4991.5   18.74  5001.1   21.51  5028.4    19.7  5034.7   19.04  5062.6   20.22
  5143.7   29.77  5152.1   31.67  5168.8   32.97  5174.4   35.34  5227.5   42.09
#Mann= 5 ,-1 , 0
  4556.7     .07       0  4829.4      .1       0  4971.6     .05       0
  4991.5      .1       0  5028.4     .07       0
Bank Sta=4971.6,4991.5
XS Rating Curve= 0 ,0
Exp/Cntr=0.3,0.1

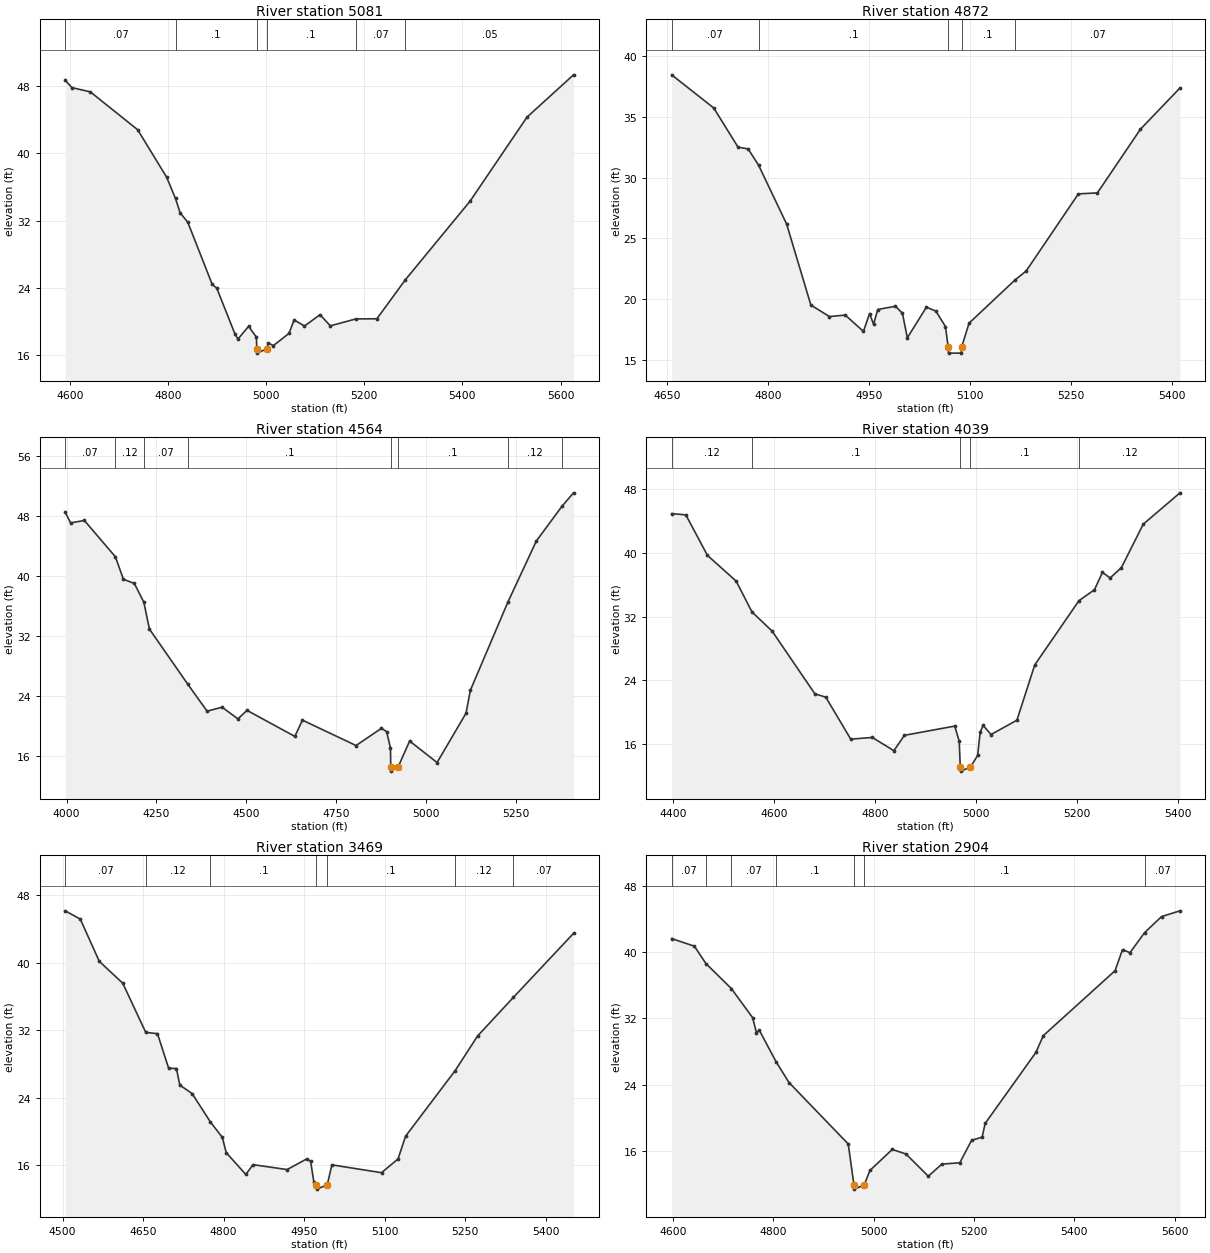
Type RM Length L Ch R = 1 ,5081    ,209,209,209
BEGIN DESCRIPTION:
DRY KUY CREEK 9.0
END DESCRIPTION:
XS GIS Cut Line= 3
      2623275.02     13390525.01        2622925.       13390325.
      2622324.99       13390525.
#Sta/Elev= 30
  4590.8   48.65  4604.5   47.78  4641.9   47.28  4738.4   42.78  4797.4   37.15
  4815.5   34.62  4824.8   32.93  4840.6   31.79  4890.3   24.42  4899.6   23.97
  4936.3   18.58  4942.8   17.93  4964.4   19.44  4980.3   18.16  4981.1   16.76
  4981.6   16.26  5001.1   16.76  5004.5   17.45    5015   17.16  5046.6    18.6
  5057.2    20.2  5078.3   19.48  5109.9   20.82    5131    19.5  5182.9   20.32
  5225.8   20.34  5283.8   24.97  5415.6    34.3  5531.5   44.27  5626.4    49.3
#Mann= 6 ,-1 , 0
  4590.8     .07       0  4815.5      .1       0  4981.1     .05       0
  5001.1      .1       0  5182.9     .07       0  5283.8     .05       0
Bank Sta=4981.1,5001.1
XS Rating Curve= 0 ,0
Exp/Cntr=0.3,0.1

Type RM Length L Ch R = 1 ,4872    ,308,308,308
BEGIN DESCRIPTION:
Mapping XS 7e76ce53
END DESCRIPTION:
XS GIS Cut Line= 3
      2623250.87     13390325.42      2622974.86     13390143.15
      2622683.21     13389833.27
#Sta/Elev= 30
  4656.3   38.47  4718.9   35.74    4755   32.52  4770.1   32.37  4785.7   31.02
  4827.3   26.19  4863.4   19.52    4891   18.57  4914.6   18.69  4941.6   17.35
  4950.7   18.81  4956.7   17.94  4962.9   19.15  4989.2   19.42  4999.6   18.85
  5006.9   16.82  5035.3   19.34  5049.4   19.02  5063.6   17.75  5067.7   16.06
  5068.2   15.56  5087.2   15.56  5087.7   16.06  5098.8   18.03  5166.7   21.56
  5183.7   22.32  5261.4   28.67  5289.7   28.75  5353.7   33.99  5412.6   37.39
#Mann= 5 ,-1 , 0
  4656.3     .07       0  4785.7      .1       0  5067.7     .05       0
  5087.7      .1       0  5166.7     .07       0
Bank Sta=5067.7,5087.7
XS Rating Curve= 0 ,0
Exp/Cntr=0.3,0.1

Type RM Length L Ch R = 1 ,4564    ,525,525,525
BEGIN DESCRIPTION:
DRY KUY CREEK 8.0
END DESCRIPTION:
XS GIS Cut Line= 3
        2623975.       13390225.        2623025.       13389875.
      2622825.02     13389525.03
#Sta/Elev= 30
  3995.9   48.51  4011.1    47.1  4049.2   47.43  4135.6   42.58    4158   39.57
  4188.5   39.01  4214.9    36.5  4230.4   32.92  4337.6   25.53    4391   21.95
  4432.8   22.48    4477   20.92  4502.1   22.06  4635.3   18.58  4656.6   20.75
  4805.8   17.36  4876.6   19.66  4891.1   19.21  4901.7   16.99  4902.4   14.44
  4902.9   13.94  4922.4   14.44    4955   17.96  5031.4   15.09    5112   21.67
  5124.2   24.75  5228.4    36.5  5307.8   44.68    5379   49.31  5411.4   51.12
#Mann= 8 ,-1 , 0
  3995.9     .07       0  4135.6     .12       0  4214.9     .07       0
  4337.6      .1       0  4902.4     .05       0  4922.4      .1       0
  5228.4     .12       0    5379     .07       0
Bank Sta=4902.4,4922.4
XS Rating Curve= 0 ,0
Exp/Cntr=0.3,0.1

Type RM Length L Ch R = 1 ,4039    ,570,570,570
BEGIN DESCRIPTION:
DRY KUY CREEK 7.0
END DESCRIPTION:
XS GIS Cut Line= 3
        2623925.       13390075.        2623475.       13389675.
      2623274.99     13389324.99
#Sta/Elev= 30
  4397.9   44.97  4425.9   44.81  4468.6   39.72  4525.4   36.49  4556.7   32.61
  4596.5   30.21    4681   22.33  4702.7    21.9    4752   16.63  4794.7   16.84
  4837.3   15.18  4858.2   17.11  4957.7   18.27  4966.5   16.36  4968.6   13.11
  4969.1   12.61  4988.8   13.11  5002.9   14.58  5007.9   17.47  5013.7   18.36
  5029.5   17.21  5080.6   19.01  5115.9   25.96  5203.3   34.03  5233.9    35.4
  5249.8   37.59  5264.9   36.88  5287.2   38.18  5330.4   43.64  5403.1   47.58
#Mann= 5 ,-1 , 0
  4397.9     .12       0  4556.7      .1       0  4968.6     .05       0
  4988.8      .1       0  5203.3     .12       0
Bank Sta=4968.6,4988.8
XS Rating Curve= 0 ,0
Exp/Cntr=0.3,0.1

Type RM Length L Ch R = 1 ,3469    ,565,565,565
BEGIN DESCRIPTION:
DRY KUY CREEK 6.0
END DESCRIPTION:
XS GIS Cut Line= 3
        2624275.       13389775.        2623875.       13389475.
      2623475.01     13389275.01
#Sta/Elev= 30
    4505   46.15  4533.1   45.17  4568.5   40.16  4612.3   37.56  4655.1   31.73
  4676.9   31.59  4697.7   27.49  4712.3   27.45  4718.5   25.49  4741.5   24.48
  4775.4   21.13  4797.7   19.29    4805   17.48  4841.5   14.89    4855   16.05
  4918.5   15.47    4955   16.73  4962.3   16.44  4968.5   13.94    4973   13.65
  4973.5   13.15  4993.3   13.65  5001.9   16.03  5094.4    15.1  5125.2   16.73
  5139.2   19.42  5231.6    27.2  5273.3    31.3    5340   35.88  5452.2   43.48
#Mann= 7 ,-1 , 0
    4505     .07       0  4655.1     .12       0  4775.4      .1       0
    4973     .05       0  4993.3      .1       0  5231.6     .12       0
    5340     .07       0
Bank Sta=4973,4993.3
XS Rating Curve= 0 ,0
Exp/Cntr=0.3,0.1

Type RM Length L Ch R = 1 ,2904    ,572,572,572
BEGIN DESCRIPTION:
DRY KUY CREEK 5.0
END DESCRIPTION:
XS GIS Cut Line= 3
      2624474.99     13389524.98        2624275.       13389175.
      2623775.01     13388825.01
#Sta/Elev= 30
  4597.1   41.62  4642.4    40.7  4665.3   38.61    4716   35.59  4758.3   32.09
  4766.2   30.26    4772   30.54  4805.4   26.73    4831   24.24  4949.1   16.82
  4960.5   11.87    4961   11.37  4980.8   11.87  4992.3   13.62  5036.8   16.16
  5064.3   15.61  5108.7   12.93  5135.8   14.39  5171.5   14.55  5195.1   17.27
    5216   17.64  5222.1   19.31  5323.2   27.87    5338    29.9    5481   37.74
  5495.9   40.29  5510.7   39.91  5540.1   42.35  5573.9   44.28  5610.5   44.97
#Mann= 7 ,-1 , 0
  4597.1     .07       0  4665.3     .12       0    4716     .07       0
  4805.4      .1       0  4960.5     .05       0  4980.8      .1       0
  5540.1     .07       0
Bank Sta=4960.5,4980.8
XS Rating Curve= 0 ,0
Exp/Cntr=0.3,0.1

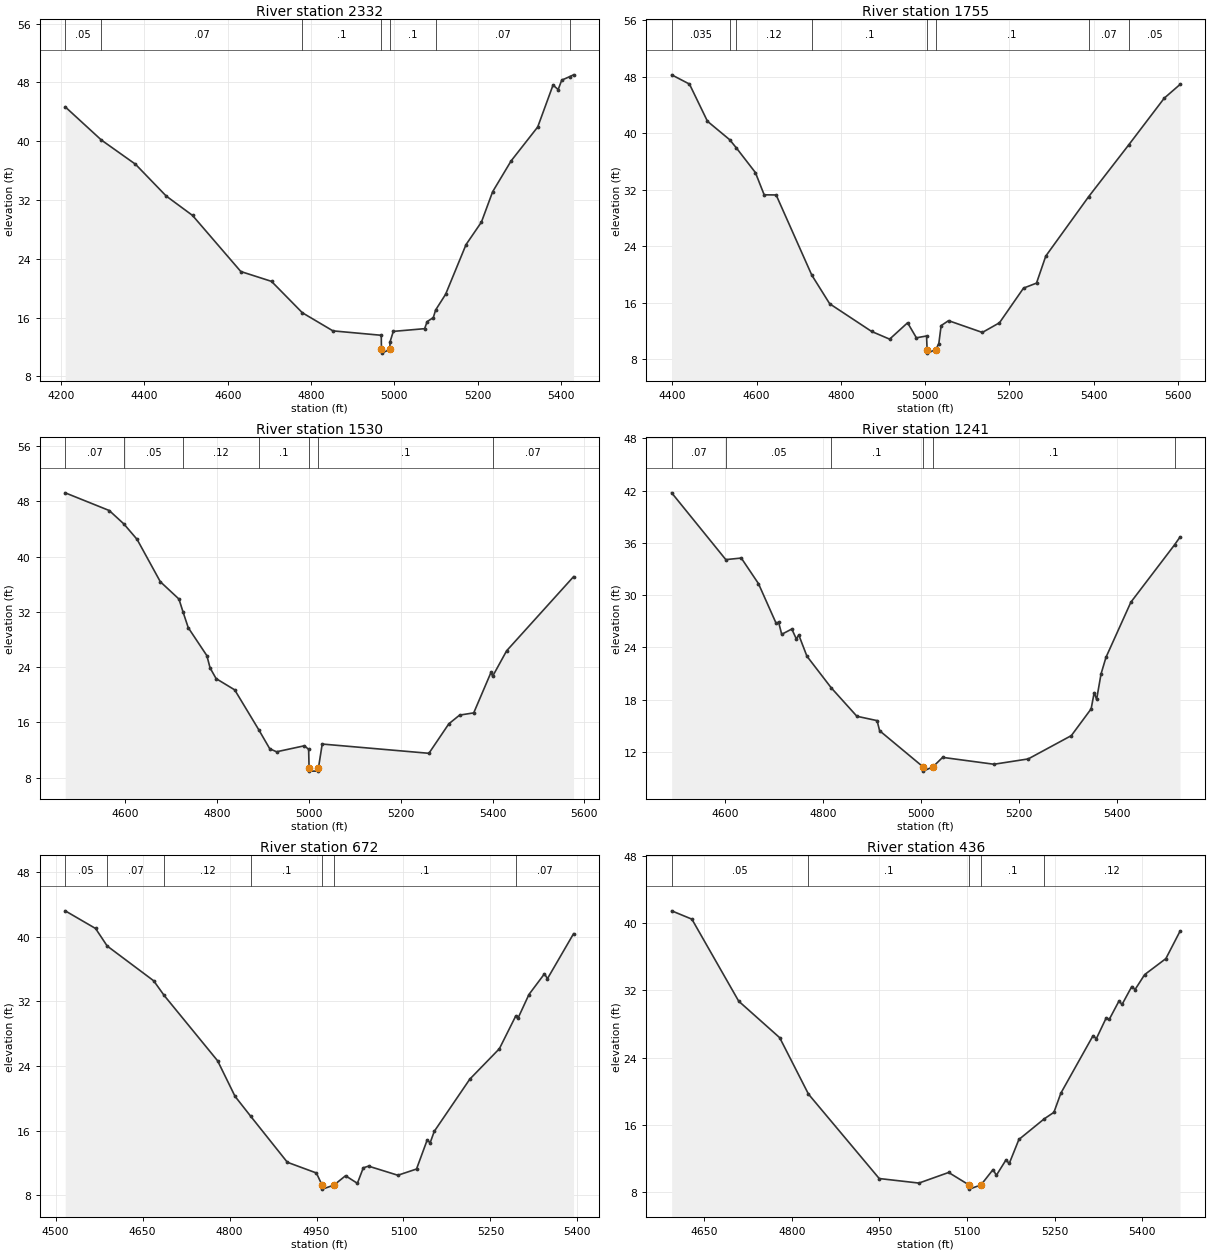
Type RM Length L Ch R = 1 ,2332    ,577,577,577
BEGIN DESCRIPTION:
DRY KUY CREEK 4.0
END DESCRIPTION:
XS GIS Cut Line= 3
        2624825.     13389525.01        2624575.       13388775.
        2624325.       13388425.
#Sta/Elev= 30
  4209.7   44.68  4296.6   40.16  4378.4   36.87  4452.2   32.54  4515.4    29.9
  4631.4   22.26  4705.1   20.92  4779.1   16.65  4852.7   14.18  4968.7   13.58
  4969.1   11.65  4969.6   11.15  4989.4   11.65  4989.7   12.67  4997.6   14.11
  5072.8   14.48  5078.9   15.44  5093.7   15.99  5099.1   17.01  5123.2   19.16
  5172.3   25.93  5209.2   28.99  5236.2   33.13  5280.5   37.32  5344.4   41.94
  5381.2   47.65  5393.5   47.03  5402.1   48.32    5421   48.79  5430.4   49.04
#Mann= 7 ,-1 , 0
  4209.7     .05       0  4296.6     .07       0  4779.1      .1       0
  4969.1     .05       0  4989.4      .1       0  5099.1     .07       0
    5421     .05       0
Bank Sta=4969.1,4989.4
XS Rating Curve= 0 ,0
Exp/Cntr=0.3,0.1

Type RM Length L Ch R = 1 ,1755    ,225,225,225
BEGIN DESCRIPTION:
DRY KUY CREEK 3.0
END DESCRIPTION:
XS GIS Cut Line= 3
      2625474.99     13388924.99        2625025.       13388525.
      2624475.02     13388275.01
#Sta/Elev= 30
  4398.6   48.28  4440.8   46.97  4483.5    41.7  4536.2   39.09  4552.3   37.91
  4597.2   34.44  4618.1   31.28  4646.5   31.26  4731.1    19.9  4773.6   15.84
  4873.1   11.92  4915.8   10.83  4958.4   13.15  4979.3   11.02  5003.4   11.28
  5004.7    9.35  5005.2    8.85  5025.2    9.35  5032.5    10.2    5038   12.75
  5055.6   13.45  5135.8   11.78  5176.4   13.15  5233.5   18.06  5264.3   18.77
  5286.3    22.6  5387.7   30.99  5483.7    38.4  5567.5   44.98  5604.8   46.91
#Mann= 8 ,-1 , 0
  4398.6    .035       0  4536.2     .05       0  4552.3     .12       0
  4731.1      .1       0  5004.7     .05       0  5025.2      .1       0
  5387.7     .07       0  5483.7     .05       0
Bank Sta=5004.7,5025.2
XS Rating Curve= 0 ,0
Exp/Cntr=0.3,0.1

Type RM Length L Ch R = 1 ,1530    ,289,289,289
BEGIN DESCRIPTION:
Mapping XS 38e7b7f9
END DESCRIPTION:
XS GIS Cut Line= 3
       2625699.7     13388469.54      2625171.91     13388386.21
      2624612.84      13388261.2
#Sta/Elev= 30
  4469.3   49.23  4565.2   46.67    4597   44.73  4625.9   42.49  4676.5   36.36
    4717   33.86    4726   31.98  4737.3   29.71  4777.8   25.67  4784.9   23.88
    4798   22.34  4838.5   20.71  4890.7   14.96  4914.8   12.19  4929.6   11.75
  4990.4   12.62  4999.5    12.1  5000.5    9.45    5001    8.95  5020.5    8.95
    5021    9.45  5029.1   12.87  5261.5   11.53  5304.9    15.8  5328.4   17.06
  5359.1   17.38  5396.8   23.25  5400.3   22.68  5430.8   26.37  5576.5   37.09
#Mann= 7 ,-1 , 0
  4469.3     .07       0    4597     .05       0    4726     .12       0
  4890.7      .1       0  5000.5     .05       0    5021      .1       0
  5400.3     .07       0
Bank Sta=5000.5,5021
XS Rating Curve= 0 ,0
Exp/Cntr=0.3,0.1

Type RM Length L Ch R = 1 ,1241    ,569,569,569
BEGIN DESCRIPTION:
Mapping XS 6207eab7
END DESCRIPTION:
XS GIS Cut Line= 3
      2625612.87     13387997.32      2625140.66     13388115.38
      2624595.53     13388195.24
#Sta/Elev= 30
  4491.6   41.75  4602.1   34.08  4633.7   34.26  4668.7   31.33  4704.8   26.77
  4709.9    26.9  4716.2    25.5  4736.8   26.11    4746   24.98  4751.1   25.42
  4767.7   22.99  4817.3   19.36  4869.7   16.09  4910.9   15.59  4916.1   14.43
  5004.6   10.29  5005.1    9.79  5025.1   10.29  5044.7   11.37  5149.5   10.58
  5219.4   11.19  5307.5   13.87  5347.9   16.94  5354.1    18.8  5359.1   18.03
  5368.1   20.95  5378.2   22.86    5429   29.19  5518.2   35.78  5529.3   36.67
#Mann= 6 ,-1 , 0
  4491.6     .07       0  4602.1     .05       0  4817.3      .1       0
  5004.6     .05       0  5025.1      .1       0  5518.2     .07       0
Bank Sta=5004.6,5025.1
XS Rating Curve= 0 ,0
Exp/Cntr=0.3,0.1

Type RM Length L Ch R = 1 ,672     ,236,236,236
BEGIN DESCRIPTION:
Mapping XS 241f4b17
END DESCRIPTION:
XS GIS Cut Line= 3
      2625557.31     13387761.21      2625081.63     13387729.96
      2624689.67     13387809.74
#Sta/Elev= 30
  4516.6   43.23    4569   41.04    4589   38.87  4669.2   34.56  4687.2   32.75
  4779.5   24.64  4809.5   20.24  4836.4   17.78  4899.7   12.07  4949.8   10.74
  4959.6    9.24  4960.1    8.74  4980.1    9.24  5000.1    10.4  5020.5    9.46
  5030.7   11.38  5039.7   11.59  5090.3   10.46  5122.5   11.23  5140.9   14.83
    5146   14.48  5153.1    15.9  5214.4   22.37  5265.4   26.14  5293.5   30.18
  5297.7   29.95  5316.4   32.86  5343.2   35.43  5348.3   34.82  5393.3   40.39
#Mann= 7 ,-1 , 0
  4516.6     .05       0    4589     .07       0  4687.2     .12       0
  4836.4      .1       0  4959.6     .05       0  4980.1      .1       0
  5293.5     .07       0
Bank Sta=4959.6,4980.1
XS Rating Curve= 0 ,0
Exp/Cntr=0.3,0.1

Type RM Length L Ch R = 1 ,436     ,384,384,384
BEGIN DESCRIPTION:
Mapping XS 71e89fa6
END DESCRIPTION:
XS GIS Cut Line= 3
      2625529.53     13387479.96      2625133.72     13387507.74
      2624713.54      13387726.5
#Sta/Elev= 30
  4594.2   41.47  4628.8   40.48    4709   30.73  4779.2   26.39  4828.5   19.68
  4949.6    9.65  5017.6    9.11  5068.5   10.37  5103.3    8.89  5103.8    8.39
  5123.9    8.89  5144.6   10.72  5150.2   10.03  5166.7   11.86  5172.3   11.44
  5188.8   14.29  5232.3   16.75  5248.8   17.52  5260.7    19.8  5315.8   26.63
  5321.4   26.27  5337.9   28.68  5343.5   28.56    5360   30.72  5365.6   30.36
  5382.1   32.47  5387.7   32.11  5404.2   33.89  5440.5   35.79  5464.7   39.04
#Mann= 5 ,-1 , 0
  4594.2     .05       0  4828.5      .1       0  5103.3     .05       0
  5123.9      .1       0  5232.3     .12       0
Bank Sta=5103.3,5123.9
XS Rating Curve= 0 ,0
Exp/Cntr=0.3,0.1

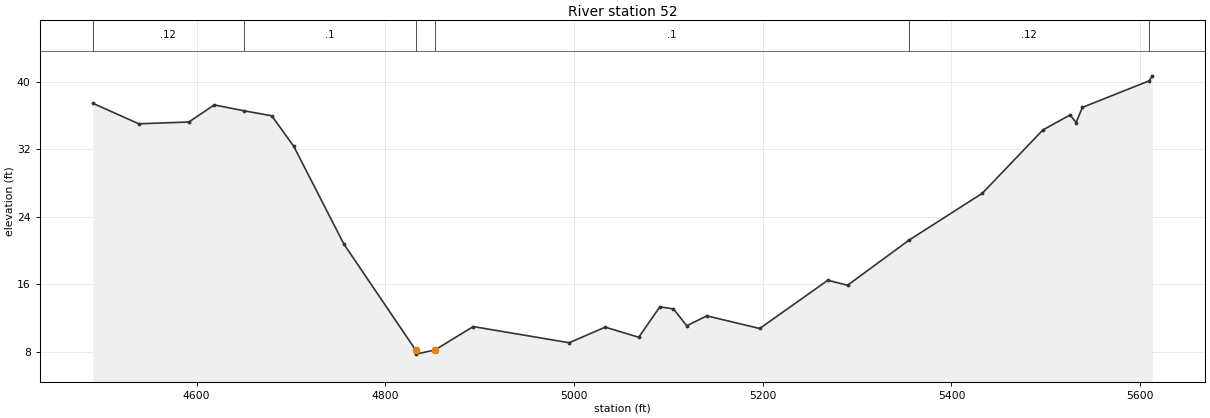
Type RM Length L Ch R = 1 ,52      ,0,0,0
BEGIN DESCRIPTION:
DRY KUY CREEK 1.0
END DESCRIPTION:
XS GIS Cut Line= 3
       2625581.6     13387268.15        2625075.       13387175.
      2624699.86     13387653.35
#Sta/Elev= 30
    4490   37.45  4538.8   35.01  4591.8   35.22  4618.7   37.25  4649.9   36.56
  4679.7   35.96    4703   32.34  4756.1   20.75  4832.1    8.19  4832.6    7.69
  4852.7    8.19  4893.2   10.96  4994.9    9.04  5033.1   10.89  5068.6    9.69
    5091    13.3  5105.4   13.05  5119.5   11.05  5140.7   12.23  5196.8   10.73
    5269   16.45  5289.9   15.86  5354.8   21.19  5432.7   26.77  5496.9   34.28
  5525.8   36.06  5532.1   35.16  5538.8   36.96  5609.4    40.1    5613    40.7
#Mann= 6 ,-1 , 0
    4490     .12       0  4649.9      .1       0  4832.1     .05       0
  4852.7      .1       0  5354.8     .12       0  5609.4     .07       0
Bank Sta=4832.1,4852.7
XS Rating Curve= 0 ,0
Exp/Cntr=0.3,0.1

Chan Stop Cuts=-1
Use User Specified Reach Order=0
Composite Channel Slope=5