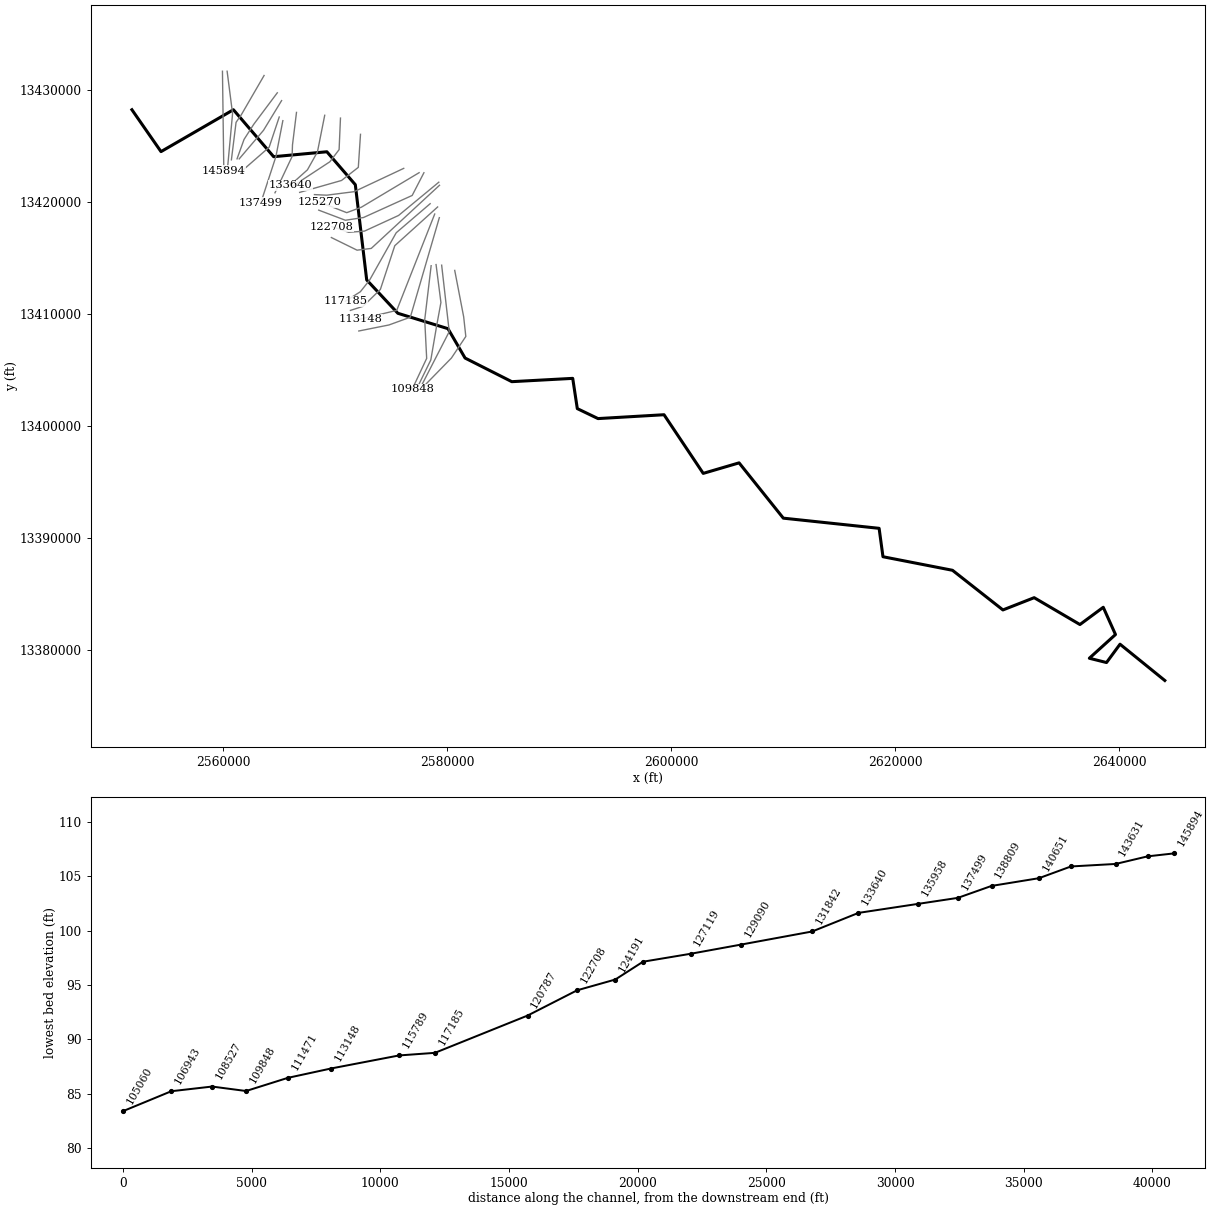
--- KUY CREEK.prj (project) ---

Proj Title=KUY CREEK Base Level Engineering
Current Plan=p01
Default Exp/Contr=0.3,0.1
English Units
Geom File=g01
Flow File=f01
Plan File=p01
Y Axis Title=Elevation
X Axis Title(PF)=Main Channel Distance
X Axis Title(XS)=Station
BEGIN DESCRIPTION:
KUY CREEK
END DESCRIPTION:
DSS Export Rating Curves= 0
DSS Export Rating Curve Sorted= 0
DSS Export Volume Flow Curves= 0
DXF OffsetX= 0
DXF OffsetY= 0
DXF ScaleX= 1
DXF ScaleY= 10

--- KUY CREEK.p01 (plan) ---

Plan Title=Multiple Run
Program Version=4.10
Short Identifier=Multiple
Geom File=g01
Flow File=f01
Subcritical Flow
K Sum by GR= 0
Std Step Tol= 0.01
Critical Tol= 0.01
Num of Std Step Trials= 20
Max Error Tol= 0.3
Flow Tol Ratio= 0.001
Split Flow NTrial= 30
Split Flow Tol= 0.02
Split Flow Ratio= 0.02
Log Output Level= 0
Friction Slope Method= 1
Unsteady Friction Slope Method= 2
Unsteady Bridges Friction Slope Method= 1
Parabolic Critical Depth
Global Vel Dist= 1 , 1 , 1
Global Log Level= 0
CheckData=True
Encroach Param=-1 ,0,0, 0
BEGIN DESCRIPTION:
Multiple Run
END DESCRIPTION:
Computation Interval=1HOUR
Output Interval=1HOUR
Run HTab= 0
Run UNet= 0
Run PostProcess= 0
Run WQNet= 0
UNET Theta= 1
UNET Theta Warmup= 1
UNET ZTol= 0.02
UNET ZSATol= 0.05
UNET MxIter= 20
UNET MaxInSteps= 0
UNET DtIC= 0
UNET DtMin= 0
UNET MaxCRTS= 20
UNET WFStab= 2
UNET SFStab= 1
UNET WFX= 1
UNET SFX= 1
UNET DSS MLevel= 4
UNET DZMax Abort= 100
UNET Convert EG Bridges= 0
UNET Use Existing IB Tables=-1
UNET Froude Reduction=False
UNET Froude Limit= 1
UNET Froude Power= 10
UNET Time Slicing=0,0, 5
UNET Junction Losses=0
Instantaneous Interval=1HOUR
Write IC File= 0
Write IC File at Sim End=0
Echo Input=False
Echo Parameters=False
Echo Output=False
Write Detailed= 0
WQ AD Non Conservative
WQ ULTIMATE=-1
WQ Max Comp Step=1HOUR
WQ Output Interval=15MIN
WQ Output Selected Increments= 0
WQ Output face flow=0
WQ Output face velocity=0
WQ Output face area=0
WQ Output face dispersion=0
WQ Output cell volume=0
WQ Output cell surface area=0
WQ Output cell continuity=0
WQ Output cumulative cell continuity=0
WQ Output face conc=0
WQ Output face dconc_dx=0
WQ Output face courant=0
WQ Output face peclet=0
WQ Output face adv mass=0
WQ Output face disp mass=0
WQ Output cell mass=0
WQ Output cell source sink temp=0
WQ Output cell source sink nsm=0
WQ Output MaxMinRange=-1
WQ Daily Max Min Mean=-1
WQ Daily Range=0
WQ Daily Time=0
WQ Create Restart=0
WQ Fixed Restart=0
WQ System Summary=0
WQ Use Fixed Temperature=0
Sorting and Armoring Iterations= 10
XS Update Threshold= 0.02
Hydraulics Update Threshold= 0.02
Energy Slope Method= 1
Volume Change Method= 0
XS Weighting Method= 0
Number of US Weighted Cross Sections= 1
Number of DS Weighted Cross Sections= 1
Upstream XS Weight=0.25
Main XS Weight=0.5
Downstream XS Weight=0.25
Number of DS XS's Weighted with US Boundary= 1
Upstream Boundary Weight= 1
Weight of XSs Associated with US Boundary= 0
Number of US XS's Weighted with DS Boundary= 1
Downstream Boundary Weight= 0.5
Weight of XSs Associated with DS Boundary= 0.5
Sediment Output Level= 4
Mass or Volume Output= 0
Output Increment Type= 1
Profile and TS Output Increment= 10
XS Output Flag= 0
XS Output Increment= 10
Disregard all LS=0
Disregard all Conn=0
Disregard all Breaches=0
Disregard all Pumps=0

--- KUY CREEK.f01 (steady flow) ---

Flow Title=Multiple
Program Version=4.10
Number of Profiles= 7
Profile Names=10-year,25-year,50-year,1pct_min,100-year,1pct_plu,500-year
River Rch & RM=KUY CREEK,Reach-1         ,145894
     911    1408    1834    1149    2292    4574    3546
River Rch & RM=KUY CREEK,Reach-1         ,141895
    1046    1624    2119    1330    2654    5296    4120
River Rch & RM=KUY CREEK,Reach-1         ,137499
    1156    1800    2354    1479    2952    5890    4596
River Rch & RM=KUY CREEK,Reach-1         ,133640
    1287    2008    2631    1657    3306    6597    5165
River Rch & RM=KUY CREEK,Reach-1         ,131842
    1457    2291    3017    1909    3809    7601    6009
River Rch & RM=KUY CREEK,Reach-1         ,120787
    1594    2517    3324    2109    4208    8397    6675
River Rch & RM=KUY CREEK,Reach-1         ,117185
    2118    3382    4501    2876    5739   11451    9231
River Rch & RM=KUY CREEK,Reach-1         ,113148
    2298    3678    4903    3137    6260   12490   10096
River Rch & RM=KUY CREEK,Reach-1         ,109848
    2717    4373    5852    3758    7498   14960   12175
River Rch & RM=KUY CREEK,Reach-1         ,108527
    2753    4430    5929    3807    7597   15158   12337
River Rch & RM=KUY CREEK,Reach-1         ,106943
    2860    4610    6177    3970    7922   15805   12889
River Rch & RM=KUY CREEK,Reach-1         ,102008
    3008    4862    6528    4204    8389   16738   13705
River Rch & RM=KUY CREEK,Reach-1         ,97637
    3238    5250    7064    4559    9096   18148   14917
River Rch & RM=KUY CREEK,Reach-1         ,94570
    3389    5509    7424    4799    9576   19107   15760
River Rch & RM=KUY CREEK,Reach-1         ,93425
    3469    5649    7623    4934    9845   19644   16243
River Rch & RM=KUY CREEK,Reach-1         ,91553
    4415    7260    9863    6426   12822   25583   21428
River Rch & RM=KUY CREEK,Reach-1         ,86058
    4555    7498   10195    6647   13263   26463   22196
River Rch & RM=KUY CREEK,Reach-1         ,83316
    4973    8199   11162    7288   14541   29013   24390
River Rch & RM=KUY CREEK,Reach-1         ,75892
    5347    8856   12096    7923   15808   31542   26688
River Rch & RM=KUY CREEK,Reach-1         ,70381
    5589    9268   12669    8304   16568   33058   28009
River Rch & RM=KUY CREEK,Reach-1         ,66542
    5895    9806   13434    8825   17609   35135   29902
River Rch & RM=KUY CREEK,Reach-1         ,58477
    5640    9372   12832    8429   16818   33555   28567
River Rch & RM=KUY CREEK,Reach-1         ,52824
    5916    9854   13516    8893   17745   35405   30245
River Rch & RM=KUY CREEK,Reach-1         ,41439
    5910    9839   13490    8873   17704   35324   30152
River Rch & RM=KUY CREEK,Reach-1         ,36551
    6795   11343   15582   10266   20484   40870   34997
Boundary for River Rch & Prof#=KUY CREEK,Reach-1         , 1
Up Type= 0
Dn Type= 3
Dn Slope=0.003
Boundary for River Rch & Prof#=KUY CREEK,Reach-1         , 2
Up Type= 0
Dn Type= 3
Dn Slope=0.003
Boundary for River Rch & Prof#=KUY CREEK,Reach-1         , 3
Up Type= 0
Dn Type= 3
Dn Slope=0.003
Boundary for River Rch & Prof#=KUY CREEK,Reach-1         , 4
Up Type= 0
Dn Type= 3
Dn Slope=0.003
Boundary for River Rch & Prof#=KUY CREEK,Reach-1         , 5
Up Type= 0
Dn Type= 3
Dn Slope=0.003
Boundary for River Rch & Prof#=KUY CREEK,Reach-1         , 6
Up Type= 0
Dn Type= 3
Dn Slope=0.003
Boundary for River Rch & Prof#=KUY CREEK,Reach-1         , 7
Up Type= 0
Dn Type= 3
Dn Slope=0.003
DSS Import GetInterval= 0
DSS Import GetPeak= 0
DSS Import FillOption= 0

--- KUY CREEK.g01 (geometry) ---

Geom Title=Existing Conditions
Program Version=4.10

River Reach=KUY CREEK       ,Reach-1
Reach XY= 30
        2551875.       13428275.       2554471.9     13424532.52
      2560935.19     13428275.45      2564526.52     13424078.74
      2569277.46     13424519.48      2571817.21     13421578.43
      2572832.99      13413068.6       2575614.7     13410086.16
      2580088.79     13408711.63        2581615.     13406086.24
      2585785.43     13403976.05      2591223.51      13404271.4
      2591632.81     13401568.18      2593480.94     13400677.26
      2599373.59     13401021.81      2602872.71     13395780.84
      2606073.51      13396721.4       2610022.3     13391780.36
      2618573.75     13390871.49      2618918.52      13388332.7
      2625123.64     13387121.73      2629626.28     13383578.37
      2632414.29     13384674.19      2636500.08     13382274.76
      2638581.76     13383815.88      2639673.39     13381381.02
      2637338.19     13379261.27      2638873.53     13378878.53
      2640078.29      13380516.9        2644075.       13377275.

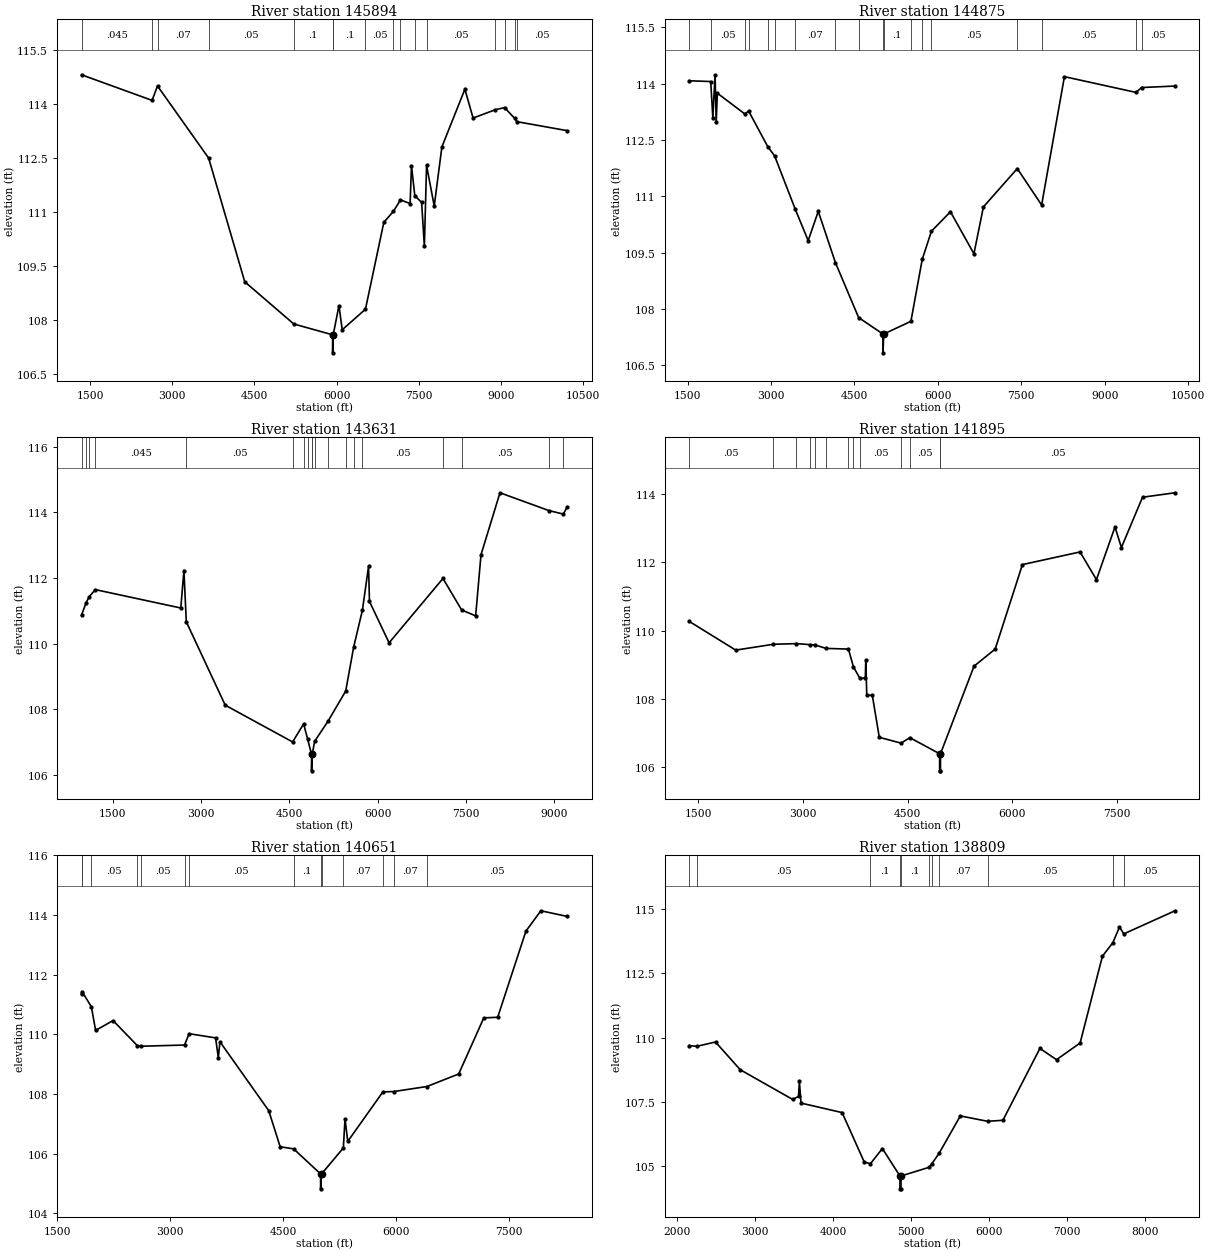
Type RM Length L Ch R = 1 ,145894  ,1019,1019,1019
BEGIN DESCRIPTION:
Mapping XS 24a3e228
END DESCRIPTION:
XS GIS Cut Line= 3
       2559957.2     13431716.06      2560009.29     13427948.65
      2560078.73      13422844.5
#Sta/Elev= 30
  1341.7  114.81  2630.7   114.1  2729.4   114.5  3663.5   112.5    4323  109.07
  5218.4   107.9  5927.5   107.6    5928   107.1  5938.9   107.6  6043.2  108.41
  6103.2  107.74  6527.5  108.31  6863.3  110.72  7036.7  111.02  7167.2  111.34
  7343.3  111.24  7367.7  112.29  7428.6  111.46  7553.3  111.27  7603.4  110.05
  7643.6   112.3  7783.4  111.17  7923.4  112.81  8343.4  114.41  8493.4  113.61
  8897.2  113.84  9068.1   113.9  9253.6   113.6  9292.6  113.51 10214.1  113.26
#Mann= 16 ,-1 , 0
  1341.7    .045       0  2630.7    .035       0  2729.4     .07       0
  3663.5     .05       0  5218.4      .1       0  5927.5     .05       0
  5938.9      .1       0  6527.5     .05       0  7036.7     .12       0
  7167.2     .05       0  7428.6     .07       0  7643.6     .05       0
  8897.2     .07       0  9068.1     .05       0  9253.6     .07       0
  9292.6     .05       0
Bank Sta=5927.5,5938.9
XS Rating Curve= 0 ,0
Exp/Cntr=0.3,0.1

Type RM Length L Ch R = 1 ,144875  ,1244,1244,1244
BEGIN DESCRIPTION:
Mapping XS a1231095
END DESCRIPTION:
XS GIS Cut Line= 3
      2560373.86     13431716.06      2560859.98     13427931.29
      2560408.59     13423035.42
#Sta/Elev= 30
  1530.7  114.08    1917  114.06  1955.2   113.1  1995.5  114.24  2015.7  112.98
  2035.9  113.75  2526.8   113.2  2600.2  113.27    2944  112.32  3065.4  112.08
  3436.1  110.66  3669.2  109.82  3850.4   110.6  4159.6  109.23    4576  107.77
  5014.4  107.33  5014.9  106.83  5025.9  107.33  5515.8  107.67  5719.3  109.32
  5884.1  110.07  6226.6  110.59  6648.3  109.47  6819.1  110.72  7427.9  111.74
  7865.4  110.77  8275.2  114.19  9562.7  113.77    9662   113.9 10263.2  113.94
#Mann= 18 ,-1 , 0
  1530.7    .045       0    1917     .05       0  2526.8    .035       0
  2600.2     .07       0    2944    .035       0  3065.4     .05       0
  3436.1     .07       0  4159.6     .05       0    4576      .1       0
  5014.4     .05       0  5025.9      .1       0  5515.8     .05       0
  5719.3     .07       0  5884.1     .05       0  7427.9     .07       0
  7865.4     .05       0  9562.7     .07       0    9662     .05       0
Bank Sta=5014.4,5025.9
XS Rating Curve= 0 ,0
Exp/Cntr=0.3,0.1

Type RM Length L Ch R = 1 ,143631  ,1736,1736,1736
BEGIN DESCRIPTION:
Mapping XS 1de81255
END DESCRIPTION:
XS GIS Cut Line= 4
       2563672.5      13431334.1      2561641.23     13427827.13
      2561172.48     13427150.04      2560755.86     13423799.72
#Sta/Elev= 30
   970.4  110.87  1047.6  111.25  1103.1  111.44  1205.7  111.65  2656.9  111.09
  2709.9  112.23  2750.4  110.67  3411.5  108.13  4556.4  107.01  4743.4  107.56
  4811.2   107.1  4877.8  106.63  4878.3  106.13  4889.4  106.63  4930.5  107.03
  5157.3  107.64    5458  108.56  5594.9  109.91  5741.7  111.02  5846.7  112.36
  5861.8  111.29  6195.2  110.03  7110.6  111.99  7427.7  111.03  7665.6  110.85
  7756.3  112.71  8078.8   114.6  8907.2  114.06  9155.6  113.95  9222.8  114.18
#Mann= 19 ,-1 , 0
   970.4     .05       0  1047.6    .035       0  1103.1     .05       0
  1205.7    .045       0  2750.4     .05       0  4556.4    .035       0
  4743.4     .05       0  4811.2    .035       0  4877.8     .05       0
  4889.4    .035       0  4930.5      .1       0  5157.3     .07       0
    5458     .05       0  5594.9     .07       0  5741.7     .05       0
  7110.6     .07       0  7427.7     .05       0  8907.2    .035       0
  9155.6     .05       0
Bank Sta=4877.8,4889.4
XS Rating Curve= 0 ,0
Exp/Cntr=0.3,0.1

Type RM Length L Ch R = 1 ,141895  ,1244,1244,1244
BEGIN DESCRIPTION:
Mapping XS 5b3311e8
END DESCRIPTION:
XS GIS Cut Line= 4
      2564853.01     13429788.89      2562752.34     13426976.43
      2561884.29     13425622.26      2561259.65     13423887.16
#Sta/Elev= 30
  1370.5  110.27  2036.9  109.43  2575.4   109.6  2907.3  109.62  3101.5  109.59
    3174  109.58  3331.5  109.48  3652.5  109.46  3724.1  108.94  3818.2   108.6
  3894.6  108.62  3900.9  109.13  3915.5  108.11  3994.7  108.11  4094.7  106.88
    4407  106.71  4532.8  106.87  4959.4   106.4  4959.9   105.9  4971.5   105.9
    4972   106.4  5452.7  108.96  5755.9  109.46  6146.4  111.93  6972.2   112.3
  7207.2  111.49  7472.9  113.03  7565.1  112.43  7868.1   113.9  8333.5  114.03
#Mann= 13 ,-1 , 0
  1370.5     .05       0  2575.4     .07       0  2907.3     .05       0
  3101.5     .07       0    3174     .05       0  3331.5     .07       0
  3652.5     .05       0  3724.1     .07       0  3818.2     .05       0
    4407     .07       0  4532.8     .05       0  4959.4     .05       0
    4972     .05       0
Bank Sta=4959.4,4972
XS Rating Curve= 0 ,0
Exp/Cntr=0.3,0.1

Type RM Length L Ch R = 1 ,140651  ,1842,1842,1842
BEGIN DESCRIPTION:
Mapping XS ef756ef3
END DESCRIPTION:
XS GIS Cut Line= 3
      2565236.18     13429091.85      2563621.59     13426435.59
      2561451.44      13423883.5
#Sta/Elev= 30
  1822.4  111.36  1830.4  111.43  1953.6  110.92  2009.7  110.13  2242.2  110.46
  2564.3  109.62  2607.7   109.6  3191.9  109.64  3252.4  110.02  3604.4  109.88
  3641.2  109.22  3662.6  109.75  4311.3  107.44  4463.5  106.23  4642.2  106.16
  5000.7  105.32  5001.2  104.82  5013.7  105.32  5303.4  106.19  5325.6  107.17
  5361.9  106.41  5829.2  108.07  5970.4  108.08  6414.8  108.25  6836.8  108.67
  7170.7  110.55  7355.2  110.57  7730.8  113.46  7929.6  114.14  8280.9  113.95
#Mann= 14 ,-1 , 0
  1822.4     .05       0  1830.4     .07       0  1953.6     .05       0
  2564.3     .07       0  2607.7     .05       0  3191.9     .07       0
  3252.4     .05       0  4642.2      .1       0  5000.7     .05       0
  5013.7      .1       0  5303.4     .07       0  5829.2     .05       0
  5970.4     .07       0  6414.8     .05       0
Bank Sta=5000.7,5013.7
XS Rating Curve= 0 ,0
Exp/Cntr=0.3,0.1

Type RM Length L Ch R = 1 ,138809  ,1310,1310,1310
BEGIN DESCRIPTION:
KUY CREEK 142.0
END DESCRIPTION:
XS GIS Cut Line= 3
      2565024.99     13427624.96        2564125.       13424925.
      2561576.14      13422699.7
#Sta/Elev= 30
  2154.5  109.69  2252.1  109.66  2491.8  109.83    2808  108.75  3482.6  107.59
  3556.4  107.71  3566.9  108.31    3588  107.45  4115.1  107.08  4399.7  105.15
  4478.7  105.09  4631.6  105.68  4856.7  104.61  4857.2  104.11  4869.8  104.11
  4870.3  104.61  5231.9  104.95  5264.1  105.08  5359.9   105.5  5631.3  106.95
  5981.3  106.74  6177.1  106.78  6651.7  109.58  6864.4  109.14  7167.2  109.79
  7452.9  113.17  7587.5   113.7  7672.2  114.31  7727.4  114.04  8384.1  114.94
#Mann= 11 ,-1 , 0
  2154.5     .07       0  2252.1     .05       0  4478.7      .1       0
  4856.7     .05       0  4870.3      .1       0  5231.9     .05       0
  5264.1      .1       0  5359.9     .07       0  5981.3     .05       0
  7587.5     .07       0  7727.4     .05       0
Bank Sta=4856.7,4870.3
XS Rating Curve= 0 ,0
Exp/Cntr=0.3,0.1

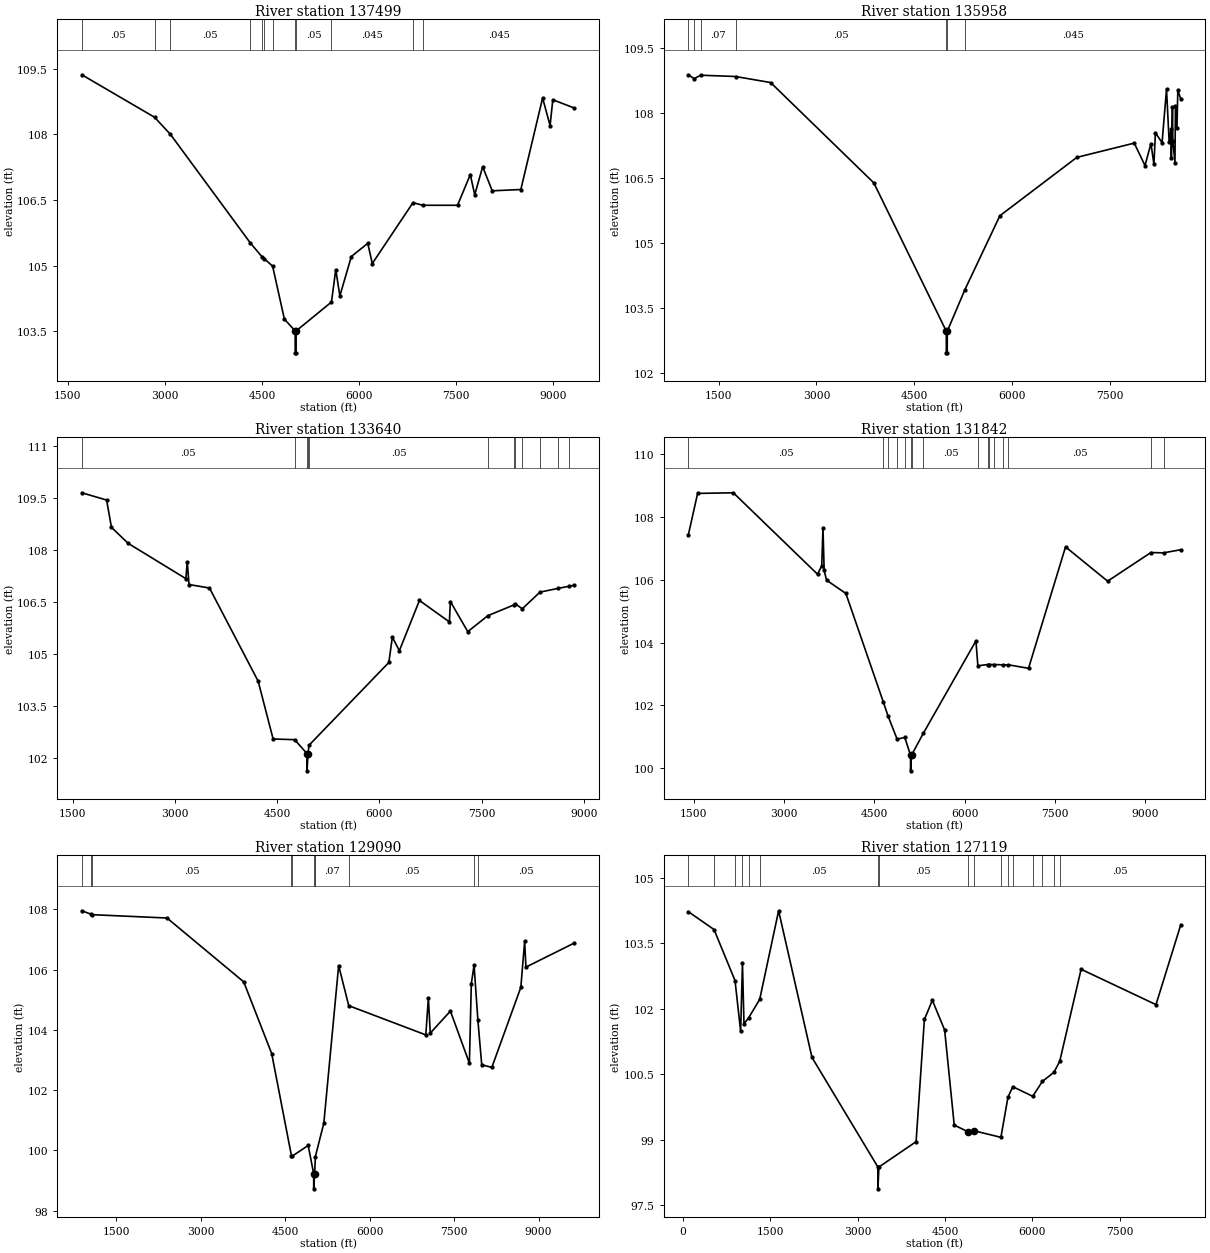
Type RM Length L Ch R = 1 ,137499  ,1541,1541,1541
BEGIN DESCRIPTION:
KUY CREEK 141.0
END DESCRIPTION:
XS GIS Cut Line= 3
      2565349.03     13427299.35        2564725.       13424075.
      2563381.52     13419958.67
#Sta/Elev= 30
  1715.8  109.36  2839.8  108.39  3085.1     108  4320.4  105.52  4502.9   105.2
  4535.2  105.16  4665.1  104.99  4847.2  103.78  5013.9  103.51  5014.4  103.01
    5028  103.01  5028.5  103.51    5575  104.17  5641.6  104.91  5704.8  104.31
  5882.3  105.21    6136  105.51  6206.5  105.05  6835.5  106.44  6986.4  106.38
  7524.6  106.38  7721.3  107.08  7790.3  106.62  7912.7  107.26    8061  106.71
  8502.9  106.74  8839.5  108.83  8955.2   108.2  8997.3  108.79    9330   108.6
#Mann= 12 ,-1 , 0
  1715.8     .05       0  2839.8    .035       0  3085.1     .05       0
  4320.4     .07       0  4502.9     .05       0  4535.2    .035       0
  4665.1     .05       0  5013.9     .05       0  5028.5     .05       0
    5575    .045       0  6835.5     .05       0  6986.4    .045       0
Bank Sta=5013.9,5028.5
XS Rating Curve= 0 ,0
Exp/Cntr=0.3,0.1

Type RM Length L Ch R = 1 ,135958  ,2318,2318,2318
BEGIN DESCRIPTION:
Mapping XS 334eb352
END DESCRIPTION:
XS GIS Cut Line= 4
      2566566.47     13428037.12       2566208.4     13425129.17
      2566175.37     13424096.01      2564645.89     13420853.98
#Sta/Elev= 30
  1036.4  108.89  1126.5   108.8  1226.2  108.88  1761.5  108.85    2298  108.71
  3879.8  106.39  4990.7  102.96  4991.2  102.46  5004.9  102.46  5005.4  102.96
  5275.6  103.92  5811.6  105.63  6991.4  106.98  7871.2  107.31  8036.1  106.79
  8127.2   107.3  8172.8  106.82  8195.6  107.55  8297.7  107.32    8366  108.56
  8406.1  107.34  8434.4  107.63  8439.9  106.96  8457.1  108.14  8462.7  107.36
  8495.1  106.86  8502.7  108.17  8525.5  107.65  8539.3  108.53  8584.7  108.33
#Mann= 7 ,-1 , 0
  1036.4     .07       0  1126.5    .035       0  1226.2     .07       0
  1761.5     .05       0  4990.7     .05       0  5005.4     .05       0
  5275.6    .045       0
Bank Sta=4990.7,5005.4
XS Rating Curve= 0 ,0
Exp/Cntr=0.3,0.1

Type RM Length L Ch R = 1 ,133640  ,1798,1798,1798
BEGIN DESCRIPTION:
Mapping XS 5219ec79
END DESCRIPTION:
XS GIS Cut Line= 4
      2569085.99     13427781.04      2568434.96     13424499.83
      2567543.03     13422904.78      2566014.41     13421538.78
#Sta/Elev= 30
  1635.1  109.66  1998.1  109.45  2069.4  108.66  2314.1   108.2  3160.7  107.18
  3180.7  107.67  3206.8  107.01  3506.9  106.91  4220.6  104.22  4440.2  102.55
  4755.4  102.53  4936.7  102.13  4937.2  101.63  4952.2  102.13  4967.2  102.37
  6137.5  104.76  6188.8  105.49  6291.9   105.1  6586.3  106.55  7025.7  105.93
  7039.9  106.52  7294.9  105.65  7589.2  106.11  7969.4  106.42  7986.7  106.46
  8094.1  106.31  8353.6  106.79  8620.8   106.9    8781  106.96  8857.8  106.99
#Mann= 12 ,-1 , 0
  1635.1     .05       0  4755.4      .1       0  4936.7     .05       0
  4952.2      .1       0  4967.2     .05       0  7589.2     .07       0
  7969.4    .035       0  7986.7     .07       0  8094.1    .035       0
  8353.6     .07       0  8620.8     .05       0    8781    .035       0
Bank Sta=4936.7,4952.2
XS Rating Curve= 0 ,0
Exp/Cntr=0.3,0.1

Type RM Length L Ch R = 1 ,131842  ,2752,2752,2752
BEGIN DESCRIPTION:
Mapping XS 3005fff8
END DESCRIPTION:
XS GIS Cut Line= 4
      2570492.25      13427529.3      2570370.21     13424710.55
      2569545.56     13423625.48      2566206.21     13421431.25
#Sta/Elev= 30
  1408.4  107.42  1562.8  108.74  2156.2  108.76  3554.7  106.17  3624.8  106.44
  3644.8  107.65  3664.8  106.29  3704.8  105.98  4025.1  105.56  4648.9   102.1
  4724.4  101.67    4876  100.93  5003.9  100.98  5099.5  100.42    5100   99.92
  5116.3  100.42  5313.8  101.12  6185.5  104.05  6218.1  103.26  6382.6   103.3
  6406.8   103.3  6487.8   103.3  6629.6  103.29    6726  103.29  7059.3  103.18
    7674  107.04    8373  105.95  9091.5  106.86    9302  106.85  9588.4  106.95
#Mann= 16 ,-1 , 0
  1408.4     .05       0  4648.9     .07       0  4724.4     .05       0
    4876     .07       0  5003.9      .1       0  5099.5     .05       0
  5116.3      .1       0  5313.8     .05       0  6218.1     .07       0
  6382.6     .05       0  6406.8    .035       0  6487.8     .05       0
  6629.6     .07       0    6726     .05       0  9091.5     .07       0
    9302     .05       0
Bank Sta=5099.5,5116.3
XS Rating Curve= 0 ,0
Exp/Cntr=0.3,0.1

Type RM Length L Ch R = 1 ,129090  ,1971,1971,1971
BEGIN DESCRIPTION:
Mapping XS c5031a1c
END DESCRIPTION:
XS GIS Cut Line= 4
      2572279.94     13426077.77      2572084.62     13423126.35
      2570587.23     13421954.47      2566848.23     13420889.24
#Sta/Elev= 30
   887.6  107.95  1058.8  107.83  1076.6  107.82  2399.9  107.71  3762.8  105.59
  4259.6  103.21    4611   99.81    4628   99.81  4907.9  100.16    5005   99.22
  5005.5   98.72  5022.4   99.22    5035   99.79  5185.5   100.9  5448.6  106.13
  5628.1   104.8    6997  103.83  7042.2  105.05  7076.1  103.89  7433.7  104.62
  7771.1  102.89    7805  105.53  7853.9  106.14  7922.2  104.31  7989.8  102.84
  8169.4  102.75  8684.8  105.41  8752.5  106.94    8775  106.08  9634.7  106.88
#Mann= 11 ,-1 , 0
   887.6     .05       0  1058.8     .07       0  1076.6     .05       0
    4611     .07       0    4628     .05       0    5005     .05       0
  5022.4     .05       0    5035     .07       0  5628.1     .05       0
  7853.9     .07       0  7922.2     .05       0
Bank Sta=5005,5022.4
XS Rating Curve= 0 ,0
Exp/Cntr=0.3,0.1

Type RM Length L Ch R = 1 ,127119  ,1849,1849,1849
BEGIN DESCRIPTION:
Mapping XS 764a1915
END DESCRIPTION:
XS GIS Cut Line= 4
      2576137.73     13423035.45      2571710.68     13420952.13
      2569262.76     13420639.63      2568169.53     13420691.68
#Sta/Elev= 30
    95.2  104.22   536.9  103.81   897.2  102.64   993.4  101.48  1024.8  103.04
  1050.8  101.65    1132  101.79  1320.8  102.21  1645.5  104.24  2218.2  100.88
  3349.7   98.37  3350.2   97.87  3367.3   98.37  4005.8   98.95  4148.1  101.75
  4284.9  102.19  4495.6  101.51  4660.6   99.33  4894.1   99.18  5001.7    99.2
  5461.9   99.05  5583.1   99.97  5665.4  100.21  6008.2   99.99  6173.6  100.33
  6372.8  100.54  6471.5  100.79  6838.5   102.9  8124.3  102.09  8550.2  103.92
#Mann= 17 ,-1 , 0
    95.2     .05       0   536.9     .07       0   897.2    .035       0
  1024.8     .05       0    1132     .07       0  1320.8     .05       0
  3349.7     .07       0  3367.3     .05       0  4894.1     .05       0
  5001.7     .05       0  5461.9     .05       0  5583.1     .07       0
  5665.4     .05       0  6008.2     .07       0  6173.6     .05       0
  6372.8    .035       0  6471.5     .05       0
Bank Sta=4894.1,5001.7
XS Rating Curve= 0 ,0
Exp/Cntr=0.3,0.1

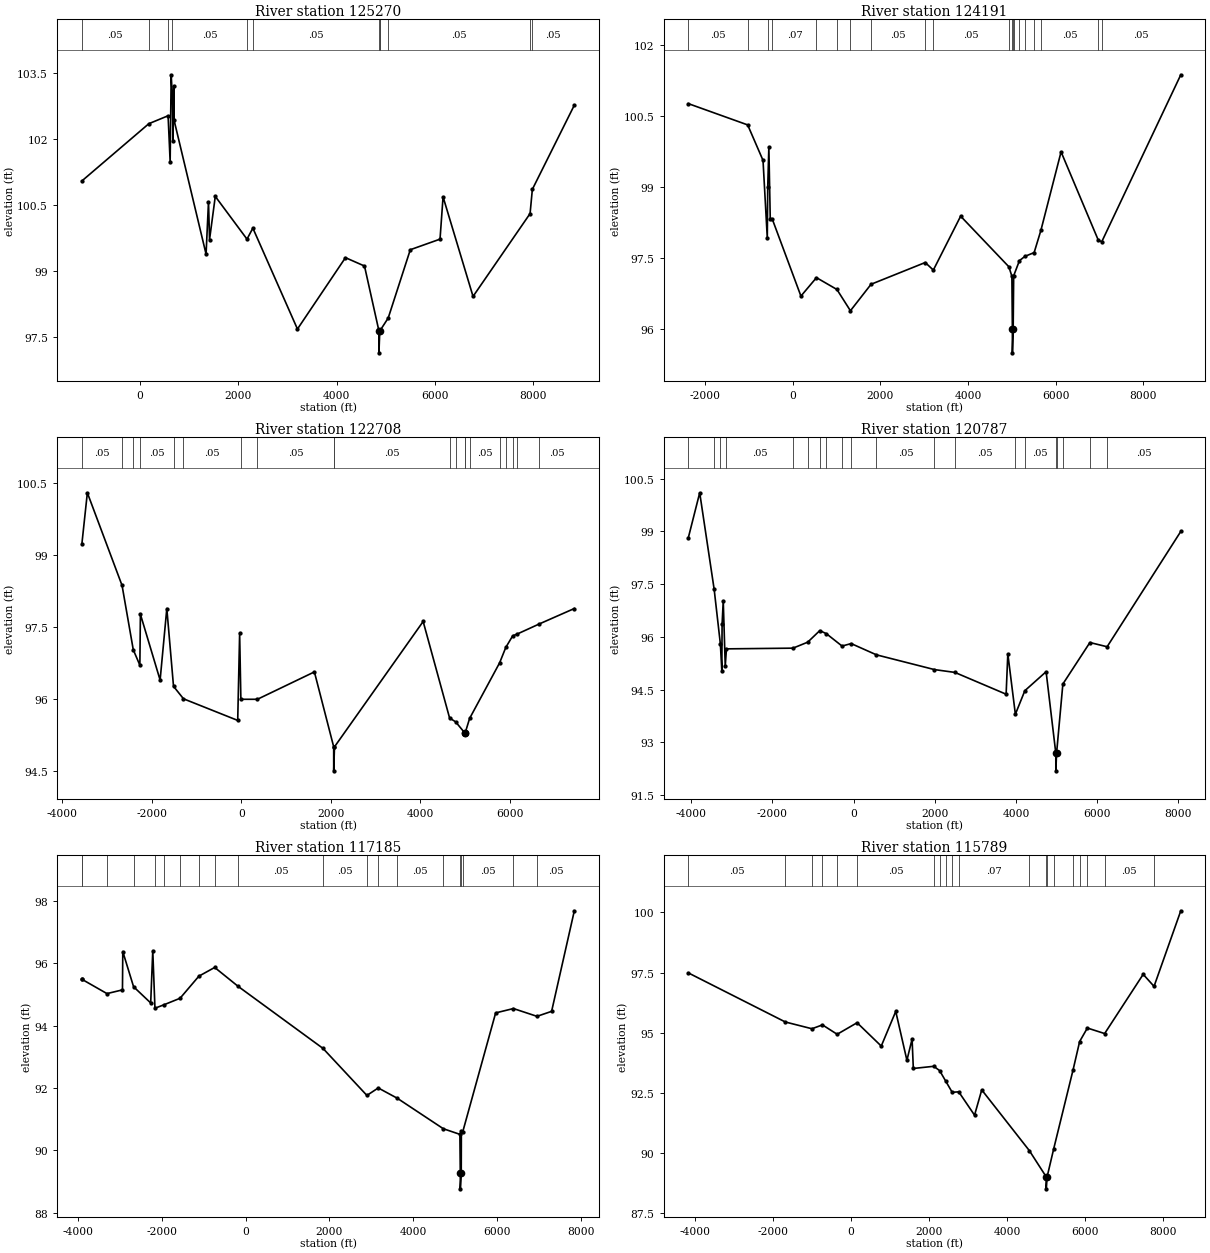
Type RM Length L Ch R = 1 ,125270  ,1079,1079,1079
BEGIN DESCRIPTION:
Mapping XS 3648a10b
END DESCRIPTION:
XS GIS Cut Line= 4
      2577512.39     13422650.75      2572353.04     13419563.24
      2571050.95     13419077.13      2568620.38     13420031.99
#Sta/Elev= 30
 -1180.4  101.04   181.9  102.34   573.3  102.52   614.9  101.48   636.3  103.45
   662.7  102.88   673.2  101.94   688.8  103.19   694.6  102.42  1345.4   99.38
  1394.8  100.57  1416.1   99.71  1532.8  100.69  2177.6   99.72    2297   99.97
  3203.5   97.68  4179.8    99.3  4566.8   99.11  4859.9   97.64  4860.4   97.14
  4877.7   97.64  4880.5   97.64    5049   97.93  5498.2   99.48  6102.6   99.72
  6164.4  100.68    6774   98.42  7933.8   100.3    7980  100.85  8833.5  102.76
#Mann= 12 ,-1 , 0
 -1180.4     .05       0   181.9     .07       0   573.3    .035       0
   662.7     .05       0  2177.6     .07       0    2297     .05       0
  4859.9     .05       0  4877.7     .05       0  4880.5      .1       0
    5049     .05       0  7933.8    .035       0    7980     .05       0
Bank Sta=4859.9,4877.7
XS Rating Curve= 0 ,0
Exp/Cntr=0.3,0.1

Type RM Length L Ch R = 1 ,124191  ,1483,1483,1483
BEGIN DESCRIPTION:
Mapping XS 8cd55e5c
END DESCRIPTION:
XS GIS Cut Line= 5
      2577940.86     13422646.36      2576893.04     13420615.52
      2572544.01      13418643.1      2570929.43     13418400.04
      2568550.99     13419302.81
#Sta/Elev= 30
 -2383.3  100.77 -1029.1  100.32  -678.7   99.57  -581.4   97.93    -571   99.01
  -545.7   99.85  -513.8   98.33  -464.1   98.32   186.2    96.7   540.8   97.09
  1007.3   96.84  1315.6   96.39  1786.6   96.95  3022.8   97.41  3207.6   97.25
  3830.7   98.39  4931.1   97.32  4999.9   97.12  5011.2      96  5011.7    95.5
  5029.1      96  5040.9   97.13  5172.6   97.45  5297.2   97.54  5507.8   97.62
    5662   98.09  6122.4   99.75  6972.9   97.88  7051.1   97.85  8854.1  101.38
#Mann= 20 ,-1 , 0
 -2383.3     .05       0 -1029.1     .05       0    -571     .05       0
  -464.1     .07       0   540.8     .05       0  1007.3     .07       0
  1315.6     .07       0  1786.6     .05       0  3022.8     .07       0
  3207.6     .05       0  4931.1      .1       0  5011.2     .05       0
  5029.1      .1       0  5040.9     .05       0  5172.6     .07       0
  5297.2     .05       0  5507.8     .07       0    5662     .05       0
  6972.9     .07       0  7051.1     .05       0
Bank Sta=5011.2,5029.1
XS Rating Curve= 0 ,0
Exp/Cntr=0.3,0.1

Type RM Length L Ch R = 1 ,122708  ,1921,1921,1921
BEGIN DESCRIPTION:
Mapping XS 505241b0
END DESCRIPTION:
XS GIS Cut Line= 5
      2579271.89     13421800.56      2575676.33     13418827.11
      2572630.82     13417427.82      2571224.57     13417323.65
      2569731.54     13417827.12
#Sta/Elev= 30
 -3561.3   99.23 -3438.5   100.3   -2663   98.37 -2412.2   97.03 -2265.3   96.71
 -2253.1   97.77 -1812.8    96.4   -1663   97.89 -1513.3   96.27 -1290.4   96.01
     -79   95.56     -36   97.37    -8.4      96   361.1      96  1634.2   96.57
  2065.3   95.01  2065.8   94.51  2083.2   95.01  4064.2   97.62    4655   95.61
  4790.4   95.53  4993.3    95.3  5003.4    95.3  5101.6    95.6  5773.2   96.76
  5910.8   97.08  6063.9   97.32    6169   97.36  6662.2   97.57  7441.8   97.89
#Mann= 20 ,-1 , 0
 -3561.3     .05       0   -2663     .07       0 -2412.2    .035       0
 -2265.3     .05       0 -1513.3    .035       0 -1290.4     .05       0
    -8.4     .07       0   361.1     .05       0  2065.3     .07       0
  2083.2     .05       0    4655     .07       0  4790.4      .1       0
  4993.3     .05       0  5003.4      .1       0  5101.6     .05       0
  5773.2     .05       0  5910.8     .07       0  6063.9     .05       0
    6169     .07       0  6662.2     .05       0
Bank Sta=4993.3,5003.4
XS Rating Curve= 0 ,0
Exp/Cntr=0.3,0.1

Type RM Length L Ch R = 1 ,120787  ,3602,3602,3602
BEGIN DESCRIPTION:
Mapping XS 25e3614a
END DESCRIPTION:
XS GIS Cut Line= 4
      2579331.79     13421524.51      2573238.45     13415882.68
      2571971.09     13415726.43      2569679.74     13416854.75
#Sta/Elev= 30
 -4072.9   98.82 -3792.3   100.1 -3435.7   97.35 -3283.2    95.8 -3247.4   95.04
 -3240.6   96.36 -3212.2   97.03 -3162.9   95.17 -3133.5   95.66 -1494.4   95.68
 -1131.2   95.85  -832.8   96.18  -669.2   96.09  -284.9   95.74   -59.8   95.81
   562.8   95.49    1993   95.07  2495.3   94.99  3758.2   94.37  3800.1   95.52
    3986    93.8  4219.6   94.47  4743.5   95.01  4982.7   92.69  4983.2   92.19
  5001.5   92.69  5156.5   94.66  5822.6   95.84  6247.1   95.72  8062.3      99
#Mann= 20 ,-1 , 0
 -4072.9     .05       0 -3435.7     .07       0 -3283.2    .035       0
 -3133.5     .05       0 -1494.4     .05       0 -1131.2     .05       0
  -832.8     .07       0  -669.2     .05       0  -284.9     .07       0
   -59.8     .05       0   562.8     .05       0    1993     .07       0
  2495.3     .05       0    3986     .07       0  4219.6     .05       0
  4982.7     .05       0  5001.5     .07       0  5156.5     .05       0
  5822.6     .07       0  6247.1     .05       0
Bank Sta=4982.7,5001.5
XS Rating Curve= 0 ,0
Exp/Cntr=0.3,0.1

Type RM Length L Ch R = 1 ,117185  ,1396,1396,1396
BEGIN DESCRIPTION:
Mapping XS 3b056549
END DESCRIPTION:
XS GIS Cut Line= 5
       2578498.5     13419878.72      2575467.04     13417280.47
       2573082.2     13413035.46      2572266.23     13412011.15
       2570929.7     13411160.64
#Sta/Elev= 30
 -3909.3   95.49 -3908.4   95.49 -3309.5   95.03 -2939.9   95.15 -2932.2   96.38
 -2674.5   95.25   -2266   94.73 -2216.6   96.41 -2164.3   94.56 -1952.4   94.67
 -1565.3   94.88 -1115.8   95.59  -738.3   95.87  -176.6   95.26  1846.9   93.27
  2895.1   91.76  3165.6      92  3619.3   91.67  4719.6   90.69  5114.5   90.51
    5124   89.26  5124.5   88.76  5146.6   89.26  5149.8   90.63  5182.4   90.59
  5968.1   94.41  6392.2   94.55  6954.7    94.3  7303.8   94.46  7846.1   97.69
#Mann= 20 ,-1 , 0
 -3909.3      .1       0 -3908.4     .05       0 -3309.5     .07       0
 -2674.5     .05       0 -2164.3     .07       0 -1952.4     .05       0
 -1565.3     .07       0 -1115.8     .05       0  -738.3     .07       0
  -176.6     .05       0  1846.9     .05       0  2895.1     .07       0
  3165.6     .05       0  3619.3     .05       0  4719.6     .15       0
    5124     .05       0  5146.6     .15       0  5182.4     .05       0
  6392.2     .07       0  6954.7     .05       0
Bank Sta=5124,5146.6
XS Rating Curve= 0 ,0
Exp/Cntr=0.3,0.1

Type RM Length L Ch R = 1 ,115789  ,2641,2641,2641
BEGIN DESCRIPTION:
Mapping XS 1874efa2
END DESCRIPTION:
XS GIS Cut Line= 5
      2579165.14     13419587.03      2575339.15     13416125.74
      2574054.43     13412219.49      2572509.29     13410709.07
      2571380.79     13410344.48
#Sta/Elev= 30
   -4172   97.49 -1685.7   95.45 -1004.4   95.17  -735.4   95.33  -358.1   94.94
   152.3   95.42   771.4   94.45  1142.7   95.89  1428.8   93.86  1561.3   94.74
  1593.1   93.52  2117.8   93.61  2267.3   93.43  2420.9      93  2588.9   92.53
  2756.3   92.55  3161.5   91.58  3346.1   92.63  4564.6   90.11  4997.6   89.02
  4998.1   88.52  5021.2   89.02  5190.8   90.19  5684.4   93.45  5854.6   94.64
  6052.3    95.2    6495   94.97  7482.5   97.43  7760.8   96.93  8446.1  100.07
#Mann= 20 ,-1 , 0
   -4172     .05       0 -1685.7     .07       0 -1004.4     .07       0
  -735.4     .05       0  -358.1     .05       0   152.3     .05       0
  2117.8     .07       0  2267.3     .05       0  2420.9     .07       0
  2588.9     .05       0  2756.3     .07       0  4564.6     .05       0
  4997.6     .05       0  5021.2     .05       0  5190.8     .07       0
  5684.4     .05       0  5854.6     .07       0  6052.3     .05       0
    6495     .05       0  7760.8     .05       0
Bank Sta=4997.6,5021.2
XS Rating Curve= 0 ,0
Exp/Cntr=0.3,0.1

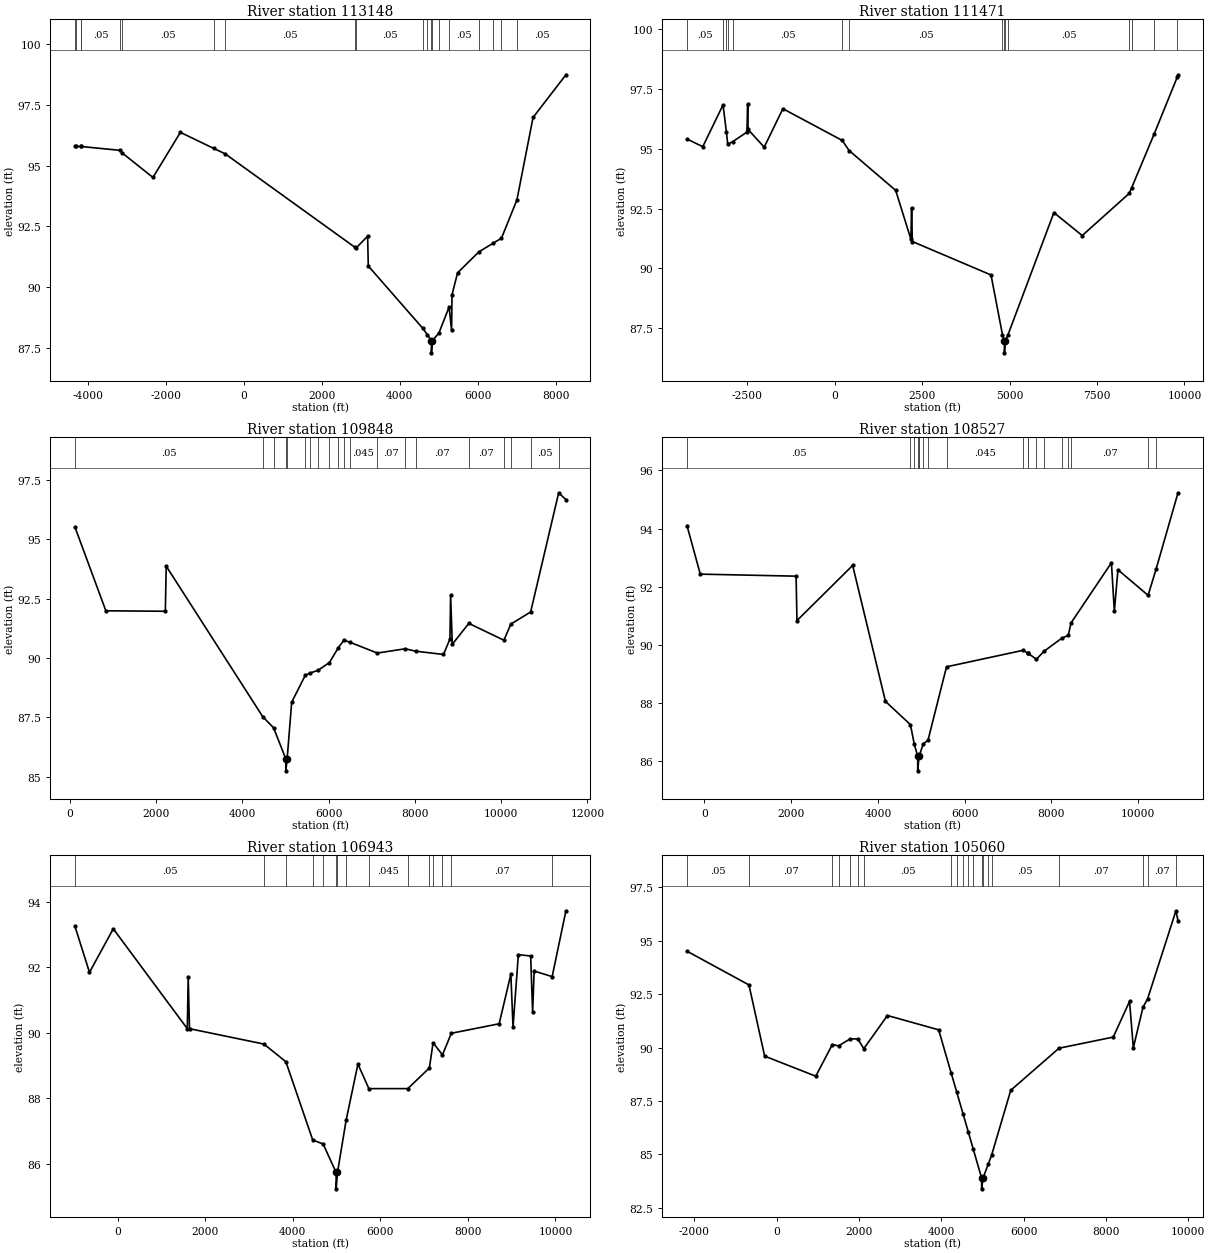
Type RM Length L Ch R = 1 ,113148  ,1677,1677,1677
BEGIN DESCRIPTION:
Mapping XS 24bd7a2c
END DESCRIPTION:
XS GIS Cut Line= 3
      2578904.53      13418955.9      2575512.76     13410344.49
      2572249.44     13409563.37
#Sta/Elev= 30
   -4346   95.78 -4307.5   95.78 -4198.7   95.78 -4188.5   95.78 -3176.3   95.62
 -3127.5   95.51 -2341.1   94.51 -1637.1   96.36  -779.7    95.7  -487.5   95.48
  2851.7   91.64  2871.3   91.61  3171.7    92.1  3189.1   90.88    4591   88.32
    4705   88.06  4809.9   87.82  4810.4   87.32  4835.7   87.82  5004.9   88.14
  5264.7    89.2  5328.6   88.24  5338.9    89.7  5482.4    90.6  6028.8   91.46
  6390.8   91.81  6609.2   92.02  7006.3   93.59  7420.6   96.97  8264.8   98.72
#Mann= 20 ,-1 , 0
   -4346     .07       0 -4307.5     .05       0 -4198.7     .07       0
 -4188.5     .05       0 -3176.3     .07       0 -3127.5     .05       0
  -779.7     .07       0  -487.5     .05       0  2851.7     .07       0
  2871.3     .05       0    4591     .07       0    4705      .1       0
  4809.9     .05       0  4835.7      .1       0  5004.9     .07       0
  5264.7     .05       0  6028.8     .07       0  6390.8     .05       0
  6609.2     .07       0  7006.3     .05       0
Bank Sta=4809.9,4835.7
XS Rating Curve= 0 ,0
Exp/Cntr=0.3,0.1

Type RM Length L Ch R = 1 ,111471  ,1623,1623,1623
BEGIN DESCRIPTION:
Mapping XS 7b6ae318
END DESCRIPTION:
XS GIS Cut Line= 4
      2579316.87     13418630.44      2576728.04     13409736.85
      2574818.32      13409042.4      2572128.67     13408504.48
#Sta/Elev= 30
   -4223   95.41 -3771.9   95.09 -3192.2   96.84 -3097.3   95.72 -3058.3    95.2
 -2916.4    95.3 -2509.3    95.7 -2488.4   96.86 -2476.9   95.81 -2015.2   95.07
 -1481.3   96.68   215.8   95.35   411.1   94.93  1743.1   93.26  2177.5   91.22
  2198.3   92.53  2219.2   91.12  4468.8   89.72    4796   87.22  4851.6   86.96
  4852.1   86.46  4877.5   86.96  4950.1    87.2  6266.6   92.33    7076   91.37
  8424.2   93.14  8491.9   93.38  9129.7   95.61  9798.1   98.02  9814.7    98.1
#Mann= 15 ,-1 , 0
   -4223     .05       0 -3192.2     .07       0 -3097.3     .05       0
 -3058.3     .07       0 -2916.4     .05       0   215.8     .07       0
   411.1     .05       0    4796      .1       0  4851.6     .05       0
  4877.5      .1       0  4950.1     .05       0  8424.2     .07       0
  8491.9     .05       0  9129.7     .07       0  9798.1     .05       0
Bank Sta=4851.6,4877.5
XS Rating Curve= 0 ,0
Exp/Cntr=0.3,0.1

Type RM Length L Ch R = 1 ,109848  ,1321,1321,1321
BEGIN DESCRIPTION:
Mapping XS 94689935
END DESCRIPTION:
XS GIS Cut Line= 4
      2578585.68     13414337.58      2578012.76     13409511.15
      2578186.37     13406056.29      2576884.64     13403279.28
#Sta/Elev= 30
   114.8   95.52   832.4   91.99    2212   91.97  2232.1   93.87  4471.1   87.53
  4722.8   87.06    5006   85.75  5006.5   85.25  5036.6   85.75  5141.5   88.14
  5456.3   89.27  5554.9   89.36    5749   89.48  6017.8   89.81  6223.7   90.44
  6353.5   90.75  6485.5   90.67  7127.3   90.21  7773.6   90.39  8013.7   90.29
  8661.8   90.15  8811.3    90.8  8827.1   92.65  8866.5   90.58  9249.3   91.46
 10063.6   90.75 10223.8   91.43 10682.8   91.94 11333.4   96.96 11501.3   96.67
#Mann= 20 ,-1 , 0
   114.8     .05       0  4471.1     .07       0  4722.8     .12       0
    5006     .05       0  5036.6     .12       0  5456.3    .035       0
  5554.9     .07       0    5749     .05       0  6017.8     .07       0
  6223.7     .07       0  6353.5     .05       0  6485.5    .045       0
  7127.3     .07       0  7773.6     .05       0  8013.7     .07       0
  9249.3     .07       0 10063.6     .07       0 10223.8     .05       0
 10682.8     .05       0 11333.4     .07       0
Bank Sta=5006,5036.6
XS Rating Curve= 0 ,0
Exp/Cntr=0.3,0.1

Type RM Length L Ch R = 1 ,108527  ,1584,1584,1584
BEGIN DESCRIPTION:
Mapping XS f4cadc24
END DESCRIPTION:
XS GIS Cut Line= 5
      2579024.41     13414439.01      2579458.43     13411053.62
      2579093.85      13409057.1      2578555.65     13405914.73
      2577375.12     13403501.58
#Sta/Elev= 30
    -401    94.1   -94.5   92.43  2113.4   92.36  2133.6   90.83  3417.3   92.73
  4173.5   88.05  4749.3   87.25    4837   86.58  4916.6   86.16  4917.1   85.66
  4947.4   86.16  4948.9   86.16  5044.3   86.59  5153.6   86.71  5580.5   89.24
  7351.9   89.81  7447.9   89.71  7452.2   89.71  7455.6   89.71  7653.7    89.5
    7824   89.77  8241.9   90.23  8386.5   90.32  8450.4   90.75  9381.1   92.82
  9448.6   91.16    9532   92.58 10226.4    91.7 10412.5   92.61 10916.2   95.23
#Mann= 20 ,-1 , 0
    -401     .05       0  4749.3     .12       0    4837     .05       0
  4916.6     .05       0  4947.4     .05       0  4948.9     .05       0
  5044.3     .07       0  5153.6     .05       0  5580.5    .045       0
  7351.9     .07       0  7447.9     .05       0  7452.2     .07       0
  7455.6     .05       0  7653.7     .07       0    7824     .05       0
  8241.9     .07       0  8386.5     .05       0  8450.4     .07       0
 10226.4     .05       0 10412.5     .07       0
Bank Sta=4916.6,4947.4
XS Rating Curve= 0 ,0
Exp/Cntr=0.3,0.1

Type RM Length L Ch R = 1 ,106943  ,1883,1883,1883
BEGIN DESCRIPTION:
Mapping XS 7401910a
END DESCRIPTION:
XS GIS Cut Line= 3
      2579524.16     13414385.79      2580201.29     13408448.17
      2577806.22     13403788.47
#Sta/Elev= 30
  -976.1   93.25  -643.2   91.84   -99.7   93.17  1591.2   90.12  1611.4   91.71
  1641.5   90.12  3342.5   89.65    3843   89.11  4456.2   86.72  4693.5    86.6
  4990.3   85.73  4990.8   85.23  5021.7   85.73  5219.4   87.33  5488.4   89.04
  5737.6   88.29    6627   88.29  7120.2   88.92  7204.8   89.69  7419.8   89.32
  7621.6   89.98    8714   90.27  8981.1   91.78  9031.1   90.18  9152.5   92.38
  9433.6   92.34  9478.5   90.63  9513.5   91.88  9924.8   91.71 10239.2   93.72
#Mann= 15 ,-1 , 0
  -976.1     .05       0  3342.5     .07       0    3843     .05       0
  4456.2     .07       0  4693.5     .05       0  4990.3     .05       0
  5021.7     .05       0  5219.4     .07       0  5737.6    .045       0
    6627     .07       0  7120.2     .05       0  7204.8     .07       0
  7419.8     .05       0  7621.6     .07       0  9924.8     .05       0
Bank Sta=4990.3,5021.7
XS Rating Curve= 0 ,0
Exp/Cntr=0.3,0.1

Type RM Length L Ch R = 1 ,105060  ,3052,3052,3052
BEGIN DESCRIPTION:
Mapping XS 6c1368c9
END DESCRIPTION:
XS GIS Cut Line= 5
      2580691.07      13413918.2      2581489.68      13409768.9
      2581680.65     13408015.43      2580395.93     13406088.35
      2577861.84     13403492.54
#Sta/Elev= 30
 -2180.1   94.51    -674   92.93  -292.9    89.6   949.5   88.66  1351.2   90.14
  1504.6   90.08  1788.6   90.41  1971.4    90.4  2117.5   89.95  2691.4    91.5
  3936.2   90.83  4241.4    88.8  4374.6   87.92  4533.2   86.87  4653.8   86.07
  4775.1   85.26  4980.6   83.89  4981.2   83.39  5013.1   83.89    5142   84.55
  5220.6   84.95  5687.9      88  6860.7   89.97  8179.1   90.49  8575.1   92.16
    8667   89.99  8902.4   91.89  9012.2   92.27  9702.3    96.4  9752.9   95.93
#Mann= 20 ,-1 , 0
 -2180.1     .05       0    -674     .07       0  1351.2     .05       0
  1504.6     .07       0  1788.6     .05       0  1971.4     .07       0
  2117.5     .05       0  4241.4    .035       0  4374.6     .05       0
  4533.2     .07       0  4653.8    .035       0  4775.1    .035       0
  4980.6    .035       0  5013.1    .035       0    5142     .07       0
  5220.6     .05       0  6860.7     .07       0  8902.4     .05       0
  9012.2     .07       0  9702.3     .05       0
Bank Sta=4980.6,5013.1
XS Rating Curve= 0 ,0
Exp/Cntr=0.3,0.1