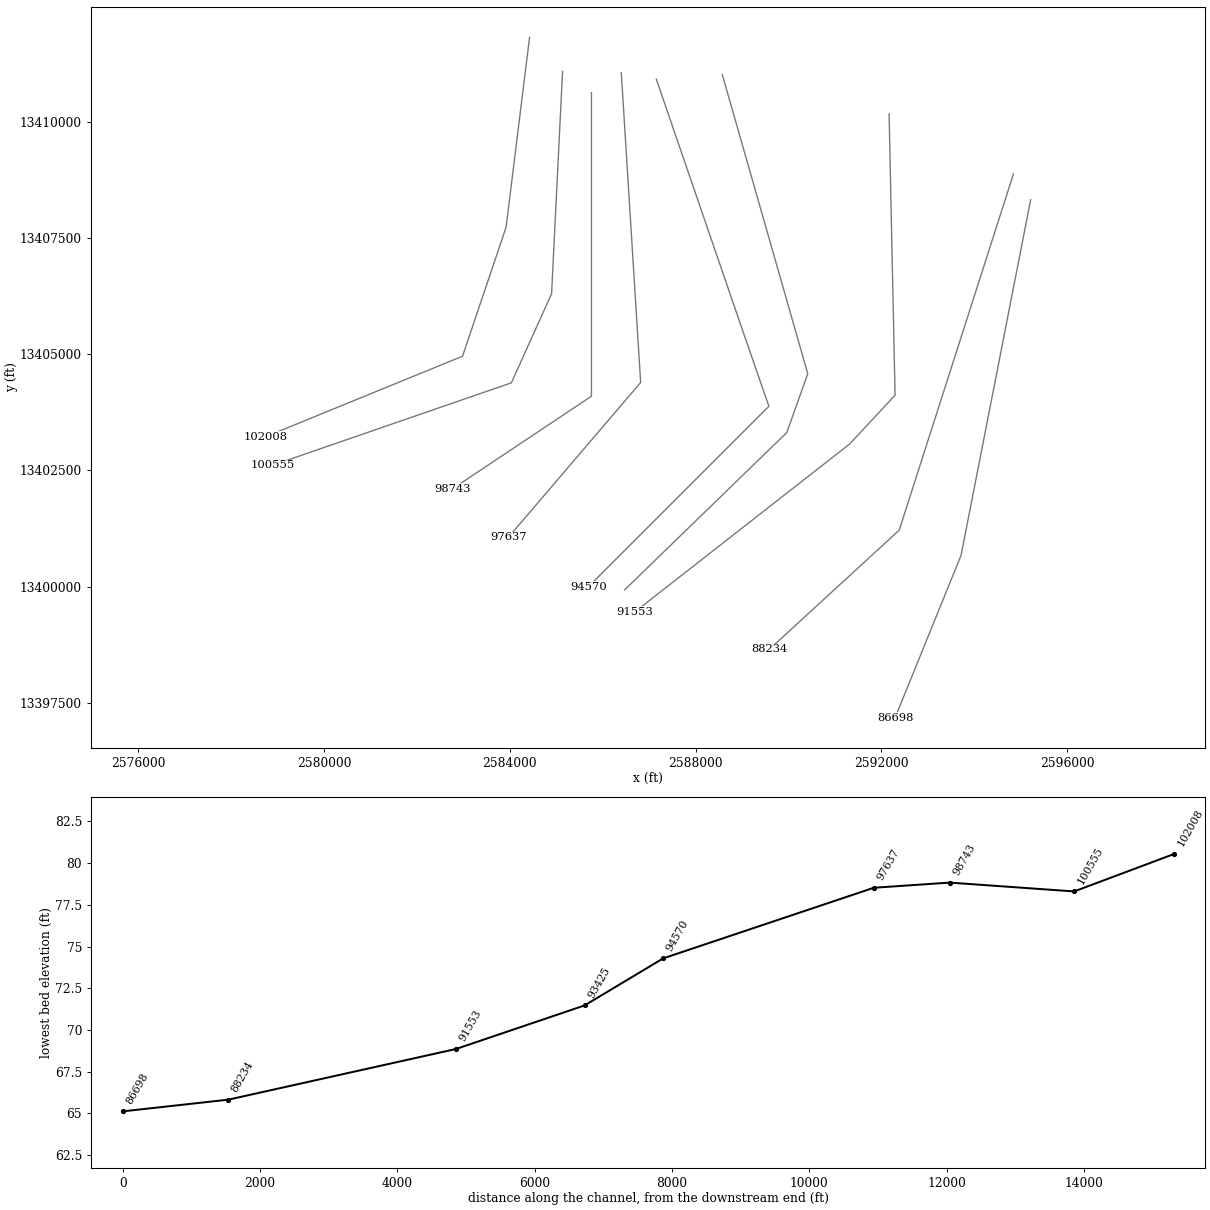
HEC-RAS study KUY CREEK.prj: KUY CREEK Base Level Engineering

--- KUY CREEK.g01 (geometry) --- (continued)

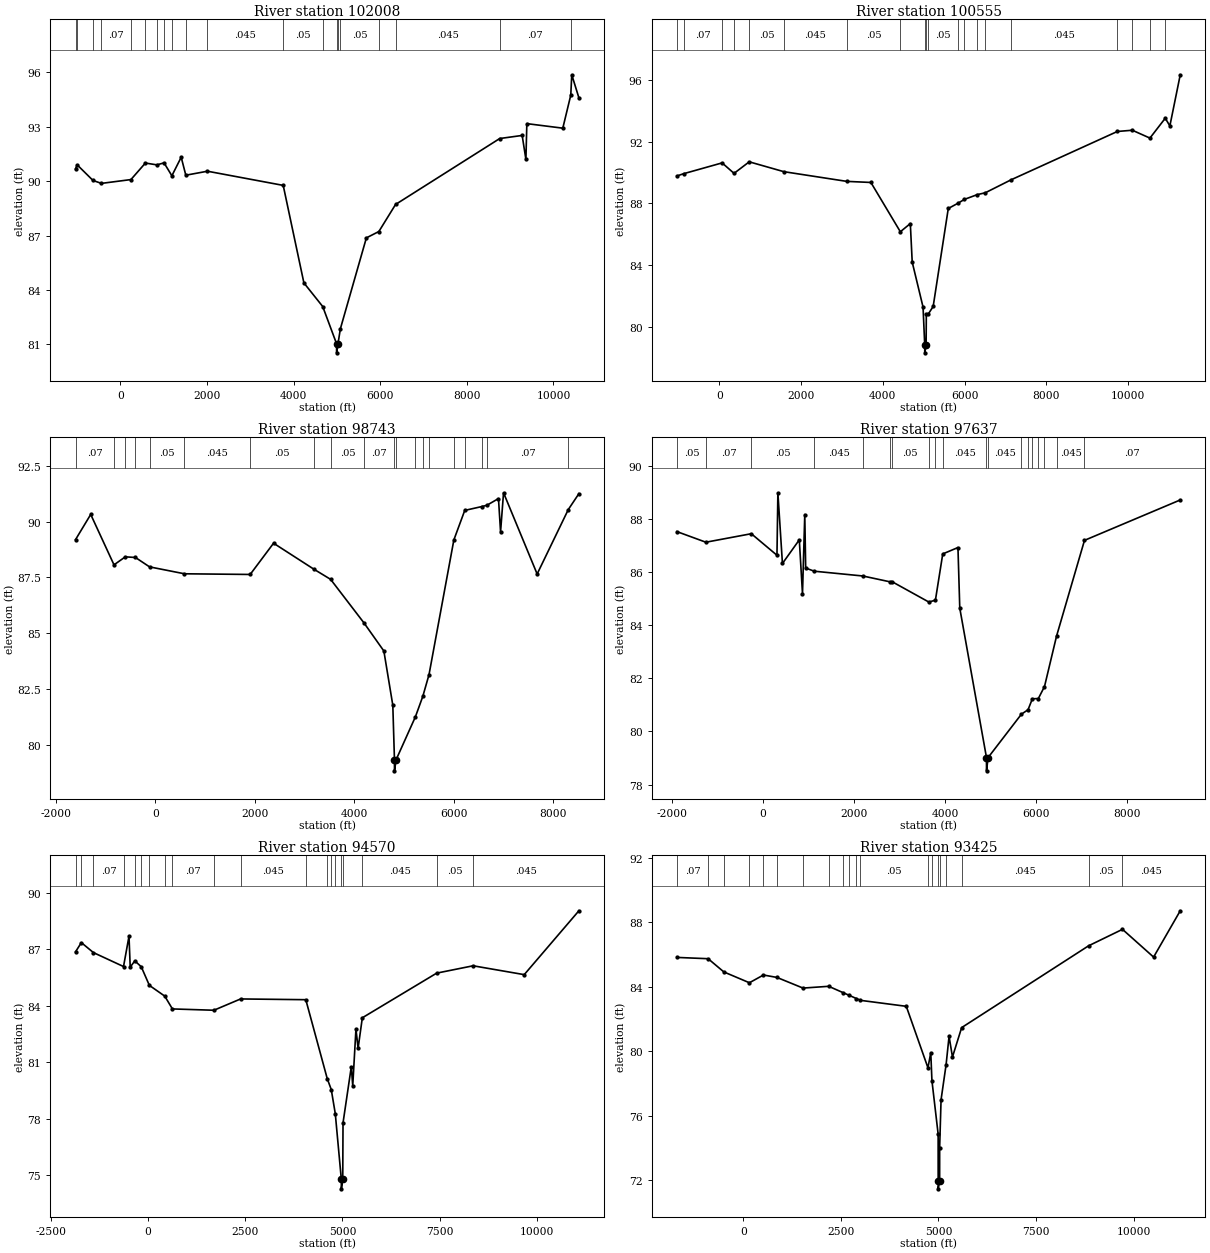
Type RM Length L Ch R = 1 ,102008  ,1453,1453,1453
BEGIN DESCRIPTION:
Mapping XS f786f08b
END DESCRIPTION:
XS GIS Cut Line= 4
      2584425.63     13411826.23      2583920.24     13407737.65
      2582982.74     13404959.87      2578752.49     13403230.75
#Sta/Elev= 30
 -1033.2   90.67  -994.9   90.89  -629.1   90.03    -435   89.87   245.7   90.08
   579.8   90.99   844.5   90.89  1010.7      91  1191.1   90.29  1406.5   91.31
  1513.1   90.32  2012.5   90.54  3761.6   89.76  4239.3   84.39  4673.7   83.09
  4993.6   81.04  4994.2   80.54  5026.8   81.04  5080.7   81.86  5681.6   86.87
    5970   87.22  6355.5   88.71  8760.4   92.34  9278.3   92.51  9364.7   91.19
  9386.3   93.16 10216.5   92.91 10400.4   94.73 10423.4   95.85 10588.2   94.58
#Mann= 20 ,-1 , 0
 -1033.2     .05       0  -994.9     .07       0  -629.1     .07       0
    -435     .07       0   245.7     .05       0   579.8     .07       0
   844.5     .05       0  1010.7     .05       0  1191.1     .07       0
  1513.1     .05       0  2012.5    .045       0  3761.6     .05       0
  4673.7     .05       0  4993.6     .05       0  5026.8      .1       0
  5080.7     .05       0    5970     .07       0  6355.5    .045       0
  8760.4     .07       0 10400.4     .07       0
Bank Sta=4993.6,5026.8
XS Rating Curve= 0 ,0
Exp/Cntr=0.3,0.1

Type RM Length L Ch R = 1 ,100555  ,1812,1812,1812
BEGIN DESCRIPTION:
Mapping XS 8a4a0d92
END DESCRIPTION:
XS GIS Cut Line= 4
      2585135.51     13411088.36      2584899.22     13406303.13
       2584033.7     13404386.62      2578903.48     13402615.78
#Sta/Elev= 30
 -1041.2   89.78  -873.8   89.93    66.2   90.63   358.5   89.95   729.9    90.7
  1577.6   90.06  3118.6   89.43  3707.9   89.36  4428.9   86.16  4673.1   86.69
  4719.3   84.19  4984.6   81.27  5025.9    78.8  5026.5    78.3  5059.3    78.8
    5065   80.79  5115.2   80.83  5232.3   81.31  5602.2   87.67    5832      88
  5996.1   88.26  6311.2   88.57  6507.9   88.69  7145.4   89.54  9740.5   92.67
 10106.9   92.75 10537.8   92.24 10913.3   93.53 11025.8   93.03   11280   96.35
#Mann= 20 ,-1 , 0
 -1041.2     .07       0  -873.8     .07       0    66.2     .07       0
   358.5     .05       0   729.9     .05       0  1577.6    .045       0
  3118.6     .05       0  4428.9     .07       0  5025.9     .05       0
  5059.3     .15       0  5115.2     .05       0    5832     .07       0
  5996.1     .05       0  6311.2     .07       0  6507.9    .045       0
  7145.4    .045       0  9740.5     .05       0 10106.9     .07       0
 10537.8     .05       0 10913.3     .05       0
Bank Sta=5025.9,5059.3
XS Rating Curve= 0 ,0
Exp/Cntr=0.3,0.1

Type RM Length L Ch R = 1 ,98743   ,1106,1106,1106
BEGIN DESCRIPTION:
Mapping XS 297dff29
END DESCRIPTION:
XS GIS Cut Line= 3
      2585757.66     13410630.89      2585757.66     13404098.79
      2582762.86     13402102.26
#Sta/Elev= 30
 -1608.8   89.19 -1302.9   90.32  -834.4   88.06  -606.5   88.42  -402.5   88.39
  -119.1   87.97   583.4   87.66  1906.3   87.63  2377.1   89.03  3185.7   87.87
  3525.6   87.41  4199.8   85.45  4597.1    84.2  4777.1   81.77  4810.3   79.33
  4810.9   78.83  4843.9   79.33  5231.7   81.25  5381.4   82.17  5505.7   83.14
  6006.2   89.18    6225    90.5  6563.1   90.67  6670.1   90.73  6903.9   91.03
  6945.9   89.54  7005.7   91.29  7682.1   87.65  8309.4   90.54  8522.6   91.25
#Mann= 20 ,-1 , 0
 -1608.8     .07       0  -834.4     .05       0  -606.5     .07       0
  -402.5     .07       0  -119.1     .05       0   583.4    .045       0
  1906.3     .05       0  3185.7     .07       0  3525.6     .05       0
  4199.8     .07       0  4810.3     .05       0  4843.9     .07       0
  5231.7     .07       0  5381.4     .05       0  5505.7     .07       0
  6006.2     .07       0    6225     .12       0  6563.1     .12       0
  6670.1     .07       0  8309.4    .045       0
Bank Sta=4810.3,4843.9
XS Rating Curve= 0 ,0
Exp/Cntr=0.3,0.1

Type RM Length L Ch R = 1 ,97637   ,3067,3067,3067
BEGIN DESCRIPTION:
Mapping XS 63800d1f
END DESCRIPTION:
XS GIS Cut Line= 3
      2586400.02     13411060.63      2586816.69     13404393.93
      2583969.74     13401060.92
#Sta/Elev= 30
   -1894   87.52   -1256   87.12  -257.9   87.44   305.9   86.63     326   88.98
   426.2   86.32   796.9   87.21     867   85.18   917.1   88.16   937.1   86.15
  1124.1   86.03  2193.1   85.85  2791.5   85.63  2830.8   85.64  3643.7   84.87
  3788.3   84.94  3949.5   86.68  4283.7   86.92  4323.7   84.64  4910.6   79.02
  4911.4   78.52  4946.4   79.02  5677.9   80.65  5824.4   80.82  5919.1   81.23
  6050.1   81.24  6185.6   81.69  6450.7   83.59  7064.4   87.19  9169.1   88.71
#Mann= 19 ,-1 , 0
   -1894     .05       0   -1256     .07       0  -257.9     .05       0
  1124.1    .045       0  2193.1     .05       0  2791.5     .07       0
  2830.8     .05       0  3643.7    .045       0  3788.3    .035       0
  3949.5    .045       0  4910.6    .045       0  4946.4    .045       0
  5677.9     .07       0  5824.4     .05       0  5919.1     .07       0
  6050.1     .05       0  6185.6     .07       0  6450.7    .045       0
  7064.4     .07       0
Bank Sta=4910.6,4946.4
XS Rating Curve= 0 ,0
Exp/Cntr=0.3,0.1

Type RM Length L Ch R = 1 ,94570   ,1145,1145,1145
BEGIN DESCRIPTION:
Mapping XS 01002600
END DESCRIPTION:
XS GIS Cut Line= 4
      2587154.36     13410922.27      2588991.17     13405574.48
       2589577.1     13403881.78      2585693.95     13399998.62
#Sta/Elev= 30
 -1858.9   86.87 -1709.4   87.36 -1398.4   86.83  -625.1   86.09  -484.5    87.7
  -453.2   86.06  -334.9   86.39    -170   86.08    39.2   85.09   434.2   84.52
   631.2   83.84  1696.9   83.77  2384.1   84.37  4059.3   84.33  4610.3   80.14
  4713.7   79.56  4817.2   78.28  4972.7   74.79  4973.5   74.29  5008.9   74.79
    5016   77.79  5228.8   80.77  5265.9   79.76  5348.2   82.77  5403.5   81.75
  5512.2   83.37    7423   85.74  8359.6   86.13  9673.1   85.66 11078.4   89.05
#Mann= 20 ,-1 , 0
 -1858.9     .07       0 -1709.4     .05       0 -1398.4     .07       0
  -625.1     .05       0  -334.9     .05       0    -170     .07       0
    39.2     .05       0   434.2     .07       0   631.2     .07       0
  1696.9     .05       0  2384.1    .045       0  4059.3     .05       0
  4610.3    .035       0  4713.7     .07       0  4817.2     .05       0
  4972.7     .05       0  5008.9     .07       0  5512.2    .045       0
    7423     .05       0  8359.6    .045       0
Bank Sta=4972.7,5008.9
XS Rating Curve= 0 ,0
Exp/Cntr=0.3,0.1

Type RM Length L Ch R = 1 ,93425   ,1872,1872,1872
BEGIN DESCRIPTION:
Mapping XS fcbf5f40
END DESCRIPTION:
XS GIS Cut Line= 4
      2588573.76     13411024.54      2590414.05     13404583.53
      2589962.66     13403316.16      2586473.09     13399930.76
#Sta/Elev= 30
 -1707.5   85.81  -906.1   85.73  -502.6   84.91   152.3   84.24   512.3   84.72
   858.4   84.57  1527.1   83.91    2185   84.02  2551.4   83.63  2711.4   83.46
  2897.6   83.26  2999.4   83.15  4174.5   82.78  4730.1   78.97  4802.5   79.91
  4831.9   78.18  4991.3   74.86  4992.1   71.97    4993   71.47  5029.8   71.97
    5030   74.02  5066.1   76.99  5195.5   79.17  5271.3   80.92  5358.5   79.64
  5593.8   81.46  8848.8   86.53  9717.3   87.55 10515.2   85.83 11198.5    88.7
#Mann= 20 ,-1 , 0
 -1707.5     .07       0  -906.1     .05       0  -502.6     .07       0
   152.3     .05       0   512.3     .05       0   858.4     .07       0
  1527.1     .05       0    2185      .1       0  2551.4     .07       0
  2711.4     .05       0  2897.6    .035       0  2999.4     .05       0
  4730.1     .05       0  4831.9     .07       0  4992.1     .05       0
  5029.8     .07       0  5195.5    .045       0  5593.8    .045       0
  8848.8     .05       0  9717.3    .045       0
Bank Sta=4992.1,5029.8
XS Rating Curve= 0 ,0
Exp/Cntr=0.3,0.1

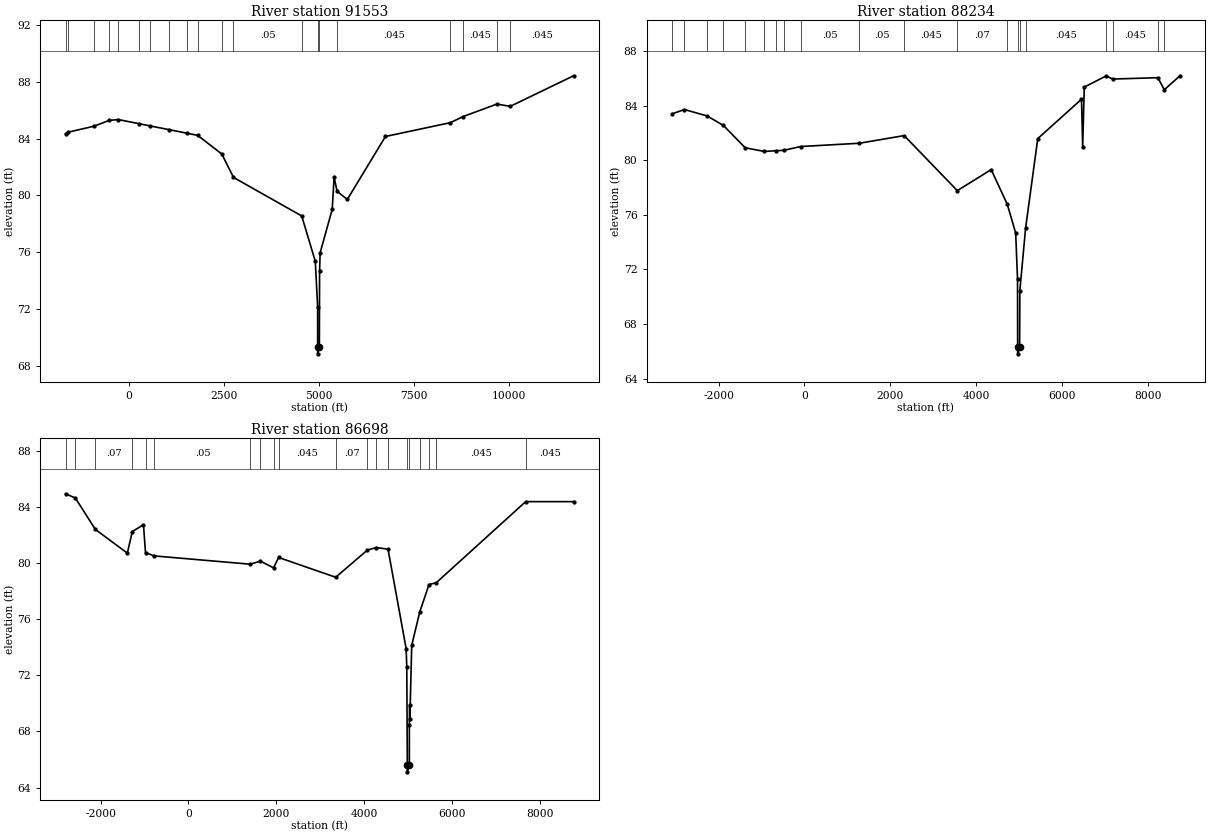
Type RM Length L Ch R = 1 ,91553   ,3319,3319,3319
BEGIN DESCRIPTION:
Mapping XS 62766a92
END DESCRIPTION:
XS GIS Cut Line= 4
      2592164.95     13410176.27      2592294.12     13404120.42
      2591316.69     13403070.72      2586690.84     13399454.71
#Sta/Elev= 30
 -1665.2   84.35 -1597.2   84.45  -905.9   84.88  -518.5   85.28  -276.6   85.34
   270.5   85.05   566.6   84.89  1059.5   84.63  1530.9   84.38  1808.8   84.23
  2444.8   82.92  2753.5   81.27  4547.5   78.56  4904.9   75.37  4966.5   72.18
  4966.9   69.36  4967.9   68.86    5012   69.36  5017.8   74.66  5031.9   75.96
  5350.5   79.03  5399.8   81.29  5478.7   80.29  5746.7   79.72  6750.9   84.15
  8456.1   85.12  8792.4   85.55  9682.3   86.43 10033.4   86.27 11697.8   88.42
#Mann= 20 ,-1 , 0
 -1665.2     .07       0 -1597.2     .05       0  -905.9     .05       0
  -518.5     .07       0  -276.6     .05       0   270.5     .07       0
   566.6     .07       0  1059.5     .05       0  1530.9     .07       0
  1808.8     .05       0  2444.8     .07       0  2753.5     .05       0
  4547.5     .07       0  4966.9     .05       0    5012     .07       0
  5478.7    .045       0  8456.1     .05       0  8792.4    .045       0
  9682.3     .05       0 10033.4    .045       0
Bank Sta=4966.9,5012
XS Rating Curve= 0 ,0
Exp/Cntr=0.3,0.1

Type RM Length L Ch R = 1 ,88234   ,1536,1536,1536
BEGIN DESCRIPTION:
Mapping XS bdc5fc95
END DESCRIPTION:
XS GIS Cut Line= 3
      2594842.17     13408882.95      2592383.84     13401216.29
      2589592.17     13398653.78
#Sta/Elev= 30
 -3086.3   83.39 -2797.3   83.71 -2268.4   83.24 -1885.9   82.54 -1380.3   80.91
  -936.3   80.64    -666   80.69  -483.2   80.72   -84.5      81  1279.8   81.24
  2325.2    81.8  3563.9   77.77  4353.5   79.31  4729.8   76.76  4924.2   74.66
  4967.5   71.28  4970.2   66.32  4971.2   65.82    5016   66.32  5021.4   70.45
  5155.2   75.02  5438.9   81.58  6458.1   84.46  6486.5   80.99  6522.2   85.35
    7034   86.17  7184.4   85.94  8237.7   86.04  8388.2   85.16  8754.3   86.18
#Mann= 20 ,-1 , 0
 -3086.3     .05       0 -2797.3     .07       0 -2268.4     .05       0
 -1885.9     .07       0 -1380.3     .05       0  -936.3     .07       0
    -666     .05       0  -483.2     .07       0   -84.5     .05       0
  1279.8     .05       0  2325.2    .045       0  3563.9     .07       0
  4729.8     .07       0  4970.2     .05       0    5016     .07       0
  5155.2    .045       0    7034    .035       0  7184.4    .045       0
  8237.7    .035       0  8388.2    .045       0
Bank Sta=4970.2,5016
XS Rating Curve= 0 ,0
Exp/Cntr=0.3,0.1

Type RM Length L Ch R = 1 ,86698   ,640,640,640
BEGIN DESCRIPTION:
Mapping XS 94af753a
END DESCRIPTION:
XS GIS Cut Line= 3
      2595212.67     13408326.92       2593714.5     13400673.78
        2592296.     13397181.04
#Sta/Elev= 30
 -2798.4   84.94 -2574.6   84.64 -2119.1    82.4 -1390.3   80.71 -1277.2   82.25
 -1023.4   82.73  -976.4   80.74  -774.3   80.51    1411   79.92  1638.3   80.14
  1939.6   79.66  2053.2    80.4  3353.4   78.99  4077.9   80.93  4280.1   81.11
  4545.5   80.99    4958    73.9  4972.3   72.61    4985   65.62    4986   65.12
    5031   65.62  5031.1   68.49  5037.5   69.86  5042.9    68.9    5085   74.14
  5267.2   76.51  5478.2   78.47  5643.9    78.6  7679.6   84.38  8769.8   84.38
#Mann= 20 ,-1 , 0
 -2798.4     .05       0 -2574.6     .07       0 -2119.1     .07       0
 -1277.2     .05       0  -976.4     .07       0  -774.3     .05       0
    1411    .035       0  1638.3     .05       0  1939.6    .035       0
  2053.2    .045       0  3353.4     .07       0  4077.9     .05       0
  4280.1     .05       0  4545.5     .07       0    4985     .05       0
    5031     .07       0  5267.2     .07       0  5478.2     .05       0
  5643.9    .045       0  7679.6    .045       0
Bank Sta=4985,5031
XS Rating Curve= 0 ,0
Exp/Cntr=0.3,0.1