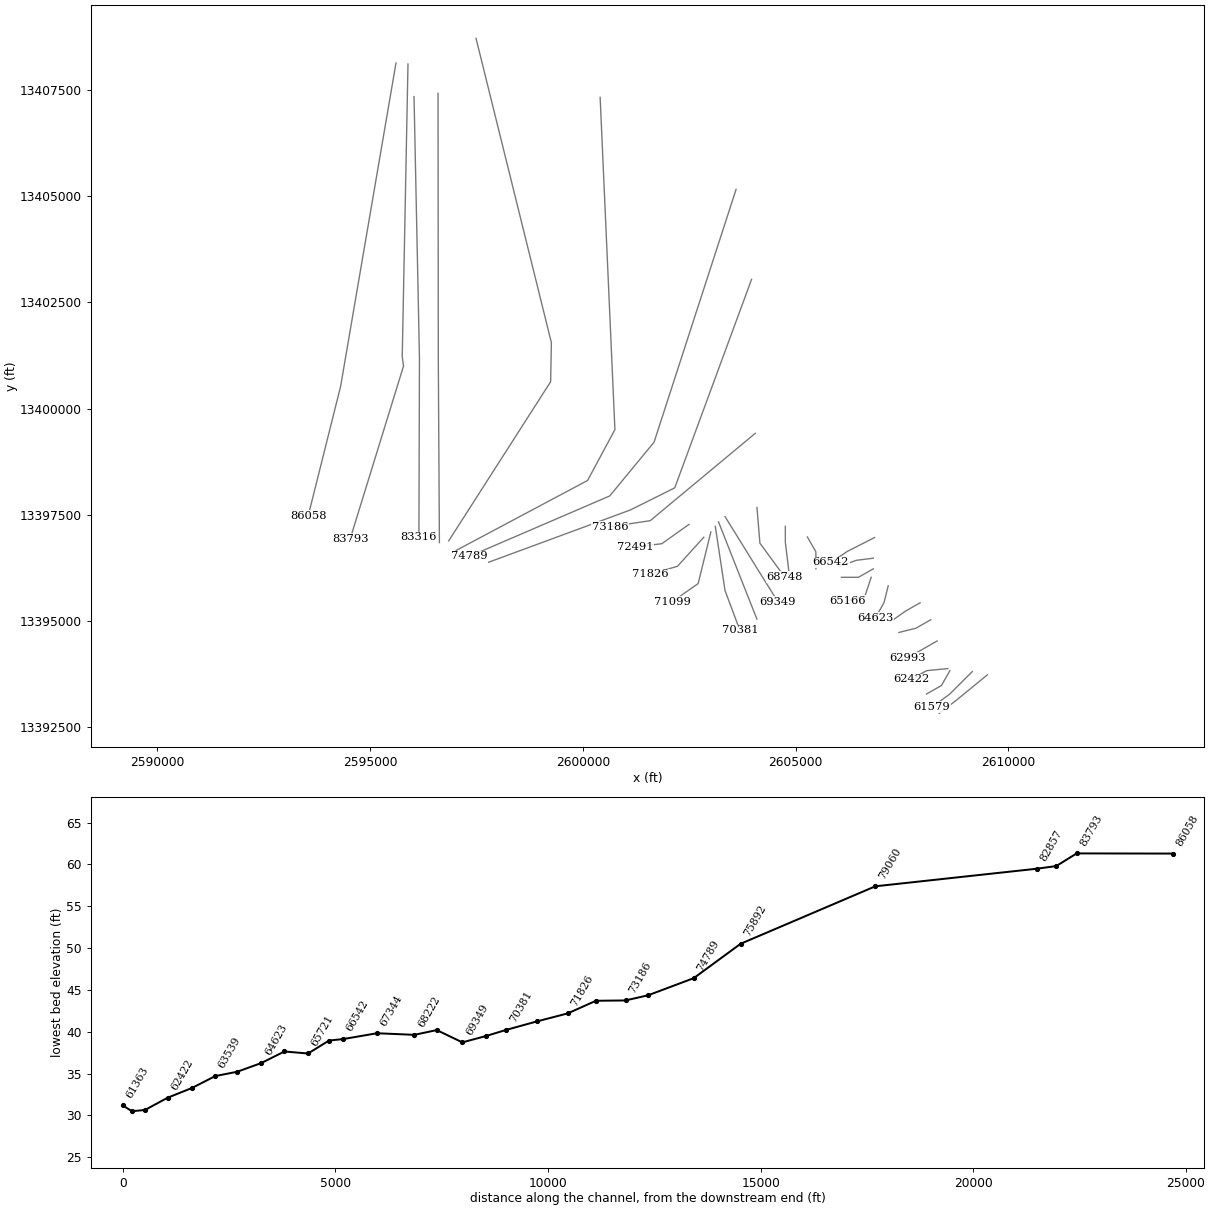
HEC-RAS study KUY CREEK.prj: KUY CREEK Base Level Engineering

--- KUY CREEK.g01 (geometry) --- (continued)

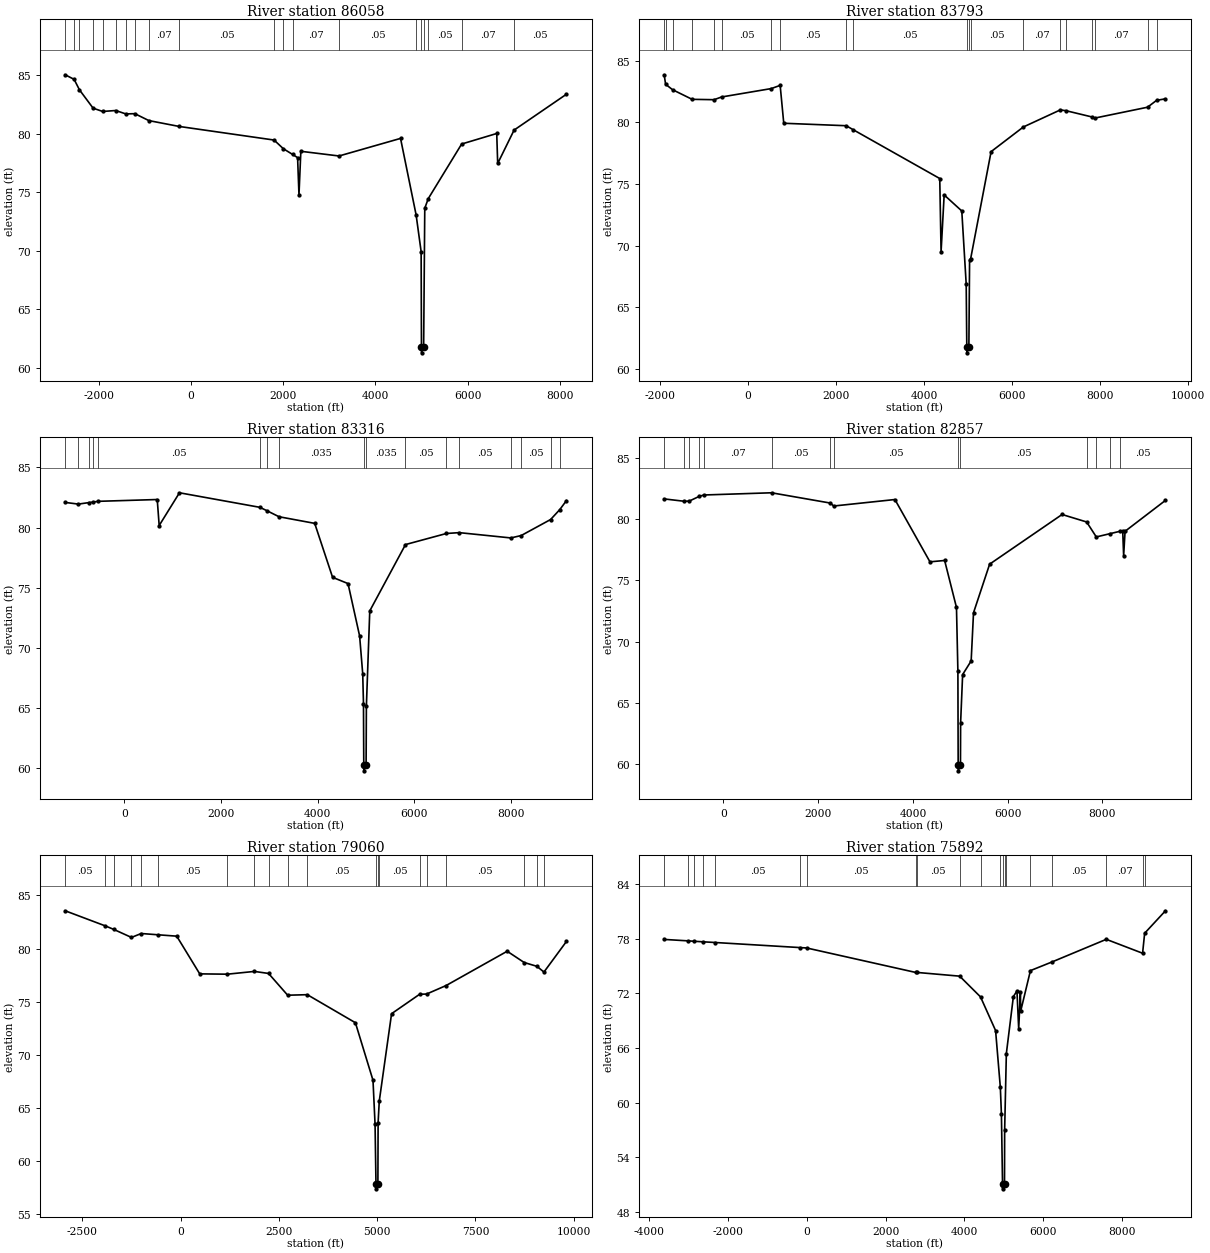
Type RM Length L Ch R = 1 ,86058   ,2265,2265,2265
BEGIN DESCRIPTION:
Mapping XS ab045514
END DESCRIPTION:
XS GIS Cut Line= 3
      2595607.63     13408140.22      2594305.55     13400518.71
       2593546.2     13397479.16
#Sta/Elev= 30
 -2726.2   85.02 -2532.4   84.63 -2415.8   83.73 -2120.7   82.17 -1913.7   81.89
   -1630   81.97 -1411.6   81.68 -1215.6    81.7  -912.1   81.11  -254.5   80.61
  1801.5   79.45  2002.7   78.71  2203.8   78.22  2311.6   77.95  2341.4   74.77
    2382   78.49  3209.5   78.09  4542.8   79.59    4881   73.05  4989.2   69.93
  4996.3   61.79  4997.3   61.29  5043.4   61.79  5068.1   73.63  5143.7   74.45
  5867.1   79.11  6627.8   80.01  6648.4   77.45  7003.8    80.3  8138.7   83.36
#Mann= 20 ,-1 , 0
 -2726.2    .035       0 -2532.4     .05       0 -2415.8    .035       0
 -2120.7     .07       0 -1913.7    .035       0   -1630     .05       0
 -1411.6    .035       0 -1215.6     .05       0  -912.1     .07       0
  -254.5     .05       0  1801.5     .07       0  2002.7     .05       0
  2203.8     .07       0  3209.5     .05       0    4881     .07       0
  4996.3     .05       0  5043.4     .07       0  5143.7     .05       0
  5867.1     .07       0  7003.8     .05       0
Bank Sta=4996.3,5043.4
XS Rating Curve= 0 ,0
Exp/Cntr=0.3,0.1

Type RM Length L Ch R = 1 ,83793   ,477,477,477
BEGIN DESCRIPTION:
Mapping XS bf96a59a
END DESCRIPTION:
XS GIS Cut Line= 4
      2595889.75     13408118.53      2595754.72     13401225.55
      2595785.16     13401002.48      2594532.03     13396932.67
#Sta/Elev= 30
 -1894.3   83.85 -1862.2   83.08 -1704.3   82.64 -1260.2   81.86  -762.4   81.83
  -592.1   82.05   534.6   82.73   737.9   82.99   819.7   79.92  2237.5   79.72
  2389.1   79.41  4360.4   75.44  4390.4   69.51  4460.4   74.11  4860.5   72.81
  4960.5   66.89  4974.2   61.81  4975.2   61.31  5021.4   61.81  5037.5   68.84
  5062.3   68.95  5525.9   77.62  6258.5   79.62  7095.6      81    7224   80.94
  7816.4   80.43  7880.3   80.34    9076   81.22  9282.9   81.78  9483.5    81.9
#Mann= 20 ,-1 , 0
 -1894.3     .05       0 -1862.2     .05       0 -1704.3     .07       0
 -1260.2     .05       0  -762.4     .07       0  -592.1     .05       0
   534.6     .07       0   737.9     .05       0  2237.5     .07       0
  2389.1     .05       0  4974.2     .05       0  5021.4     .05       0
  5062.3     .05       0  6258.5     .07       0  7095.6     .05       0
    7224     .07       0  7816.4     .05       0  7880.3     .07       0
    9076     .05       0  9282.9     .07       0
Bank Sta=4974.2,5021.4
XS Rating Curve= 0 ,0
Exp/Cntr=0.3,0.1

Type RM Length L Ch R = 1 ,83316   ,459,459,459
BEGIN DESCRIPTION:
Mapping XS 914aae00
END DESCRIPTION:
XS GIS Cut Line= 3
      2596031.75     13407351.27      2596159.46     13401190.84
      2596146.44     13396972.11
#Sta/Elev= 30
 -1227.6   82.09  -955.2   81.95  -743.8   82.07  -645.2   82.12  -546.6   82.18
   679.1   82.33   719.1   80.17  1139.2   82.89  2806.8   81.68  2950.7    81.4
  3201.3    80.9  3939.8   80.35  4309.9   75.87  4629.9   75.35    4870      71
  4934.1   67.86    4950   65.37  4955.8    60.3  4956.8    59.8  5004.1    60.3
    5010   65.15    5080   73.08  5819.9   78.59  6667.4   79.51    6933   79.58
    8002   79.14  8216.5   79.34    8825   80.67  9014.2   81.49  9152.9   82.24
#Mann= 17 ,-1 , 0
 -1227.6     .05       0  -955.2     .07       0  -743.8     .05       0
  -645.2     .07       0  -546.6     .05       0  2806.8    .035       0
  2950.7     .05       0  3201.3    .035       0  4955.8    .035       0
  5004.1    .035       0  5819.9     .05       0  6667.4     .07       0
    6933     .05       0    8002     .07       0  8216.5     .05       0
    8825    .035       0  9014.2     .05       0
Bank Sta=4955.8,5004.1
XS Rating Curve= 0 ,0
Exp/Cntr=0.3,0.1

Type RM Length L Ch R = 1 ,82857   ,3797,3797,3797
BEGIN DESCRIPTION:
Mapping XS c49e1b4c
END DESCRIPTION:
XS GIS Cut Line= 3
      2596595.98      13407427.2      2596602.17      13401164.8
      2596628.21     13396841.89
#Sta/Elev= 30
 -1252.2   81.65  -834.3   81.46  -724.7   81.47  -510.7   81.86    -412   81.97
    1014   82.15  2258.3   81.31  2325.8   81.07    3620    81.6    4360   76.52
    4670   76.63    4920    72.8    4950   67.58  4955.8   59.98  4956.8   59.48
  5004.2   59.98  5007.6   63.42    5050   67.33    5230   68.44    5280   72.37
    5620   76.33    7150   80.38  7668.7   79.77  7872.4   78.55  8155.7   78.81
  8383.4   79.02  8430.1   79.06  8450.1   77.02  8480.1   79.01  9333.2   81.53
#Mann= 14 ,-1 , 0
 -1252.2     .07       0  -834.3     .05       0  -724.7     .07       0
  -510.7     .05       0    -412     .07       0    1014     .05       0
  2258.3     .07       0  2325.8     .05       0  4955.8     .05       0
  5004.2     .05       0  7668.7     .07       0  7872.4     .05       0
  8155.7     .07       0  8383.4     .05       0
Bank Sta=4955.8,5004.2
XS Rating Curve= 0 ,0
Exp/Cntr=0.3,0.1

Type RM Length L Ch R = 1 ,79060   ,3168,3168,3168
BEGIN DESCRIPTION:
Mapping XS a13c9c1a
END DESCRIPTION:
XS GIS Cut Line= 4
      2597488.56      13408722.9      2599259.39     13401552.78
      2599242.03     13400632.64      2596846.18     13396882.61
#Sta/Elev= 30
 -2939.7   83.56 -1913.8   82.13 -1699.5    81.8 -1252.4   81.05 -1004.6   81.42
  -578.1    81.3  -100.9   81.17   484.6   77.62  1185.9   77.59  1875.4   77.85
  2235.8   77.66  2722.1   75.61  3221.8   75.66  4445.9   73.02  4893.7    67.6
  4946.2   63.45  4969.3   57.88  4970.3   57.38  5018.1   57.88  5023.7    63.6
  5052.8   65.63  5366.2   73.87  6080.4    75.7  6257.3   75.72  6753.3   76.52
  8308.4   79.75  8740.3   78.69    9065   78.33  9243.6   77.79  9816.2   80.67
#Mann= 20 ,-1 , 0
 -2939.7     .05       0 -1913.8     .07       0 -1699.5     .05       0
 -1252.4     .07       0 -1004.6     .05       0  -578.1     .05       0
  1185.9     .05       0  1875.4     .07       0  2235.8     .05       0
  2722.1      .1       0  3221.8     .05       0  4969.3     .05       0
  5018.1     .07       0  5052.8     .05       0  6080.4     .07       0
  6257.3     .05       0  6753.3     .05       0  8740.3     .05       0
    9065     .07       0  9243.6     .05       0
Bank Sta=4969.3,5018.1
XS Rating Curve= 0 ,0
Exp/Cntr=0.3,0.1

Type RM Length L Ch R = 1 ,75892   ,1103,1103,1103
BEGIN DESCRIPTION:
Mapping XS 04bff531
END DESCRIPTION:
XS GIS Cut Line= 4
      2600405.23       13407334.      2600752.45     13399504.17
      2600110.09     13398306.25      2597019.87     13396656.98
#Sta/Elev= 30
 -3607.2   77.94 -2997.2   77.78 -2861.8   77.74 -2633.2   77.68 -2311.4    77.6
  -154.7   77.04     1.9      77  2763.1   74.31  2795.8   74.31  3878.6    73.9
  4406.7   71.62  4788.4   67.92  4908.8   61.68  4936.2   58.74  4964.6   51.01
  4965.6   50.51  5014.7   51.01  5018.2   56.96  5061.4   65.39  5239.3   71.65
    5330   72.28    5374   68.12  5417.8   72.14  5423.5   70.04  5671.5   74.51
  6222.4   75.47  7593.2   77.95  8512.8   76.42  8565.1   78.62  9092.4   81.09
#Mann= 20 ,-1 , 0
 -3607.2     .05       0 -2997.2     .07       0 -2861.8     .05       0
 -2633.2     .07       0 -2311.4     .05       0  -154.7     .07       0
     1.9     .05       0  2763.1     .07       0  2795.8     .05       0
  3878.6     .07       0  4406.7     .05       0  4908.8     .07       0
  4964.6     .05       0  5014.7     .07       0  5061.4     .05       0
  5671.5     .07       0  6222.4     .05       0  7593.2     .07       0
  8512.8     .07       0  8565.1     .05       0
Bank Sta=4964.6,5014.7
XS Rating Curve= 0 ,0
Exp/Cntr=0.3,0.1

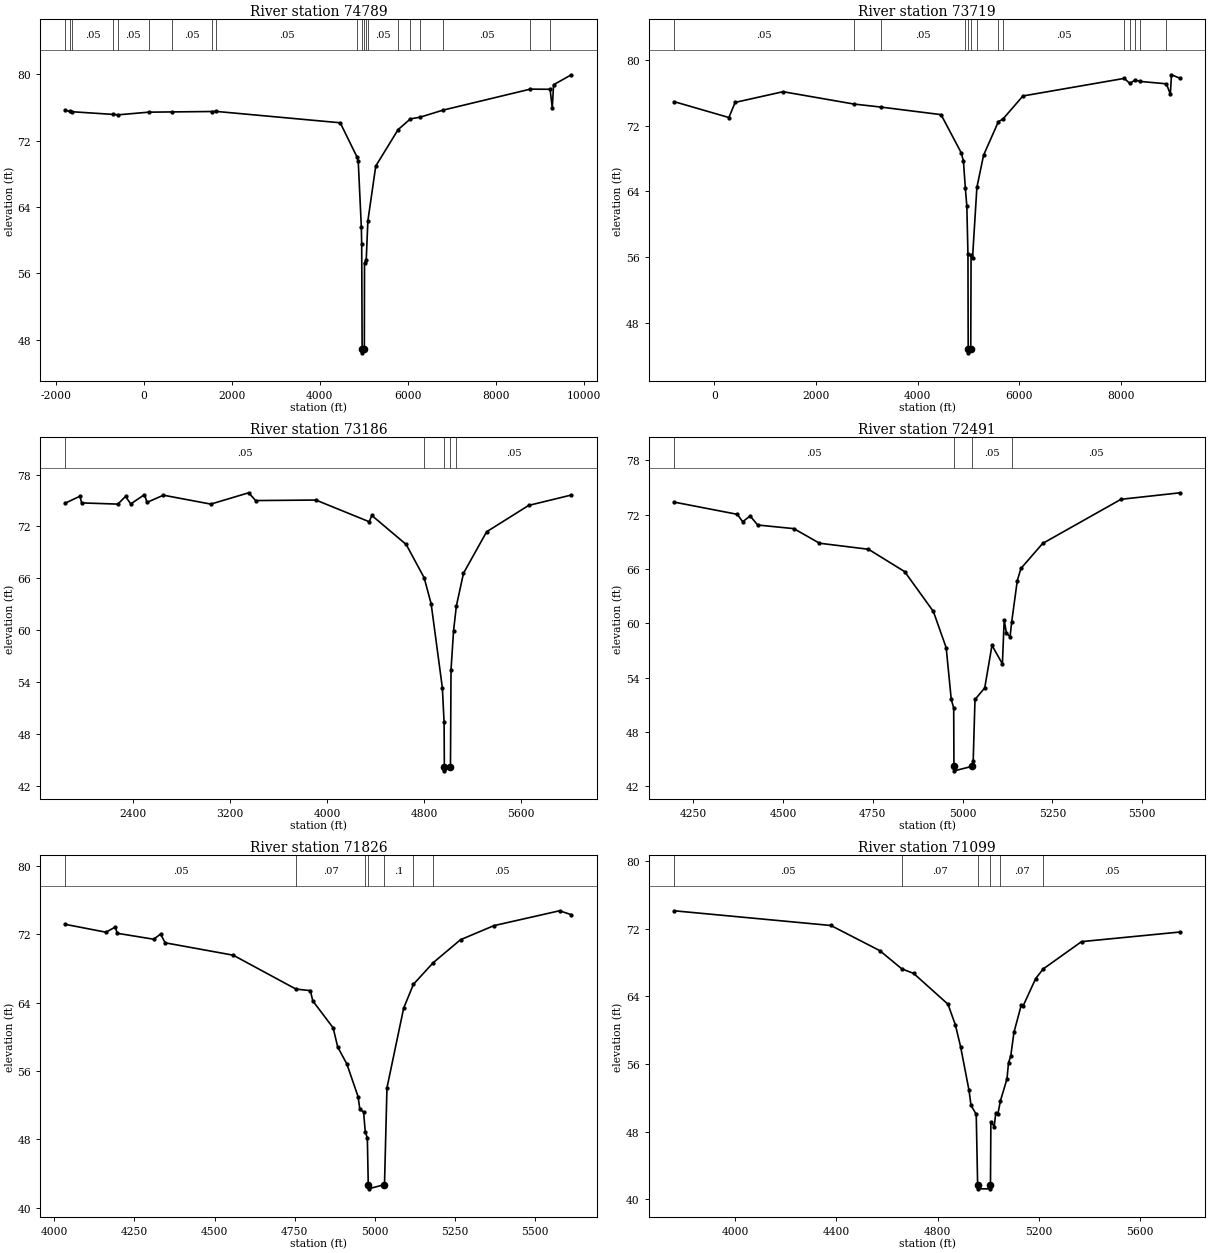
Type RM Length L Ch R = 1 ,74789   ,1070,1070,1070
BEGIN DESCRIPTION:
Mapping XS da08373c
END DESCRIPTION:
XS GIS Cut Line= 4
      2603599.67     13405163.89      2601672.59     13399209.03
      2600630.92     13397941.67      2597332.33     13396518.07
#Sta/Elev= 30
 -1778.6   75.64 -1671.1   75.53 -1621.5   75.48  -696.1   75.16  -581.6   75.11
   111.4   75.43     641   75.46  1542.8   75.51    1649   75.52  4463.5   74.15
  4845.5   70.01  4872.7   69.48  4943.1   61.53    4951   59.47    4961    46.9
    4962    46.4  5011.3    46.9  5014.8   57.18  5054.1   57.64  5091.4   62.32
  5270.2   68.93  5778.5   73.33  6057.4   74.62  6281.3   74.83    6794   75.67
  8780.7   78.21  9230.3   78.19    9280   75.93  9308.9   78.74  9713.5   79.94
#Mann= 20 ,-1 , 0
 -1778.6     .05       0 -1671.1     .07       0 -1621.5     .05       0
  -696.1    .035       0  -581.6     .05       0   111.4      .1       0
     641     .05       0  1542.8     .07       0    1649     .05       0
  4845.5     .12       0    4961     .05       0  5011.3     .12       0
  5054.1     .07       0  5091.4     .05       0  5778.5     .07       0
  6057.4     .05       0  6281.3     .07       0    6794     .05       0
  8780.7     .07       0  9230.3     .05       0
Bank Sta=4961,5011.3
XS Rating Curve= 0 ,0
Exp/Cntr=0.3,0.1

Type RM Length L Ch R = 1 ,73719   ,533,533,533
BEGIN DESCRIPTION:
Mapping XS 2427f7e4
END DESCRIPTION:
XS GIS Cut Line= 4
      2603964.26     13403045.87       2602158.7     13398132.64
      2601117.03     13397611.81      2597784.78     13396379.57
#Sta/Elev= 30
  -788.2   74.92   288.8   72.99     412   74.83  1354.2   76.13  2746.7   74.63
  3279.9   74.26  4461.6   73.34  4856.6   68.72  4901.3   67.72  4939.7   64.37
  4968.4   62.24  4990.8   56.37  4995.4   44.86  4996.4   44.36  5045.9   44.86
  5052.3   56.28  5080.2   55.85  5166.6   64.49  5298.2   68.41  5588.9   72.48
  5680.4   72.81  6071.5   75.61  8064.6   77.75  8175.1   77.14  8278.8   77.55
  8378.9   77.38  8894.3   77.09  8971.6   75.82  8993.8   78.19  9163.7   77.76
#Mann= 14 ,-1 , 0
  -788.2     .05       0  2746.7      .1       0  3279.9     .05       0
  4939.7     .07       0  4995.4     .05       0  5045.9     .07       0
  5166.6     .05       0  5588.9     .07       0  5680.4     .05       0
  8064.6      .1       0  8175.1     .07       0  8278.8     .05       0
  8378.9     .07       0  8894.3     .05       0
Bank Sta=4995.4,5045.9
XS Rating Curve= 0 ,0
Exp/Cntr=0.3,0.1

Type RM Length L Ch R = 1 ,73186   ,695,695,695
BEGIN DESCRIPTION:
Mapping XS e112e027
END DESCRIPTION:
XS GIS Cut Line= 3
      2604051.08     13399417.38      2601582.26     13397358.63
      2600635.08     13397217.64
#Sta/Elev= 30
  1841.1    74.7  1960.8   75.49  1975.1   74.72  2273.2   74.58    2337   75.47
  2379.9    74.6  2493.2   75.68    2514   74.78  2649.4   75.61  3039.9   74.58
  3352.3   75.89  3409.5   74.99  3906.3   75.05  4346.7   72.54  4367.5   73.27
  4651.3   69.91  4799.1   66.07  4856.9   63.06  4949.4   53.34  4963.7   49.34
  4965.8   44.24  4966.8   43.74  5016.3   44.24  5020.9   55.45  5041.8   59.94
  5064.9    62.8  5123.7   66.59  5314.4   71.38  5661.1   74.43  6013.3   75.63
#Mann= 5 ,-1 , 0
  1841.1     .05       0  4799.1     .07       0  4965.8     .05       0
  5016.3     .07       0  5064.9     .05       0
Bank Sta=4965.8,5016.3
XS Rating Curve= 0 ,0
Exp/Cntr=0.3,0.1

Type RM Length L Ch R = 1 ,72491   ,665,665,665
BEGIN DESCRIPTION:
Mapping XS 98331850
END DESCRIPTION:
XS GIS Cut Line= 3
      2602493.72     13397271.83      2601853.52      13396816.1
        2601235.     13396740.14
#Sta/Elev= 30
  4196.8   73.38  4372.8   72.03  4387.6   71.21  4408.5   71.85  4429.4   70.85
  4530.2   70.45  4601.5   68.84    4738   68.17  4838.8    65.7  4918.7    61.3
  4954.4   57.29  4968.5   51.58  4975.3   50.65    4976    44.2    4977    43.7
  5026.6    44.2  5029.6   44.82  5034.6   51.58  5061.7   52.86  5081.9   57.56
  5110.9   55.51  5115.9   60.36  5122.2   58.88  5132.3   58.52  5136.7   60.13
  5152.4   64.71  5162.5   66.05  5222.9   68.81  5441.2   73.69  5605.8   74.41
#Mann= 4 ,-1 , 0
  4196.8     .05       0    4976     .05       0  5026.6     .05       0
  5136.7     .05       0
Bank Sta=4976,5026.6
XS Rating Curve= 0 ,0
Exp/Cntr=0.3,0.1

Type RM Length L Ch R = 1 ,71826   ,727,727,727
BEGIN DESCRIPTION:
Mapping XS 3a32b2d4
END DESCRIPTION:
XS GIS Cut Line= 3
      2602840.96     13396968.03      2602222.45     13396284.41
      2601593.21     13396099.98
#Sta/Elev= 30
  4034.8   73.16  4161.2   72.24  4189.6   72.83  4197.1   72.11  4309.9   71.42
  4331.6   72.02  4345.8      71    4558   69.55  4753.6   65.58  4798.6    65.4
  4806.1    64.2  4869.6   61.04  4883.8    58.8  4912.2   56.82  4947.3   52.99
  4952.9    51.5  4964.5    51.2  4969.6    48.9  4976.2   48.16  4979.1   42.69
  4980.1   42.19  5029.7   42.69  5037.4   54.02  5089.5   63.35  5119.9   66.14
  5181.5   68.67  5266.7   71.36  5370.9   73.01  5575.4   74.75  5612.4   74.29
#Mann= 7 ,-1 , 0
  4034.8     .05       0  4753.6     .07       0  4969.6      .1       0
  4979.1     .05       0  5029.7      .1       0  5119.9     .07       0
  5181.5     .05       0
Bank Sta=4979.1,5029.7
XS Rating Curve= 0 ,0
Exp/Cntr=0.3,0.1

Type RM Length L Ch R = 1 ,71099   ,718,718,718
BEGIN DESCRIPTION:
Mapping XS fb5d8031
END DESCRIPTION:
XS GIS Cut Line= 3
      2603007.08     13397093.06      2602708.47      13395877.8
      2602098.72      13395448.2
#Sta/Elev= 30
  3760.2   74.12  4378.9   72.38  4571.7   69.41    4659   67.25  4705.6   66.71
  4841.1   63.07  4870.3   60.63  4890.9   58.05  4924.2   52.88  4932.1    51.1
  4952.7   50.05  4958.2   41.73  4959.2   41.23  5007.9   41.23  5008.9   41.73
  5010.5   49.18  5023.6   48.59  5029.7   50.16  5038.4   50.13  5048.1   51.63
  5074.1   54.24  5080.2   56.17  5088.9   56.92  5101.5   59.73  5130.7   62.99
  5138.2   62.89  5187.3    66.1  5216.7   67.23  5368.4   70.47  5757.5   71.61
#Mann= 6 ,-1 , 0
  3760.2     .05       0    4659     .07       0  4958.2     .05       0
  5008.9     .07       0  5048.1     .07       0  5216.7     .05       0
Bank Sta=4958.2,5008.9
XS Rating Curve= 0 ,0
Exp/Cntr=0.3,0.1

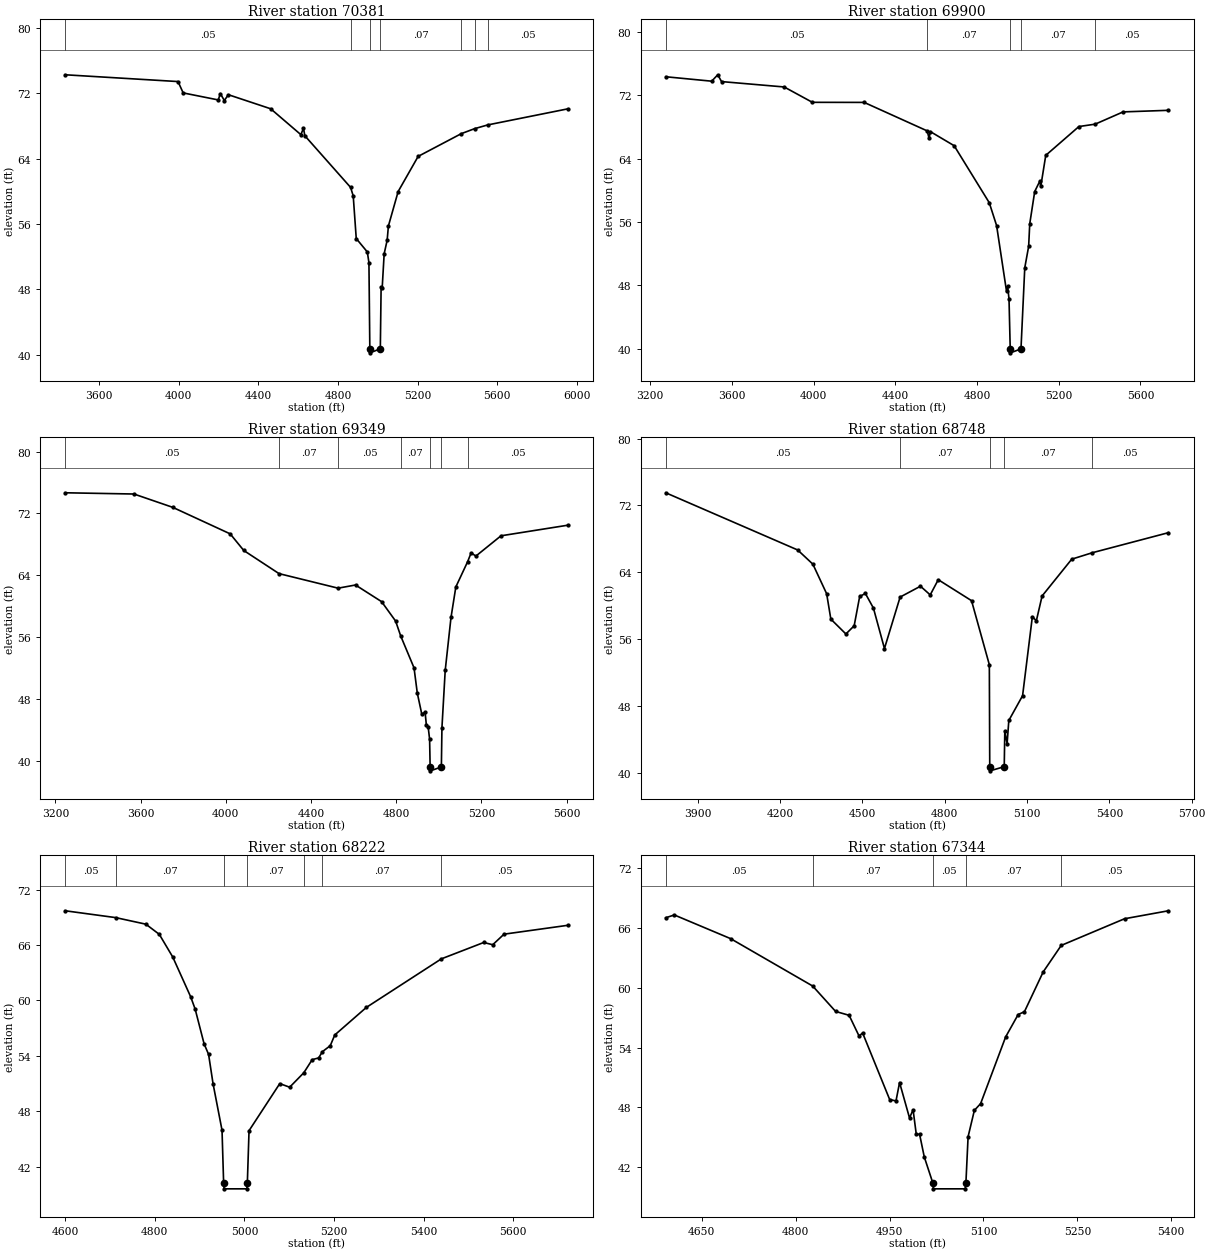
Type RM Length L Ch R = 1 ,70381   ,481,481,481
BEGIN DESCRIPTION:
Mapping XS 1dd57d5f
END DESCRIPTION:
XS GIS Cut Line= 3
      2603111.24     13397225.06      2603340.41     13395711.13
      2603687.63     13394780.58
#Sta/Elev= 30
    3430   74.26  3996.4   73.43  4022.4   72.04  4198.7   71.18  4208.8   71.96
  4229.1   71.11  4249.3   71.82  4461.7    70.1  4613.4   66.93  4626.5   67.71
  4633.6   66.79  4863.3   60.47  4876.4   59.43  4891.6   54.21  4947.2   52.57
  4955.3   51.26  4959.8   40.72  4960.9   40.22  5012.5   40.72  5016.5   48.29
  5021.8   48.13  5031.8   52.35  5046.8      54  5053.1   55.75  5102.1   59.97
  5202.5   64.27    5419   67.05  5485.5   67.66  5551.7   68.12  5954.4   70.09
#Mann= 7 ,-1 , 0
    3430     .05       0  4863.3     .07       0  4959.8     .05       0
  5012.5     .07       0    5419     .05       0  5485.5     .07       0
  5551.7     .05       0
Bank Sta=4959.8,5012.5
XS Rating Curve= 0 ,0
Exp/Cntr=0.3,0.1

Type RM Length L Ch R = 1 ,69900   ,551,551,551
BEGIN DESCRIPTION:
Mapping XS 7b9db32f
END DESCRIPTION:
XS GIS Cut Line= 3
      2603187.63     13397329.22      2603750.14     13395898.63
      2604089.71     13395039.29
#Sta/Elev= 30
  3275.7   74.36  3500.7    73.8  3530.4   74.61  3548.9   73.75  3855.6   73.07
  3993.7   71.13  4247.3   71.12    4556   67.52  4565.4   66.56  4570.8   67.44
  4687.9   65.65  4859.8   58.45  4895.8   55.56  4944.5   47.24  4949.9   47.88
  4956.6   46.27  4962.5   39.98  4963.5   39.48  5015.2   39.98  5033.7   50.22
  5052.7   52.93  5058.1   55.79  5082.4   59.86  5106.8   61.14  5112.2   60.52
  5136.5   64.43  5298.8   68.07  5378.3   68.37  5515.2   69.92  5736.9   70.12
#Mann= 5 ,-1 , 0
  3275.7     .05       0    4556     .07       0  4962.5     .05       0
  5015.2     .07       0  5378.3     .05       0
Bank Sta=4962.5,5015.2
XS Rating Curve= 0 ,0
Exp/Cntr=0.3,0.1

Type RM Length L Ch R = 1 ,69349   ,601,601,601
BEGIN DESCRIPTION:
Mapping XS c231b815
END DESCRIPTION:
XS GIS Cut Line= 3
      2603340.41     13397454.19      2604125.14     13396183.35
      2604582.61     13395448.63
#Sta/Elev= 30
  3246.5   74.67    3569   74.51  3750.9   72.79  4020.7   69.36  4084.5   67.21
    4250   64.22  4527.2   62.34  4608.9   62.75  4731.3    60.6  4797.1   58.09
  4821.1   56.16  4883.6   52.04  4898.9   48.78  4920.2   46.03  4935.5   46.32
  4941.4   44.66  4950.2   44.35  4956.7   42.82  4959.2   39.23  4960.2   38.73
  5011.9   39.23  5014.6   44.32  5029.9    51.7  5057.1   58.55  5079.8    62.5
  5135.1   65.76  5151.5    66.9    5174   66.49  5291.8   69.11  5605.6   70.48
#Mann= 7 ,-1 , 0
  3246.5     .05       0    4250     .07       0  4527.2     .05       0
  4821.1     .07       0  4959.2     .05       0  5011.9     .07       0
  5135.1     .05       0
Bank Sta=4959.2,5011.9
XS Rating Curve= 0 ,0
Exp/Cntr=0.3,0.1

Type RM Length L Ch R = 1 ,68748   ,526,526,526
BEGIN DESCRIPTION:
Mapping XS b0343d95
END DESCRIPTION:
XS GIS Cut Line= 3
      2604090.41     13397669.46      2604159.86     13396829.19
      2604743.19     13396030.58
#Sta/Elev= 30
    3783    73.5  4263.9   66.65  4319.3   64.95  4369.5   61.41  4384.8   58.37
  4439.7   56.59  4469.8   57.57  4489.9   61.08  4510.7   61.44    4540   59.69
  4580.2   54.85  4637.3   61.01  4711.5   62.31    4747   61.27  4776.3   63.09
  4897.6   60.58  4962.5   52.91    4964    40.7  4965.1    40.2  5016.8    40.7
  5018.9   44.99  5027.3   43.45  5033.5   46.23  5083.7    49.2  5119.3   58.66
  5133.9   58.17  5154.8   61.14  5262.9   65.55  5337.8   66.32  5615.1   68.72
#Mann= 5 ,-1 , 0
    3783     .05       0  4637.3     .07       0    4964     .05       0
  5016.8     .07       0  5337.8     .05       0
Bank Sta=4964,5016.8
XS Rating Curve= 0 ,0
Exp/Cntr=0.3,0.1

Type RM Length L Ch R = 1 ,68222   ,878,878,878
BEGIN DESCRIPTION:
Mapping XS 21f4358c
END DESCRIPTION:
XS GIS Cut Line= 3
      2604757.08     13397225.03      2604757.08     13396850.02
      2604847.17     13396108.49
#Sta/Elev= 30
  4600.1    69.7  4712.9   68.96  4780.1   68.25  4810.1   67.15  4840.1    64.7
  4880.1    60.4  4890.1   59.07  4910.1   55.31  4920.1   54.17  4930.1   50.99
  4950.1   45.97  4953.7   40.23  4954.8   39.63  5005.5   39.63  5006.6   40.23
  5010.4   45.92    5079   51.01  5101.1   50.62  5132.6   52.18  5151.4    53.6
  5165.8   53.79  5174.1   54.46  5191.7   55.11  5201.8   56.27  5272.3   59.25
  5439.7    64.5  5534.2   66.27  5554.4   66.03  5579.6   67.17  5722.1   68.13
#Mann= 7 ,-1 , 0
  4600.1     .05       0  4712.9     .07       0  4953.7     .05       0
  5006.6     .07       0  5132.6      .1       0  5174.1     .07       0
  5439.7     .05       0
Bank Sta=4953.7,5006.6
XS Rating Curve= 0 ,0
Exp/Cntr=0.3,0.1

Type RM Length L Ch R = 1 ,67344   ,802,802,802
BEGIN DESCRIPTION:
KUY CREEK 71.0
END DESCRIPTION:
XS GIS Cut Line= 3
      2605274.99     13396975.01        2605475.       13396625.
        2605475.     13396225.03
#Sta/Elev= 30
  4592.3   67.05    4606   67.33    4696   64.95  4827.1   60.19  4863.7   57.64
  4885.3   57.25  4901.1   55.18  4906.9   55.47  4950.1   48.79  4960.2   48.65
  4965.9    50.5  4981.8   46.94  4987.5   47.76  4992.6    45.3  4997.9    45.3
  5005.4   43.02    5019   40.42    5020   39.82  5070.8   39.82  5071.9   40.42
  5075.4   45.06  5085.4    47.7  5095.4   48.38  5135.4   55.08  5155.4   57.33
  5165.4   57.61  5195.4   61.61  5224.2   64.27  5325.4   66.95  5395.4   67.75
#Mann= 5 ,-1 , 0
  4592.3     .05       0  4827.1     .07       0    5019     .05       0
  5071.9     .07       0  5224.2     .05       0
Bank Sta=5019,5071.9
XS Rating Curve= 0 ,0
Exp/Cntr=0.3,0.1

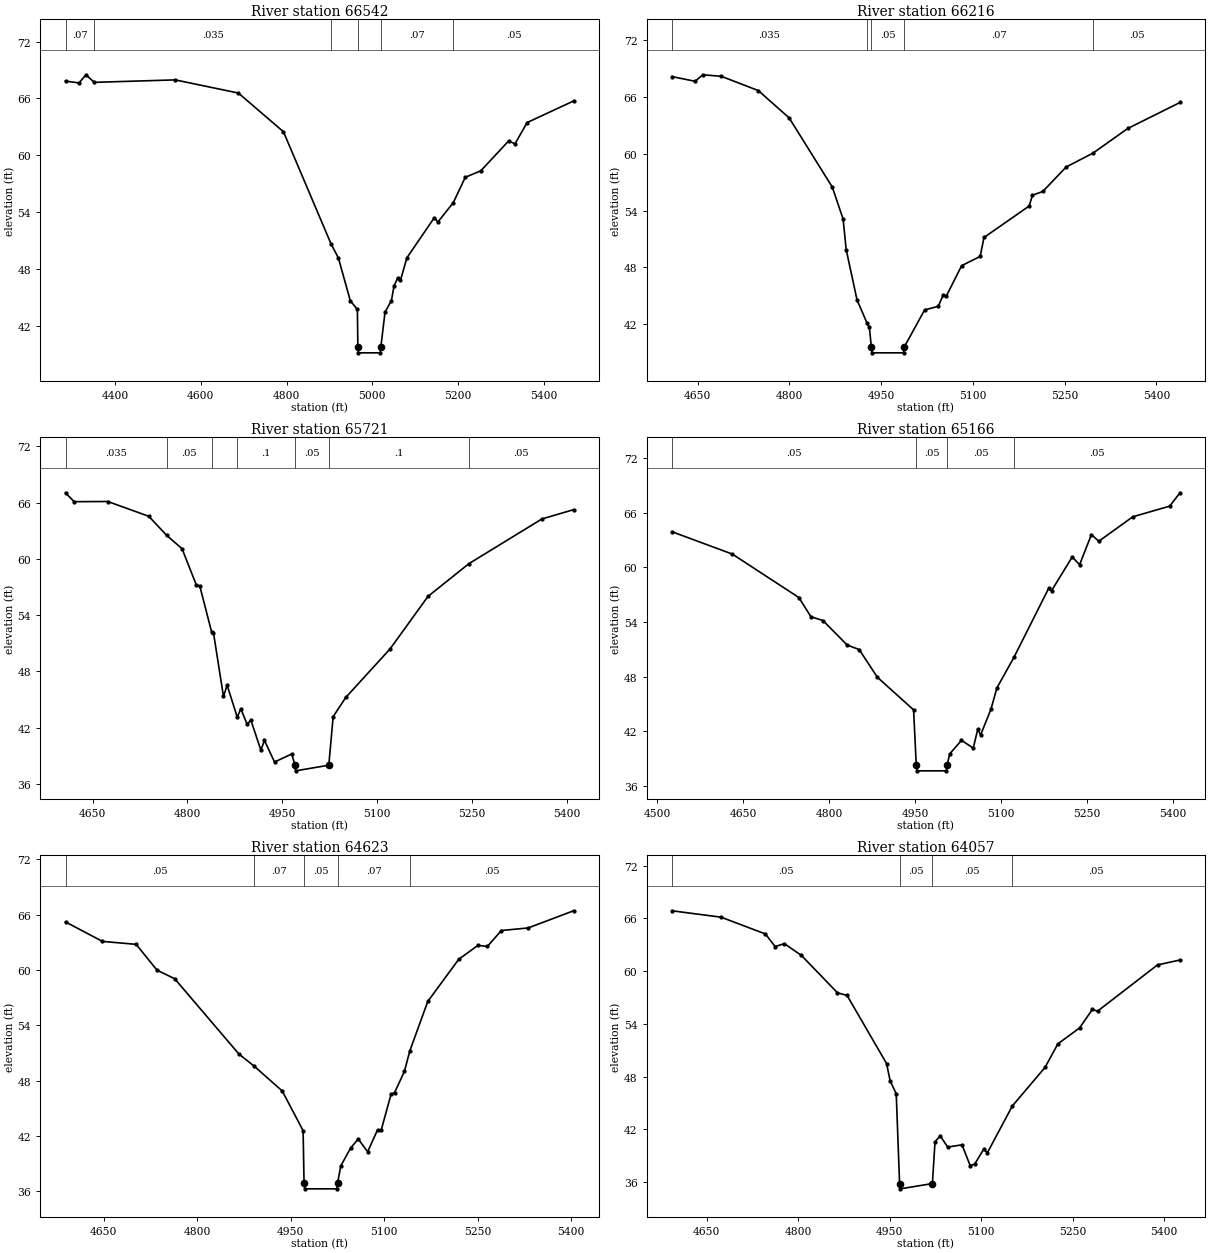
Type RM Length L Ch R = 1 ,66542   ,326,326,326
BEGIN DESCRIPTION:
KUY CREEK 70.0
END DESCRIPTION:
XS GIS Cut Line= 3
      2606853.07      13396961.4      2606215.46      13396636.1
      2605825.01     13396375.01
#Sta/Elev= 30
  4284.2   67.83  4315.7   67.64  4331.9    68.5  4351.2    67.7  4540.2   67.96
  4687.6   66.57  4792.8   62.48  4904.3   50.58  4920.9   49.16  4948.7   44.63
  4965.3    43.7  4966.4   39.72  4967.5   39.12  5018.9   39.12    5020   39.72
  5029.8   43.42  5044.8   44.65  5050.8    46.2  5059.8   47.06  5065.8   46.78
  5080.8   49.16  5144.9   53.41  5152.9   52.93    5189   54.98  5217.1   57.67
  5253.2   58.35  5318.1    61.5  5333.1   61.21  5361.4   63.45  5469.7   65.73
#Mann= 6 ,-1 , 0
  4284.2     .07       0  4351.2    .035       0  4904.3     .07       0
  4966.4     .05       0    5020     .07       0    5189     .05       0
Bank Sta=4966.4,5020
XS Rating Curve= 0 ,0
Exp/Cntr=0.3,0.1

Type RM Length L Ch R = 1 ,66216   ,495,495,495
BEGIN DESCRIPTION:
KUY CREEK 69.0
END DESCRIPTION:
XS GIS Cut Line= 3
      2606825.02       13396475.        2606425.       13396425.
      2606025.03     13396275.01
#Sta/Elev= 30
  4608.2   68.17    4646   67.67  4658.6   68.36  4688.8    68.2  4749.3   66.69
  4799.7    63.8  4870.2   56.48  4887.9    53.1  4892.9   49.88  4910.6   44.56
  4926.8   42.12  4930.7    41.7  4934.1   39.55  4935.2   38.95  4986.6   38.95
  4987.7   39.55  5021.1   43.49  5043.4   43.87  5051.4   45.06  5056.7   44.97
  5081.6   48.17  5111.9   49.15  5118.1   51.15    5192   54.48  5197.3   55.62
  5214.3   56.02  5252.5   58.61  5296.2   60.07  5353.1   62.68  5438.5   65.43
#Mann= 5 ,-1 , 0
  4608.2    .035       0  4926.8     .07       0  4934.1     .05       0
  4987.7     .07       0  5296.2     .05       0
Bank Sta=4934.1,4987.7
XS Rating Curve= 0 ,0
Exp/Cntr=0.3,0.1

Type RM Length L Ch R = 1 ,65721   ,555,555,555
BEGIN DESCRIPTION:
KUY CREEK 68.0
END DESCRIPTION:
XS GIS Cut Line= 3
      2606824.97     13396224.98        2606475.       13396025.
      2606074.97       13396025.
#Sta/Elev= 30
  4607.3   67.04  4620.9   66.09  4674.2   66.11    4739   64.53  4767.4   62.49
  4791.5   61.08  4813.9   57.25  4819.6    57.1  4838.1   52.24  4841.2   52.13
    4857   45.33  4862.8   46.53  4878.8   43.12  4884.4   44.02  4894.5   42.35
  4900.2   42.83  4916.1   39.61  4921.8   40.64  4937.7   38.34    4965    39.2
  4969.9      38    4971    37.4  5023.5      38  5030.4   43.18  5050.4   45.23
  5120.4    50.4  5180.4      56  5244.9   59.48  5360.4   64.25  5410.4   65.24
#Mann= 7 ,-1 , 0
  4607.3    .035       0  4767.4     .05       0  4838.1     .12       0
  4878.8      .1       0  4969.9     .05       0  5023.5      .1       0
  5244.9     .05       0
Bank Sta=4969.9,5023.5
XS Rating Curve= 0 ,0
Exp/Cntr=0.3,0.1

Type RM Length L Ch R = 1 ,65166   ,543,543,543
BEGIN DESCRIPTION:
KUY CREEK 67.0
END DESCRIPTION:
XS GIS Cut Line= 3
      2606775.01     13396025.02        2606625.       13395575.
      2606224.97     13395474.99
#Sta/Elev= 30
  4525.6   63.92    4631   61.46    4747   56.69  4768.1   54.58  4789.1   54.16
  4831.3   51.47  4852.4   50.97    4884   47.93  4947.3   44.34    4952   38.24
  4953.1   37.64  5004.6   37.64  5005.7   38.24  5010.3    39.5  5030.9   40.99
  5051.5   40.14  5059.2    42.2  5064.4    41.6  5082.4   44.42  5092.7   46.75
  5122.6   50.13  5182.9   57.68  5188.1   57.44  5224.2   61.15    5237   60.29
  5257.7   63.61  5270.5   62.87  5329.8   65.56  5394.2   66.73  5412.3    68.2
#Mann= 4 ,-1 , 0
  4525.6     .05       0    4952     .05       0  5005.7     .05       0
  5122.6     .05       0
Bank Sta=4952,5005.7
XS Rating Curve= 0 ,0
Exp/Cntr=0.3,0.1

Type RM Length L Ch R = 1 ,64623   ,566,566,566
BEGIN DESCRIPTION:
KUY CREEK 66.0
END DESCRIPTION:
XS GIS Cut Line= 3
      2607175.01     13395825.03        2607075.       13395425.
      2606874.98     13395074.96
#Sta/Elev= 30
  4588.5    65.2  4647.8   63.09  4701.9   62.77  4735.4   59.97  4763.8   59.04
  4866.8   50.88  4891.6   49.55  4936.4   46.87  4969.9   42.57  4971.4   36.86
  4972.5   36.26    5024   36.26  5025.1   36.86  5030.4   38.75  5046.2   40.69
  5058.4   41.66  5073.5   40.28  5089.4   42.66  5095.1   42.59    5111    46.5
  5116.7   46.69  5132.6   49.01    5141   51.18    5170   56.58  5219.7   61.15
  5250.6   62.66  5265.7   62.54  5288.1   64.27  5331.2   64.55    5404   66.41
#Mann= 5 ,-1 , 0
  4588.5     .05       0  4891.6     .07       0  4971.4     .05       0
  5025.1     .07       0    5141     .05       0
Bank Sta=4971.4,5025.1
XS Rating Curve= 0 ,0
Exp/Cntr=0.3,0.1

Type RM Length L Ch R = 1 ,64057   ,518,518,518
BEGIN DESCRIPTION:
KUY CREEK 65.0
END DESCRIPTION:
XS GIS Cut Line= 3
      2607924.98     13395424.99        2607575.       13395225.
        2607225.       13394975.
#Sta/Elev= 30
    4593   66.86  4673.6   66.13  4746.3   64.22  4762.1   62.79  4777.3   63.12
  4805.3   61.78  4864.4   57.53  4880.2   57.22    4945   49.47  4950.7   47.53
  4960.8   46.03  4966.3   35.82  4967.4   35.22  5020.1   35.82  5024.4   40.58
    5033   41.24  5045.2   39.97  5068.6   40.23  5082.1   37.86  5089.5   38.04
  5104.2   39.73  5110.4   39.34  5151.2   44.65    5205   49.05  5225.9   51.72
  5261.5   53.53  5282.4   55.63    5291   55.44  5389.3    60.7  5426.2   61.26
#Mann= 4 ,-1 , 0
    4593     .05       0  4966.3     .05       0  5020.1     .05       0
  5151.2     .05       0
Bank Sta=4966.3,5020.1
XS Rating Curve= 0 ,0
Exp/Cntr=0.3,0.1

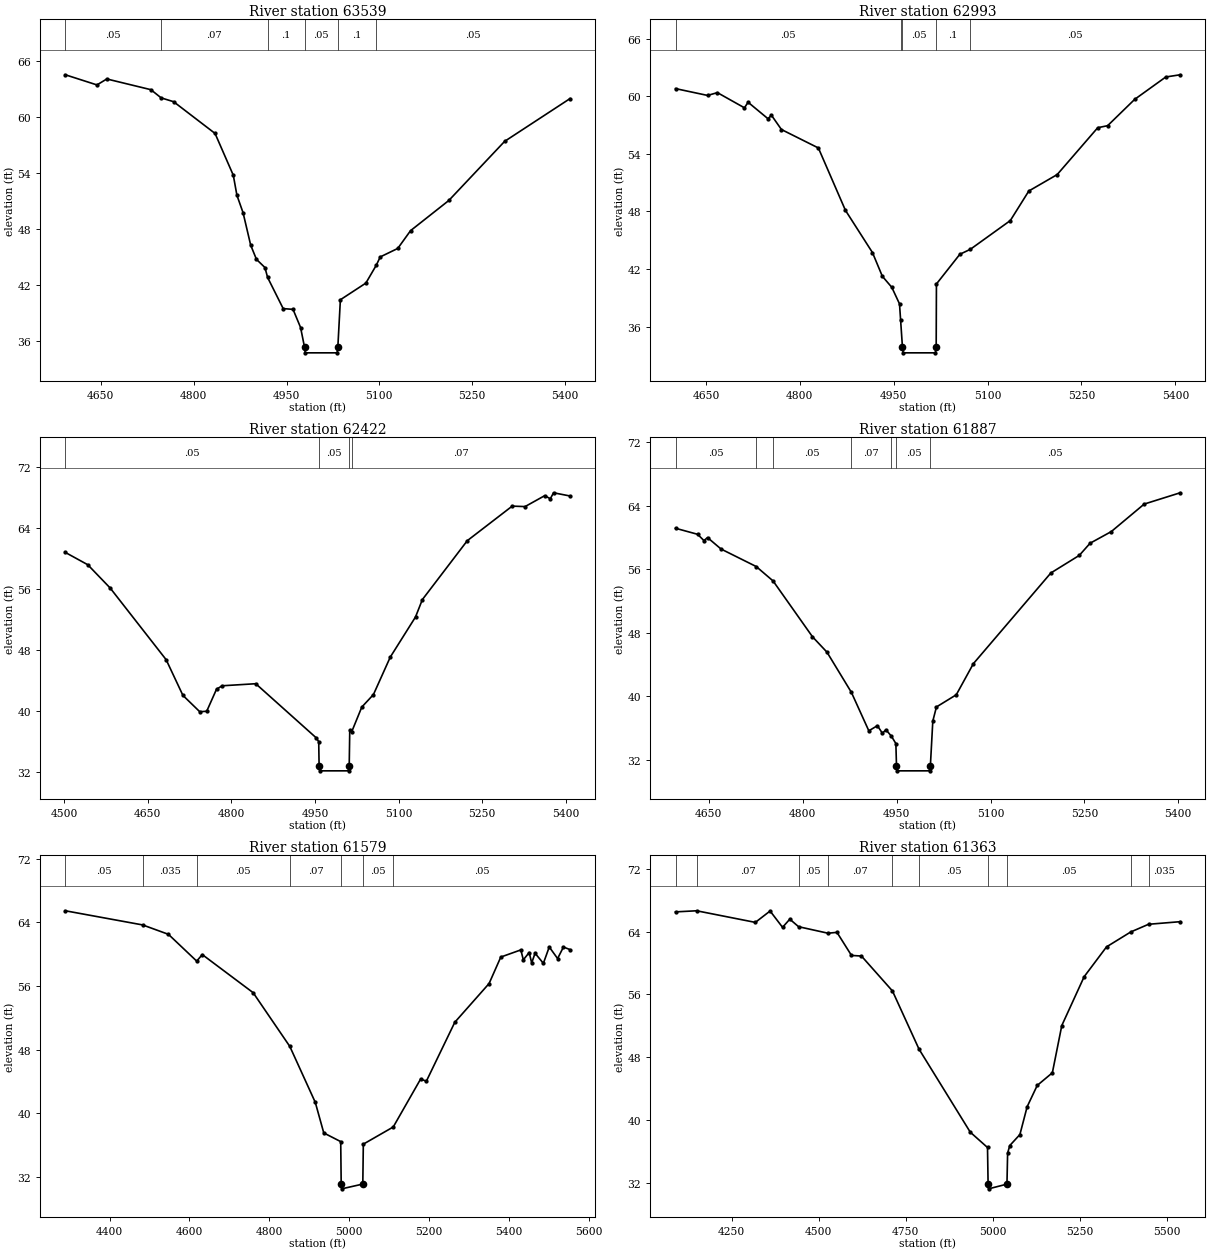
Type RM Length L Ch R = 1 ,63539   ,546,546,546
BEGIN DESCRIPTION:
KUY CREEK 64.0
END DESCRIPTION:
XS GIS Cut Line= 3
      2608175.02     13395025.01        2607825.       13394825.
      2607425.05     13394725.01
#Sta/Elev= 30
  4592.6   64.56  4643.7   63.47  4659.6   64.11  4730.8   62.96  4747.4   62.08
  4767.5   61.67  4834.5   58.26    4864   53.77  4869.8   51.63  4879.8   49.74
  4892.1   46.26  4901.4   44.74  4915.1   43.86  4919.4    42.8  4944.6   39.45
  4960.5   39.37  4972.7   37.42  4979.1    35.3  4980.2    34.7  5031.8    34.7
  5032.9    35.3    5037    40.4  5078.2   42.19  5095.1   44.12  5101.4      45
  5129.7   45.91  5150.4   47.82  5212.2   51.06  5302.4   57.41    5408      62
#Mann= 6 ,-1 , 0
  4592.6     .05       0  4747.4     .07       0  4919.4      .1       0
  4979.1     .05       0  5032.9      .1       0  5095.1     .05       0
Bank Sta=4979.1,5032.9
XS Rating Curve= 0 ,0
Exp/Cntr=0.3,0.1

Type RM Length L Ch R = 1 ,62993   ,571,571,571
BEGIN DESCRIPTION:
KUY CREEK 63.0
END DESCRIPTION:
XS GIS Cut Line= 3
        2608325.       13394525.        2607975.       13394325.
      2607625.02     13394125.01
#Sta/Elev= 30
  4601.5   60.79  4652.6   60.08  4668.4   60.37  4711.6   58.79  4717.4   59.37
  4749.1   57.66  4754.8   58.01  4770.7   56.53  4829.7   54.61  4872.9   48.12
  4916.1   43.72  4931.9   41.25    4947    40.1  4959.3   38.38  4961.1   36.66
    4964   33.88  4965.1   33.28  5016.8   33.28  5017.9   33.88  5018.3   40.45
  5055.7   43.54  5072.5   44.06  5136.3   47.05  5165.9   50.13  5211.2   51.84
    5276   56.72  5291.8   56.93    5335   59.67  5384.7      62  5407.7   62.23
#Mann= 5 ,-1 , 0
  4601.5     .05       0  4961.1      .1       0    4964     .05       0
  5017.9      .1       0  5072.5     .05       0
Bank Sta=4964,5017.9
XS Rating Curve= 0 ,0
Exp/Cntr=0.3,0.1

Type RM Length L Ch R = 1 ,62422   ,535,535,535
BEGIN DESCRIPTION:
KUY CREEK 62.0
END DESCRIPTION:
XS GIS Cut Line= 3
      2608574.97       13393875.        2608075.       13393825.
      2607724.98     13393624.99
#Sta/Elev= 30
  4502.1   60.75  4542.3   59.14  4582.5   56.09    4683   46.69  4713.1   42.01
  4743.3   39.87  4755.8   39.93  4773.4   42.82  4783.5   43.27  4843.8   43.54
  4951.8   36.48  4956.8   35.95  4957.5   32.72  4958.6   32.12  5010.3   32.12
  5011.5   32.72  5012.5   37.41  5016.1   37.26  5034.1   40.48    5055   42.12
  5085.2   47.03  5130.5   52.29  5142.8   54.57  5223.4   62.29    5304   66.82
  5327.1   66.76  5362.3   68.19  5372.4   67.79  5378.2   68.57  5407.7   68.15
#Mann= 4 ,-1 , 0
  4502.1     .05       0  4957.5     .05       0  5011.5     .05       0
  5016.1     .07       0
Bank Sta=4957.5,5011.5
XS Rating Curve= 0 ,0
Exp/Cntr=0.3,0.1

Type RM Length L Ch R = 1 ,61887   ,308,308,308
BEGIN DESCRIPTION:
KUY CREEK 61.0
END DESCRIPTION:
XS GIS Cut Line= 3
      2608625.01     13393825.01        2608425.       13393475.
      2608075.04     13393275.02
#Sta/Elev= 30
  4596.8   61.14  4632.1   60.38  4642.2   59.59  4647.9   59.97  4669.5   58.53
  4725.7   56.33  4752.6   54.52  4815.6    47.5  4838.7   45.57  4877.7   40.52
  4905.6   35.68  4919.3   36.33  4927.2   35.38    4933   35.81  4941.7      35
  4948.8   34.08  4949.8   31.25  4950.9   30.65  5002.8   30.65  5003.9   31.25
  5007.8    36.9  5013.6   38.68  5045.3   40.21  5072.6   44.12  5196.4   55.52
  5241.8   57.73  5259.1   59.26  5292.9   60.72  5345.5   64.18    5403    65.6
#Mann= 7 ,-1 , 0
  4596.8     .05       0  4725.7     .07       0  4752.6     .05       0
  4877.7     .07       0  4941.7     .05       0  4949.8     .05       0
  5003.9     .05       0
Bank Sta=4949.8,5003.9
XS Rating Curve= 0 ,0
Exp/Cntr=0.3,0.1

Type RM Length L Ch R = 1 ,61579   ,216,216,216
BEGIN DESCRIPTION:
Mapping XS ba27f4f4
END DESCRIPTION:
XS GIS Cut Line= 3
      2609150.86     13393803.96      2608616.11     13393269.21
      2608206.42     13392970.62
#Sta/Elev= 30
  4289.4   65.47  4482.9   63.69  4547.4   62.51  4618.2   59.14  4632.2   59.96
  4759.5   55.17  4851.3   48.41  4915.1   41.37  4936.3   37.53  4978.7   36.44
  4979.9    31.1    4981    30.5    5034    31.1  5035.3   36.12  5110.2   38.28
  5178.5   44.29  5193.2   44.05  5264.3   51.45  5350.1   56.32  5379.4   59.65
  5429.6   60.55  5435.8    59.3  5450.5   60.22  5456.7   58.91  5465.2   60.13
    5486   58.86  5500.7   60.92  5521.6   59.46  5536.2   60.91  5552.6   60.59
#Mann= 7 ,-1 , 0
  4289.4     .05       0  4482.9    .035       0  4618.2     .05       0
  4851.3     .07       0  4979.9     .05       0    5034     .05       0
  5110.2     .05       0
Bank Sta=4979.9,5034
XS Rating Curve= 0 ,0
Exp/Cntr=0.3,0.1

Type RM Length L Ch R = 1 ,61363   ,285,285,285
BEGIN DESCRIPTION:
Mapping XS ccff8717
END DESCRIPTION:
XS GIS Cut Line= 3
      2609504.98     13393727.53      2608803.61     13393151.15
       2608374.5     13392818.94
#Sta/Elev= 30
  4088.7   66.51  4149.3   66.65  4318.1   65.17  4360.5   66.62  4396.3   64.54
  4417.1   65.58  4442.4   64.62  4526.9   63.79  4552.7    63.9  4594.4   60.96
  4623.1   60.88  4712.2   56.43  4788.6   49.01  4935.9   38.43  4985.4   36.48
  4987.1   31.81  4988.3   31.21  5041.3   31.81  5043.2   35.77  5049.5   36.73
  5078.5   38.13  5099.3   41.67  5128.3   44.39  5171.8      46  5198.9   52.02
  5263.2   58.25  5327.5   62.05  5397.1   63.95  5448.3   64.93  5539.2   65.26
#Mann= 10 ,-1 , 0
  4088.7     .05       0  4149.3     .07       0  4442.4     .05       0
  4526.9     .07       0  4712.2    .035       0  4788.6     .05       0
  4987.1    .035       0  5041.3     .05       0  5397.1     .07       0
  5448.3    .035       0
Bank Sta=4987.1,5041.3
XS Rating Curve= 0 ,0
Exp/Cntr=0.3,0.1