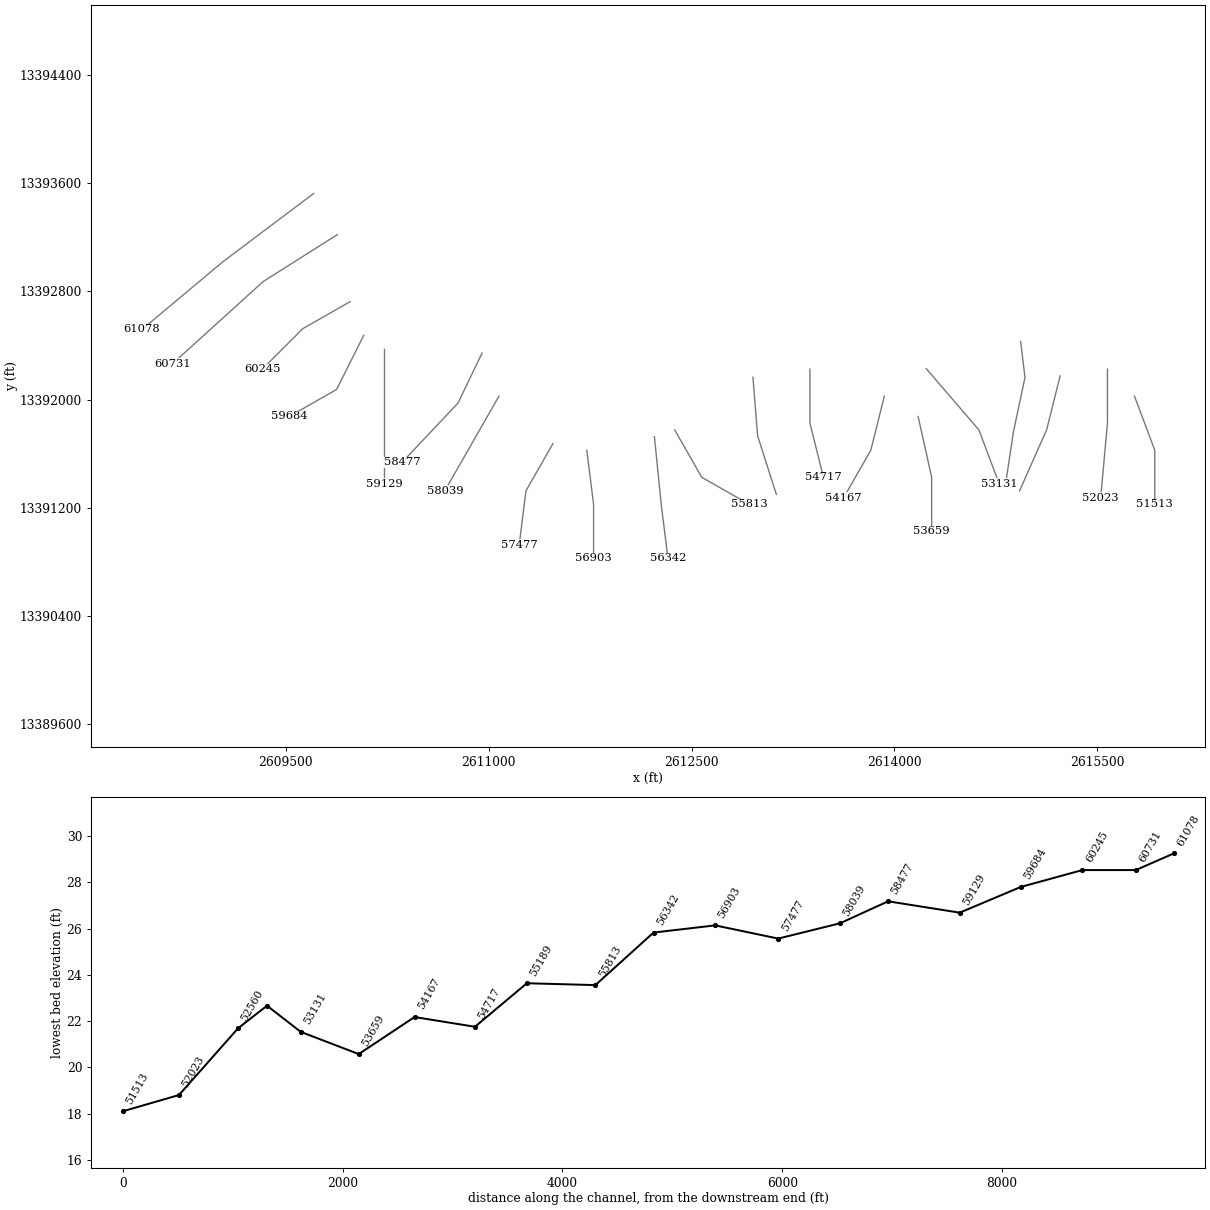
HEC-RAS study KUY CREEK.prj: KUY CREEK Base Level Engineering

--- KUY CREEK.g01 (geometry) --- (continued)

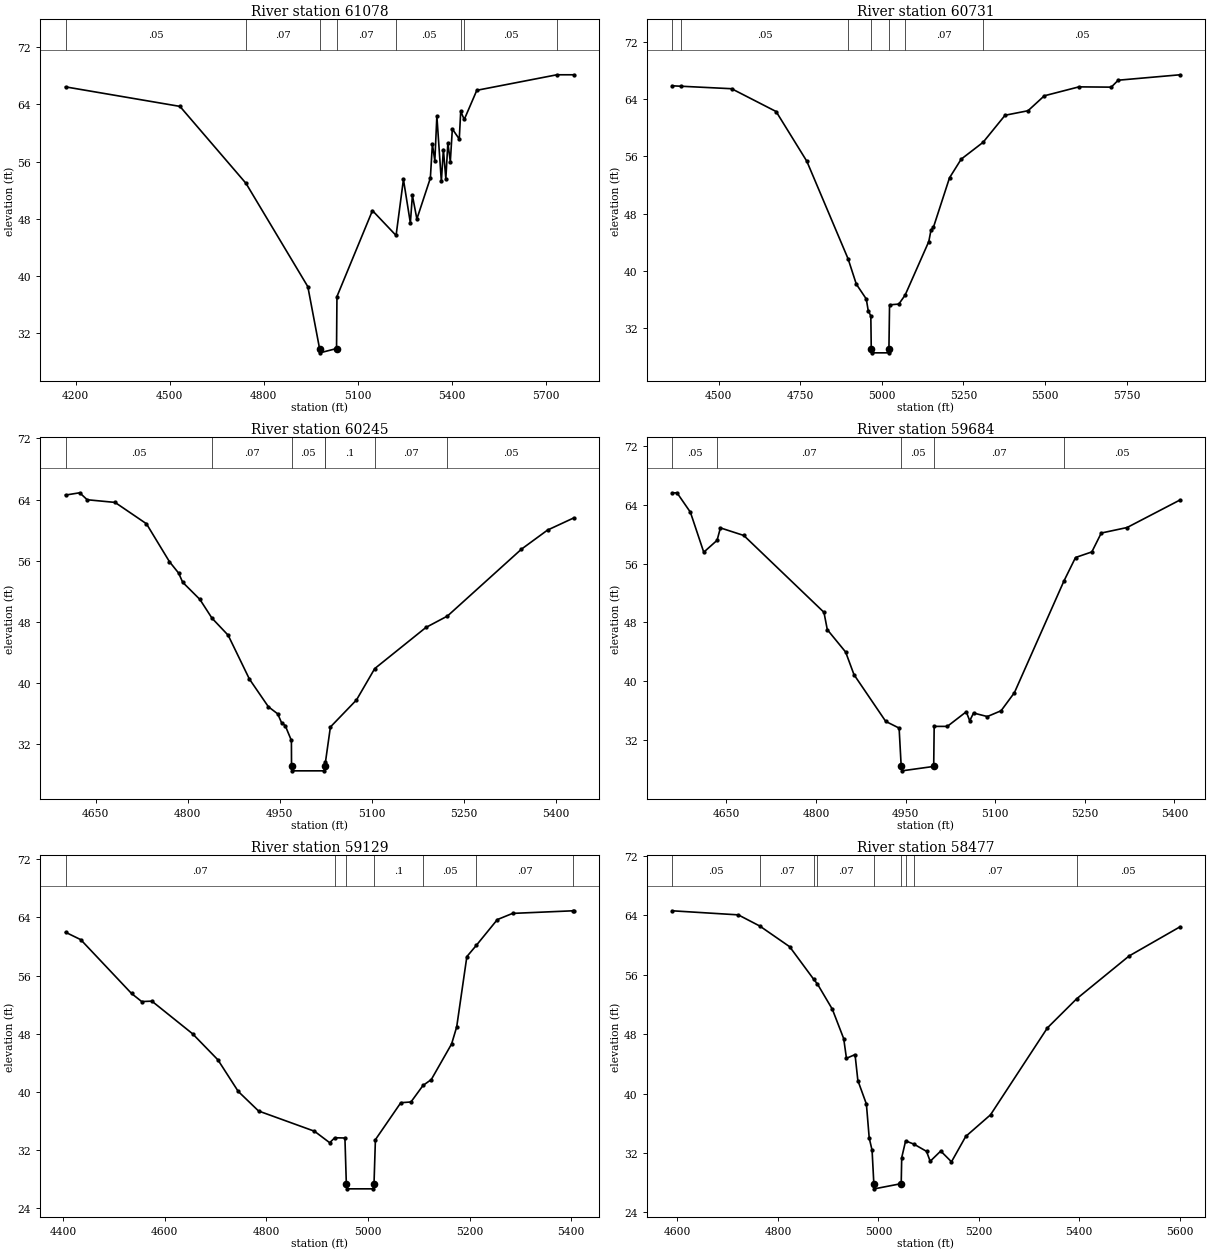
Type RM Length L Ch R = 1 ,61078   ,347,347,347
BEGIN DESCRIPTION:
Mapping XS 84c18319
END DESCRIPTION:
XS GIS Cut Line= 3
      2609706.42     13393526.18      2609032.78     13393019.21
      2608436.01     13392519.59
#Sta/Elev= 30
    4168   66.44  4533.2   63.71    4744   52.95  4941.4    38.5  4978.8   29.85
    4980   29.25    5033   29.85  5034.3   37.12  5147.6   49.14    5223   45.66
  5246.5   53.49  5268.6   47.41  5275.1   51.26  5289.4   47.97  5332.4   53.68
  5338.9   58.43  5346.7    56.1  5353.2   62.35  5367.5   53.22    5374   57.68
  5381.8   53.59  5388.3   58.61  5396.1   55.98  5402.6   60.55  5424.7   59.14
  5429.3   63.01  5440.6   61.88  5480.7   65.96  5736.2   68.13  5789.4   68.13
#Mann= 8 ,-1 , 0
    4168     .05       0    4744     .07       0  4978.8     .05       0
    5033     .07       0    5223     .05       0  5429.3     .07       0
  5440.6     .05       0  5736.2     .07       0
Bank Sta=4978.8,5033
XS Rating Curve= 0 ,0
Exp/Cntr=0.3,0.1

Type RM Length L Ch R = 1 ,60731   ,486,486,486
BEGIN DESCRIPTION:
Mapping XS 85aded63
END DESCRIPTION:
XS GIS Cut Line= 3
      2609879.98     13393220.58      2609331.39     13392873.38
      2608658.92      13392263.3
#Sta/Elev= 30
  4356.8   65.88  4383.5   65.82  4539.6   65.47    4676   62.28  4770.1   55.33
  4896.7   41.67  4921.8   38.14  4952.4   36.06  4958.3   34.43  4966.3   33.69
  4967.6   29.13  4968.7   28.53  5020.7   28.53  5021.8   29.13  5023.7   35.24
  5052.1   35.35  5071.4    36.6    5144    44.1  5150.7   45.69  5158.2   46.09
  5207.5   53.01  5243.3   55.62  5310.3   57.97  5377.8   61.76  5448.1   62.39
  5498.1   64.48  5604.2   65.73  5703.3   65.69  5724.5   66.66    5914   67.42
#Mann= 7 ,-1 , 0
  4356.8     .07       0  4383.5     .05       0  4896.7      .1       0
  4967.6     .05       0  5021.8      .1       0  5071.4     .07       0
  5310.3     .05       0
Bank Sta=4967.6,5021.8
XS Rating Curve= 0 ,0
Exp/Cntr=0.3,0.1

Type RM Length L Ch R = 1 ,60245   ,561,561,561
BEGIN DESCRIPTION:
KUY CREEK 58.0
END DESCRIPTION:
XS GIS Cut Line= 3
      2609975.03     13392725.01        2609625.       13392525.
        2609325.       13392225.
#Sta/Elev= 30
  4601.1   64.59  4624.2   64.89  4636.4   63.98  4681.8   63.63  4732.9   60.84
  4770.3   55.89  4785.4   54.38  4791.9   53.19    4820   50.94  4839.6    48.5
    4866   46.26  4900.6   40.53  4931.5   36.91  4946.7   35.98  4953.1    34.8
  4958.9   34.45    4969    32.5  4969.2   29.13  4970.3   28.53  5022.4   28.53
  5023.5   29.13  5024.4   29.64  5032.5   34.26    5075    37.8  5104.7    41.9
  5188.1   47.28  5223.1   48.77  5343.7   57.52  5386.1   60.01  5428.5   61.59
#Mann= 7 ,-1 , 0
  4601.1     .05       0  4839.6     .07       0  4969.2     .05       0
  5023.5     .07       0  5024.4      .1       0  5104.7     .07       0
  5223.1     .05       0
Bank Sta=4969.2,5023.5
XS Rating Curve= 0 ,0
Exp/Cntr=0.3,0.1

Type RM Length L Ch R = 1 ,59684   ,555,555,555
BEGIN DESCRIPTION:
KUY CREEK 57.0
END DESCRIPTION:
XS GIS Cut Line= 3
      2610075.02     13392475.04        2609875.       13392075.
      2609524.98     13391874.99
#Sta/Elev= 30
  4559.1   65.62  4567.5   65.65  4589.9   63.01  4612.3   57.56  4634.6   59.18
  4640.2   60.87  4679.3   59.84  4813.5   49.38  4819.1   47.02  4849.8   43.97
  4863.8   40.89  4916.9   34.53  4939.3   33.62  4942.8    28.4    4944    27.8
  4997.2    28.4    4998   33.85    5020   33.85  5051.7   35.84  5057.5   34.61
  5063.9   35.67    5087   35.19    5110   35.98  5132.3   38.44  5215.2   53.64
  5234.6   56.84  5261.9    57.6  5277.7   60.17  5320.9   60.92  5409.5   64.67
#Mann= 5 ,-1 , 0
  4559.1     .05       0  4634.6     .07       0  4942.8     .05       0
  4997.2     .07       0  5215.2     .05       0
Bank Sta=4942.8,4997.2
XS Rating Curve= 0 ,0
Exp/Cntr=0.3,0.1

Type RM Length L Ch R = 1 ,59129   ,652,652,652
BEGIN DESCRIPTION:
KUY CREEK 56.0
END DESCRIPTION:
XS GIS Cut Line= 3
        2610225.     13392374.97        2610225.       13391775.
        2610225.     13391374.97
#Sta/Elev= 30
  4404.6   61.96  4434.6   60.94  4534.6   53.54  4554.6   52.43  4574.6   52.49
  4654.6   48.01  4704.6   44.42  4744.6   40.08  4784.6   37.39  4894.6   34.61
  4924.6   33.03  4934.5   33.71  4954.6   33.68  4957.4   27.29  4958.5   26.69
  5010.6   26.69  5011.8   27.29  5014.6   33.45  5064.6   38.53  5084.6   38.63
  5108.3    40.9  5124.6   41.71  5164.6   46.61  5174.6   48.95  5194.6   58.61
  5213.5   60.18  5254.6    63.7  5284.6   64.55  5404.3   64.91  5404.6   64.91
#Mann= 7 ,-1 , 0
  4404.6     .07       0  4934.5      .1       0  4957.4     .05       0
  5011.8      .1       0  5108.3     .05       0  5213.5     .07       0
  5404.3     .05       0
Bank Sta=4957.4,5011.8
XS Rating Curve= 0 ,0
Exp/Cntr=0.3,0.1

Type RM Length L Ch R = 1 ,58477   ,438,438,438
BEGIN DESCRIPTION:
KUY CREEK 55.0
END DESCRIPTION:
XS GIS Cut Line= 3
      2610950.24     13392343.96      2610771.99     13391973.63
      2610360.02     13391536.73
#Sta/Elev= 30
    4589   64.63    4721   64.08  4763.7   62.58  4823.3   59.79  4871.1   55.41
  4878.7   54.76  4908.3   51.37  4930.9   47.41  4936.4   44.76  4953.5   45.26
  4959.1   41.77  4976.1    38.6  4981.7   34.03  4987.4   32.38  4990.9   27.88
    4992   27.18  5045.4   27.88  5046.4   31.38  5054.2   33.64    5071   33.19
  5095.8   32.23  5103.1   30.89  5124.1   32.27  5145.5   30.82  5173.9   34.24
  5223.2   37.15  5336.5   48.86  5394.8   52.78  5499.1   58.54  5600.5   62.47
#Mann= 9 ,-1 , 0
    4589     .05       0  4763.7     .07       0  4871.1     .05       0
  4878.7     .07       0  4990.9     .05       0  5045.4     .07       0
  5054.2      .1       0    5071     .07       0  5394.8     .05       0
Bank Sta=4990.9,5045.4
XS Rating Curve= 0 ,0
Exp/Cntr=0.3,0.1

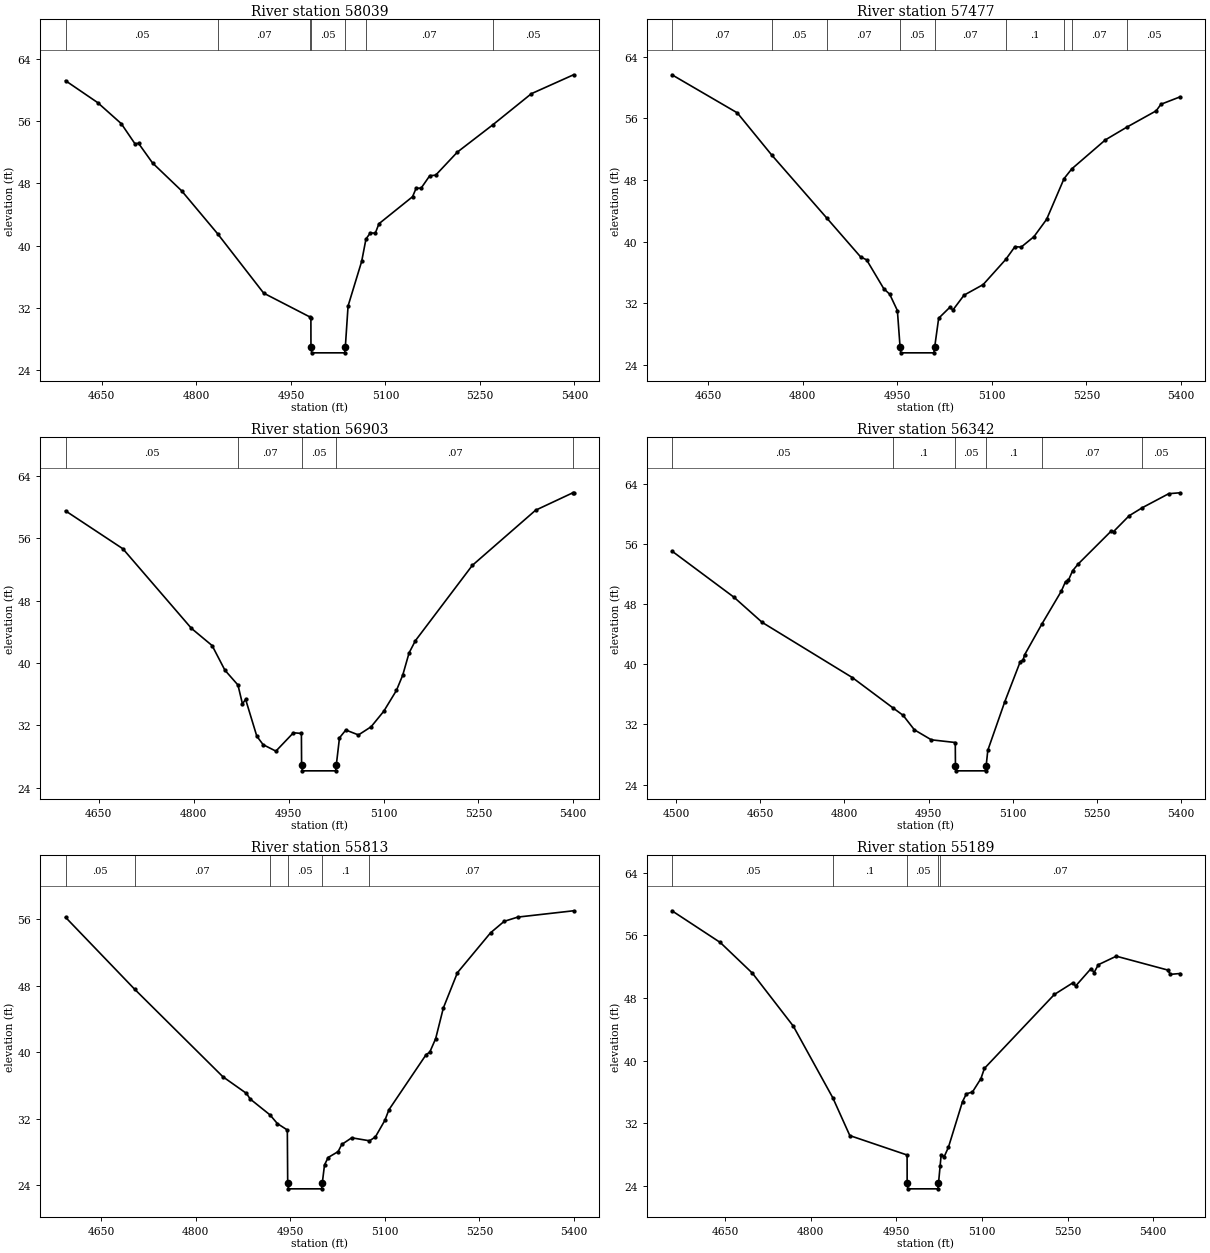
Type RM Length L Ch R = 1 ,58039   ,562,562,562
BEGIN DESCRIPTION:
KUY CREEK 54.0
END DESCRIPTION:
XS GIS Cut Line= 3
      2611074.99     13392024.98        2610875.       13391675.
        2610675.       13391325.
#Sta/Elev= 30
  4592.3    61.2  4643.4   58.38  4680.8   55.68  4702.4   53.11  4708.2   53.15
  4730.5   50.62  4776.6   47.05  4833.5   41.55  4906.8    33.9  4980.6   30.82
  4981.7   30.76  4981.8   26.93    4983   26.23  5035.2   26.23  5036.3   26.93
  5040.7   32.25  5062.3   37.99  5069.1   40.86    5076   41.64  5083.9   41.61
  5089.7   42.82    5143   46.29  5148.7   47.38  5156.6   47.39  5170.3   48.99
  5179.7   49.06  5214.2   52.03  5269.9    55.5  5331.6   59.53  5398.5   61.96
#Mann= 7 ,-1 , 0
  4592.3     .05       0  4833.5     .07       0  4980.6      .1       0
  4981.8     .05       0  5036.3      .1       0  5069.1     .07       0
  5269.9     .05       0
Bank Sta=4981.8,5036.3
XS Rating Curve= 0 ,0
Exp/Cntr=0.3,0.1

Type RM Length L Ch R = 1 ,57477   ,574,574,574
BEGIN DESCRIPTION:
KUY CREEK 53.0
END DESCRIPTION:
XS GIS Cut Line= 3
      2611474.98     13391674.96        2611275.       13391325.
        2611225.     13390924.98
#Sta/Elev= 30
  4592.4   61.67    4696   56.73  4750.5   51.27  4838.6   43.02  4891.8   38.02
  4901.2   37.65  4928.5    33.9  4937.9   33.18  4950.1   31.06  4954.4   26.27
  4955.5   25.57    5008   25.57  5009.2   26.27  5015.6   30.06  5033.3   31.48
  5038.3   31.14  5055.9   33.06  5086.2   34.43  5122.1    37.7  5136.6   39.35
  5146.6    39.3  5166.8   40.65  5186.9    42.9  5214.6   48.19  5226.8   49.45
  5280.2   53.22  5314.4   54.88  5360.8   56.99  5368.3   57.84  5398.6    58.8
#Mann= 9 ,-1 , 0
  4592.4     .07       0  4750.5     .05       0  4838.6     .07       0
  4954.4     .05       0  5009.2     .07       0  5122.1      .1       0
  5214.6     .05       0  5226.8     .07       0  5314.4     .05       0
Bank Sta=4954.4,5009.2
XS Rating Curve= 0 ,0
Exp/Cntr=0.3,0.1

Type RM Length L Ch R = 1 ,56903   ,561,561,561
BEGIN DESCRIPTION:
KUY CREEK 52.0
END DESCRIPTION:
XS GIS Cut Line= 3
        2611725.     13391625.03        2611775.       13391225.
        2611775.     13390825.04
#Sta/Elev= 30
  4597.3   59.52    4688   54.65  4796.4   44.43  4829.1   42.22  4849.3   39.06
  4869.9   37.16    4877   34.74    4882   35.32  4899.7   30.59  4909.7    29.5
  4929.9   28.67  4957.6   31.03  4970.2   30.94  4970.5   26.84  4971.7   26.14
  5024.2   26.14  5025.3   26.84  5030.4   30.38  5040.4   31.38  5060.4   30.75
  5080.4    31.8  5100.4   33.79  5120.4   36.46  5130.4   38.43  5140.4   41.28
  5150.4   42.85  5240.4   52.52  5340.4    59.6  5399.3   61.84  5400.4   61.84
#Mann= 5 ,-1 , 0
  4597.3     .05       0  4869.9     .07       0  4970.5     .05       0
  5025.3     .07       0  5399.3     .05       0
Bank Sta=4970.5,5025.3
XS Rating Curve= 0 ,0
Exp/Cntr=0.3,0.1

Type RM Length L Ch R = 1 ,56342   ,529,529,529
BEGIN DESCRIPTION:
KUY CREEK 51.0
END DESCRIPTION:
XS GIS Cut Line= 3
        2612225.       13391725.        2612275.       13391225.
        2612325.     13390825.01
#Sta/Elev= 30
  4492.5   55.08    4603   48.94  4653.3   45.59  4814.1   38.24  4886.4   34.21
  4904.5   33.22  4924.6   31.29  4954.8   29.96  4997.5    29.6  4997.8   26.53
    4999   25.83  5051.5   25.83  5052.6   26.53  5055.5   28.57  5085.7   35.02
  5113.4   40.38  5118.4   40.57    5121   41.26  5151.4   45.31  5186.5   49.74
    5194   51.02  5199.1   51.18  5206.6   52.46  5216.7   53.37  5274.7   57.69
  5279.7   57.68  5307.4   59.78  5330.8   60.85    5378   62.72  5398.1   62.84
#Mann= 6 ,-1 , 0
  4492.5     .05       0  4886.4      .1       0  4997.8     .05       0
  5052.6      .1       0  5151.4     .07       0  5330.8     .05       0
Bank Sta=4997.8,5052.6
XS Rating Curve= 0 ,0
Exp/Cntr=0.3,0.1

Type RM Length L Ch R = 1 ,55813   ,624,624,624
BEGIN DESCRIPTION:
KUY CREEK 50.0
END DESCRIPTION:
XS GIS Cut Line= 3
        2612375.       13391775.        2612575.       13391425.
      2612924.98     13391225.01
#Sta/Elev= 30
  4593.3   56.23  4702.8   47.59  4843.1   37.04  4880.5   35.04  4886.3   34.37
  4917.9   32.45  4929.5   31.41  4945.3   30.64  4945.9   24.26  4947.1   23.56
  4999.6   23.56  5000.8   24.26  5004.3   26.44  5010.1   27.33  5025.9   28.04
  5031.7    28.9  5047.5    29.7  5075.7   29.34    5085    29.8  5100.1    31.8
  5106.5   33.07  5165.6   39.71  5171.3      40  5180.7   41.63  5192.9   45.32
  5215.2   49.56  5267.8   54.36  5289.4   55.74    5311   56.25  5399.5   57.01
#Mann= 6 ,-1 , 0
  4593.3     .05       0  4702.8     .07       0  4917.9      .1       0
  4945.9     .05       0  5000.8      .1       0  5075.7     .07       0
Bank Sta=4945.9,5000.8
XS Rating Curve= 0 ,0
Exp/Cntr=0.3,0.1

Type RM Length L Ch R = 1 ,55189   ,472,472,472
BEGIN DESCRIPTION:
Mapping XS 2a127180
END DESCRIPTION:
XS GIS Cut Line= 3
      2612953.35     13392165.51      2612988.07     13391731.46
      2613126.55     13391298.71
#Sta/Elev= 30
    4557   59.15  4641.6    55.1    4698   51.17  4769.5   44.42  4838.8   35.25
  4868.5   30.44  4968.8   27.96  4968.9   24.34  4970.1   23.64  5022.7   23.64
  5023.8   24.34  5026.7    26.6  5028.5      28  5033.8   27.75  5041.2   28.95
  5065.9   34.79  5072.7   35.78  5083.2      36  5098.1   37.72  5104.2   39.02
  5226.7   48.46  5258.9   49.94  5264.1   49.55    5291   51.77  5296.3   51.26
  5303.7   52.26  5335.2   53.35  5424.9   51.59  5430.1   51.03  5446.8   51.14
#Mann= 5 ,-1 , 0
    4557     .05       0  4838.8      .1       0  4968.9     .05       0
  5023.8      .1       0  5026.7     .07       0
Bank Sta=4968.9,5023.8
XS Rating Curve= 0 ,0
Exp/Cntr=0.3,0.1

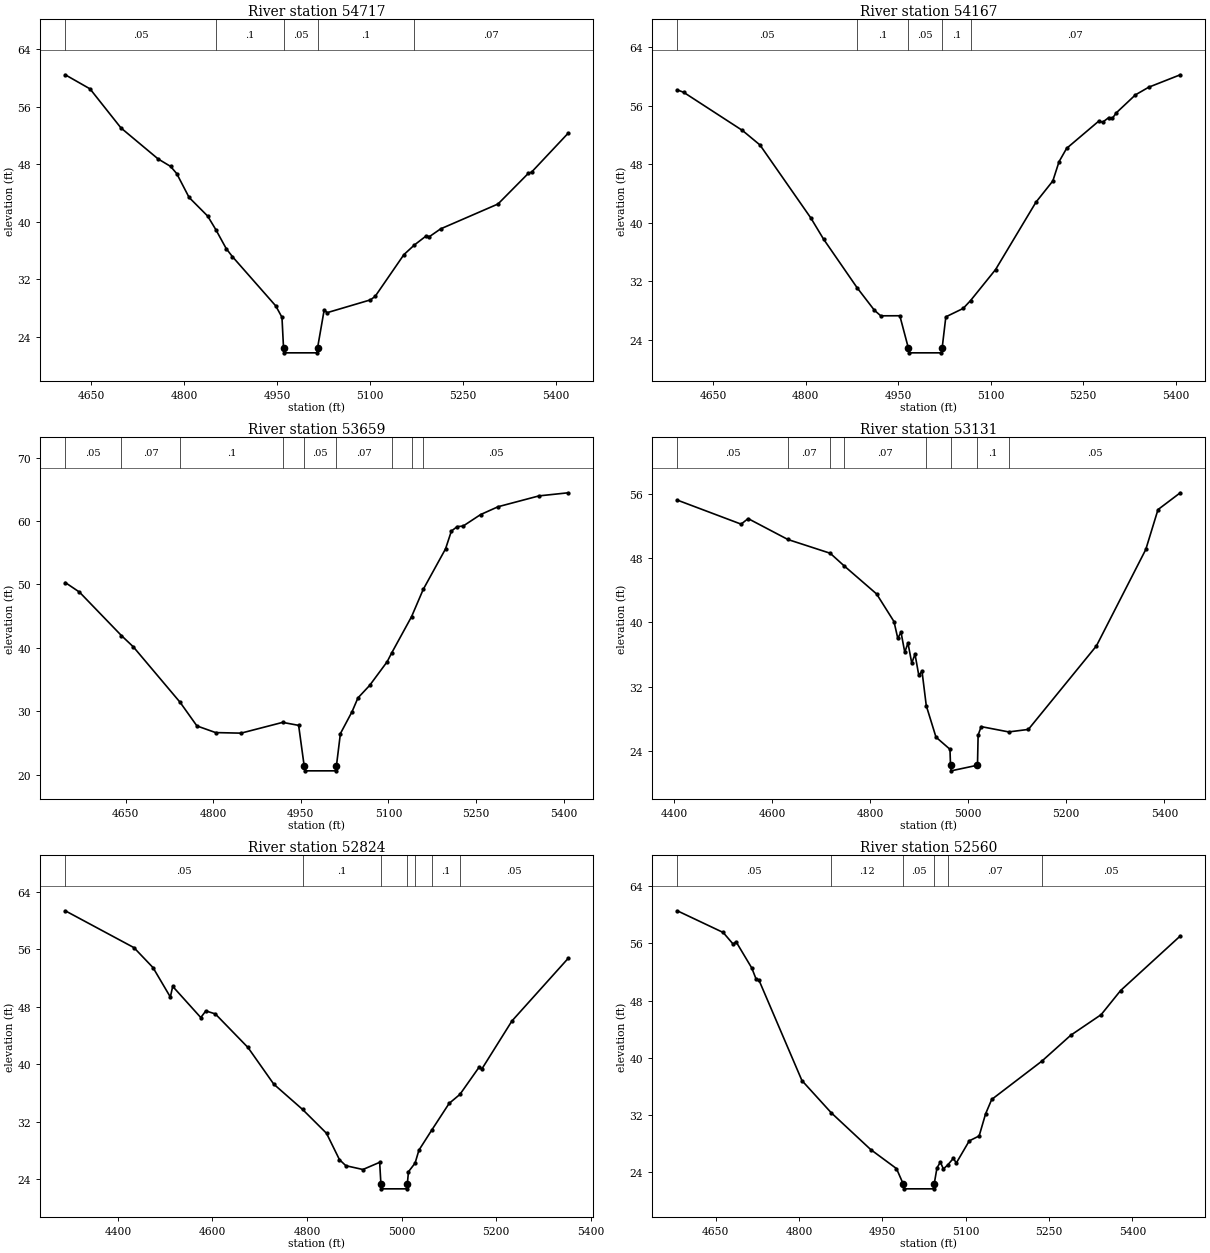
Type RM Length L Ch R = 1 ,54717   ,550,550,550
BEGIN DESCRIPTION:
KUY CREEK 48.0
END DESCRIPTION:
XS GIS Cut Line= 3
        2613375.     13392225.01        2613375.       13391825.
      2613474.99     13391425.02
#Sta/Elev= 30
  4607.8   60.41  4647.8   58.45  4697.8   53.02  4757.8   48.71  4777.8   47.68
  4787.8   46.68  4807.8   43.36  4837.8   40.77    4851   38.88  4867.8   36.24
  4877.8   35.13  4947.8   28.28  4957.8    26.7  4960.3   22.46  4961.5   21.76
  5014.1   21.76  5015.3   22.46  5025.9   27.69    5031   27.35  5100.6   29.12
  5108.3   29.61  5154.7   35.41  5171.5   36.74  5190.8   38.02  5195.9   37.91
    5214   38.99  5306.7   42.45  5355.7   46.71  5360.9   46.88  5420.1    52.3
#Mann= 5 ,-1 , 0
  4607.8     .05       0    4851      .1       0  4960.3     .05       0
  5015.3      .1       0  5171.5     .07       0
Bank Sta=4960.3,5015.3
XS Rating Curve= 0 ,0
Exp/Cntr=0.3,0.1

Type RM Length L Ch R = 1 ,54167   ,508,508,508
BEGIN DESCRIPTION:
KUY CREEK 47.0
END DESCRIPTION:
XS GIS Cut Line= 3
      2613925.01     13392025.04        2613825.       13391625.
      2613624.98     13391274.97
#Sta/Elev= 30
    4592   58.19  4602.3   57.86  4697.7   52.63    4726   50.65  4808.5   40.65
  4829.1   37.76  4883.5    31.1  4911.6   28.01  4921.9   27.25  4952.8   27.26
  4966.5   22.88  4967.7   22.18  5020.3   22.18  5021.5   22.88  5027.4   27.11
  5055.5   28.26  5067.5   29.34    5108   33.58  5173.5   42.81  5200.9   45.72
  5210.9   48.35  5223.2   50.18  5275.7   53.94  5281.5   53.76  5291.6    54.4
  5297.3   54.28  5303.8   55.05  5334.8   57.51  5356.4   58.56  5407.5   60.26
#Mann= 5 ,-1 , 0
    4592     .05       0  4883.5      .1       0  4966.5     .05       0
  5021.5      .1       0  5067.5     .07       0
Bank Sta=4966.5,5021.5
XS Rating Curve= 0 ,0
Exp/Cntr=0.3,0.1

Type RM Length L Ch R = 1 ,53659   ,528,528,528
BEGIN DESCRIPTION:
KUY CREEK 46.0
END DESCRIPTION:
XS GIS Cut Line= 3
        2614175.     13391874.98        2614275.       13391425.
        2614275.     13391024.96
#Sta/Elev= 30
  4546.8   50.31  4571.1    48.8  4642.9   41.94  4663.3   40.16  4743.4    31.4
  4772.2   27.67  4804.2   26.62  4847.7   26.53  4918.9   28.23  4946.3   27.76
  4955.9   21.28  4957.1   20.58  5009.7   20.58  5010.9   21.28  5017.8   26.46
  5037.8   29.93  5047.8   32.09  5067.8   34.06  5097.8    37.8  5105.4   39.16
  5139.6   44.92  5159.5   49.21  5197.8   55.63  5207.8   58.44  5217.8   59.14
  5227.8   59.22  5257.8   61.04  5287.8   62.28  5357.8   63.99  5407.8   64.48
#Mann= 9 ,-1 , 0
  4546.8     .05       0  4642.9     .07       0  4743.4      .1       0
  4918.9     .07       0  4955.9     .05       0  5010.9     .07       0
  5105.4     .05       0  5139.6     .07       0  5159.5     .05       0
Bank Sta=4955.9,5010.9
XS Rating Curve= 0 ,0
Exp/Cntr=0.3,0.1

Type RM Length L Ch R = 1 ,53131   ,307,307,307
BEGIN DESCRIPTION:
KUY CREEK 45.0
END DESCRIPTION:
XS GIS Cut Line= 3
      2614235.23     13392228.76        2614625.       13391775.
      2614775.01     13391374.98
#Sta/Elev= 30
    4407   55.21  4537.1   52.22  4551.4   52.91  4632.5   50.31  4718.7    48.6
    4747   47.04  4813.3   43.54  4848.8    40.1  4856.5   38.02  4863.1   38.78
  4870.7    36.3  4877.3   37.43    4885   34.94  4891.6   36.05  4899.3   33.43
  4905.9   33.93  4914.6   29.64  4934.4   25.73  4962.9   24.22    4964   22.24
  4965.2   21.54    5019   22.24  5020.3   25.98  5026.5   27.04  5082.7   26.38
  5122.7   26.69  5261.5   37.08  5362.1   49.07    5387   54.03  5432.4   56.12
#Mann= 8 ,-1 , 0
    4407     .05       0  4632.5     .07       0  4718.7     .05       0
    4747     .07       0  4914.6      .1       0    4964     .05       0
    5019      .1       0  5082.7     .05       0
Bank Sta=4964,5019
XS Rating Curve= 0 ,0
Exp/Cntr=0.3,0.1

Type RM Length L Ch R = 1 ,52824   ,264,264,264
BEGIN DESCRIPTION:
Mapping XS a2aec039
END DESCRIPTION:
XS GIS Cut Line= 4
      2614933.15     13392429.24      2614965.24     13392164.02
      2614879.79     13391761.15      2614822.49     13391380.93
#Sta/Elev= 30
  4288.7   61.36    4434   56.23  4474.3   53.45  4510.9   49.36  4515.9   50.84
  4575.3    46.5  4585.9   47.43    4606   47.01    4675   42.34  4729.7   37.23
  4790.6   33.71  4841.1    30.4  4868.5   26.73    4882   25.89  4918.1   25.36
  4953.5   26.36  4956.1   23.37  4957.3   22.67  5010.7   22.67    5012   23.37
  5014.4   25.05  5028.4   26.25  5036.5   28.05  5063.1   30.79  5100.4   34.56
  5123.2   35.81  5164.3   39.65  5169.3   39.32  5233.2   46.03  5352.2   54.75
#Mann= 7 ,-1 , 0
  4288.7     .05       0  4790.6      .1       0  4956.1     .05       0
    5012      .1       0  5028.4     .07       0  5063.1      .1       0
  5123.2     .05       0
Bank Sta=4956.1,5012
XS Rating Curve= 0 ,0
Exp/Cntr=0.3,0.1

Type RM Length L Ch R = 1 ,52560   ,537,537,537
BEGIN DESCRIPTION:
KUY CREEK 44.0
END DESCRIPTION:
XS GIS Cut Line= 3
      2615225.01     13392175.05        2615125.       13391775.
        2614925.       13391325.
#Sta/Elev= 30
  4581.2   60.54  4663.7   57.51  4681.7   55.88  4686.9   56.22  4715.2   52.54
    4723   50.99  4728.1   50.85  4805.4   36.82  4858.1   32.32  4929.1   27.18
  4975.5   24.52  4987.5   22.39  4988.7   21.69  5042.1   21.69  5043.4   22.39
  5048.3    24.6  5054.4   25.43  5059.9   24.47  5067.6   25.02  5077.7   25.94
  5083.2   25.31  5106.4   28.39  5124.2   29.08  5135.8   32.17  5146.8   34.18
    5237   39.53    5289   43.15  5343.7   46.03  5378.6   49.39    5486   57.02
#Mann= 6 ,-1 , 0
  4581.2     .05       0  4858.1     .12       0  4987.5     .05       0
  5043.4     .12       0  5067.6     .07       0    5237     .05       0
Bank Sta=4987.5,5043.4
XS Rating Curve= 0 ,0
Exp/Cntr=0.3,0.1

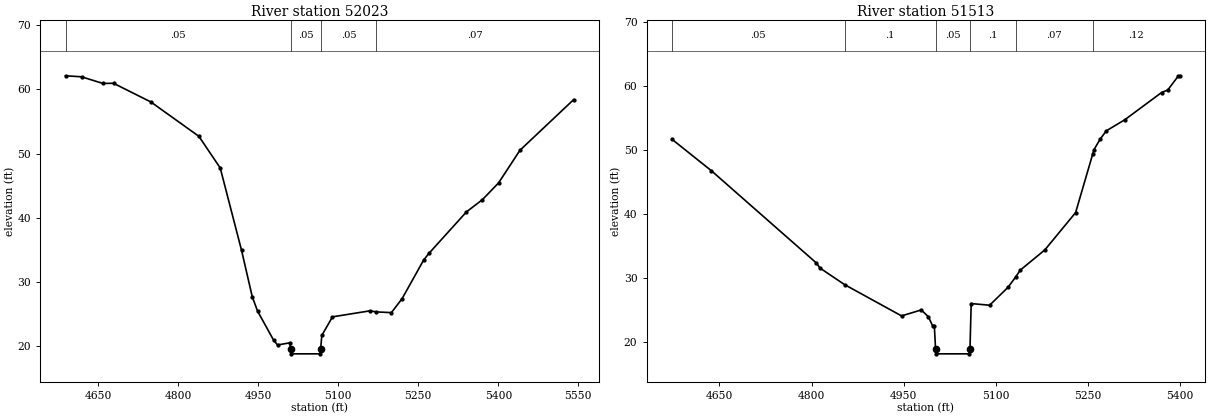
Type RM Length L Ch R = 1 ,52023   ,510,510,510
BEGIN DESCRIPTION:
KUY CREEK 43.0
END DESCRIPTION:
XS GIS Cut Line= 3
        2615575.     13392225.03        2615575.       13391825.
        2615525.       13391275.
#Sta/Elev= 30
  4588.7   62.13  4618.7   61.97  4658.7   60.94  4678.7   60.96  4748.7   58.05
  4838.7    52.7  4878.7   47.77  4918.7   34.93  4938.7   27.72  4948.7   25.47
  4978.7   20.95  4986.2   20.19  5008.8   20.52    5011   19.51  5012.2   18.81
  5065.7   18.81  5066.9   19.51  5069.1   21.67  5089.1   24.57  5159.4   25.51
  5171.5   25.34  5199.6   25.23  5219.7   27.42  5259.8   33.39  5269.9   34.46
  5340.2   40.92  5370.3   42.84  5400.4   45.43  5440.6   50.53    5541    58.4
#Mann= 4 ,-1 , 0
  4588.7     .05       0    5011     .05       0  5066.9     .05       0
  5171.5     .07       0
Bank Sta=5011,5066.9
XS Rating Curve= 0 ,0
Exp/Cntr=0.3,0.1

Type RM Length L Ch R = 1 ,51513   ,570,570,570
BEGIN DESCRIPTION:
KUY CREEK 42.0
END DESCRIPTION:
XS GIS Cut Line= 3
      2615775.02     13392024.96        2615925.       13391625.
        2615925.     13391224.96
#Sta/Elev= 30
  4572.8    51.7  4636.8   46.79  4807.7   32.35  4813.9   31.53  4853.8   28.95
  4946.6   24.05  4978.6   24.98  4990.2   23.93  4997.3   22.48    5000   22.48
    5002   18.81  5003.2   18.11  5056.7   18.11    5058   18.81    5060   25.98
    5090   25.72    5120   28.53  5132.4   30.14    5140   31.22    5180   34.39
    5230   40.22  5257.9    49.4    5260   50.08    5270   51.73    5280   53.02
    5310   54.75    5370   59.02    5380   59.41  5397.5   61.64    5400   61.64
#Mann= 6 ,-1 , 0
  4572.8     .05       0  4853.8      .1       0    5002     .05       0
    5058      .1       0  5132.4     .07       0  5257.9     .12       0
Bank Sta=5002,5058
XS Rating Curve= 0 ,0
Exp/Cntr=0.3,0.1