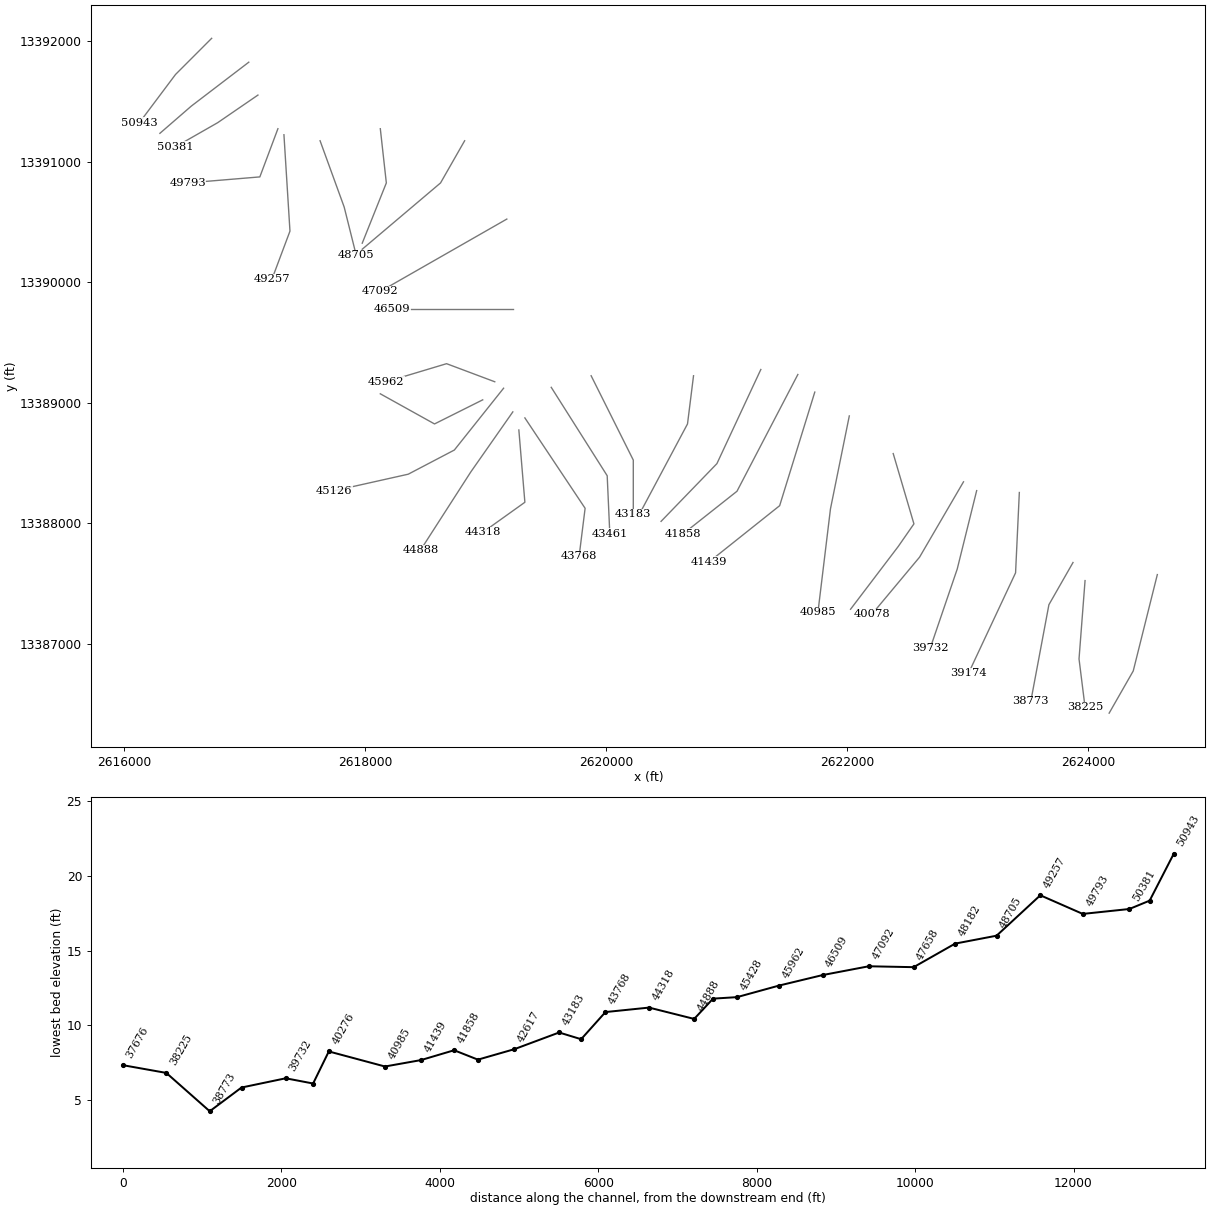
HEC-RAS study KUY CREEK.prj: KUY CREEK Base Level Engineering

--- KUY CREEK.g01 (geometry) --- (continued)

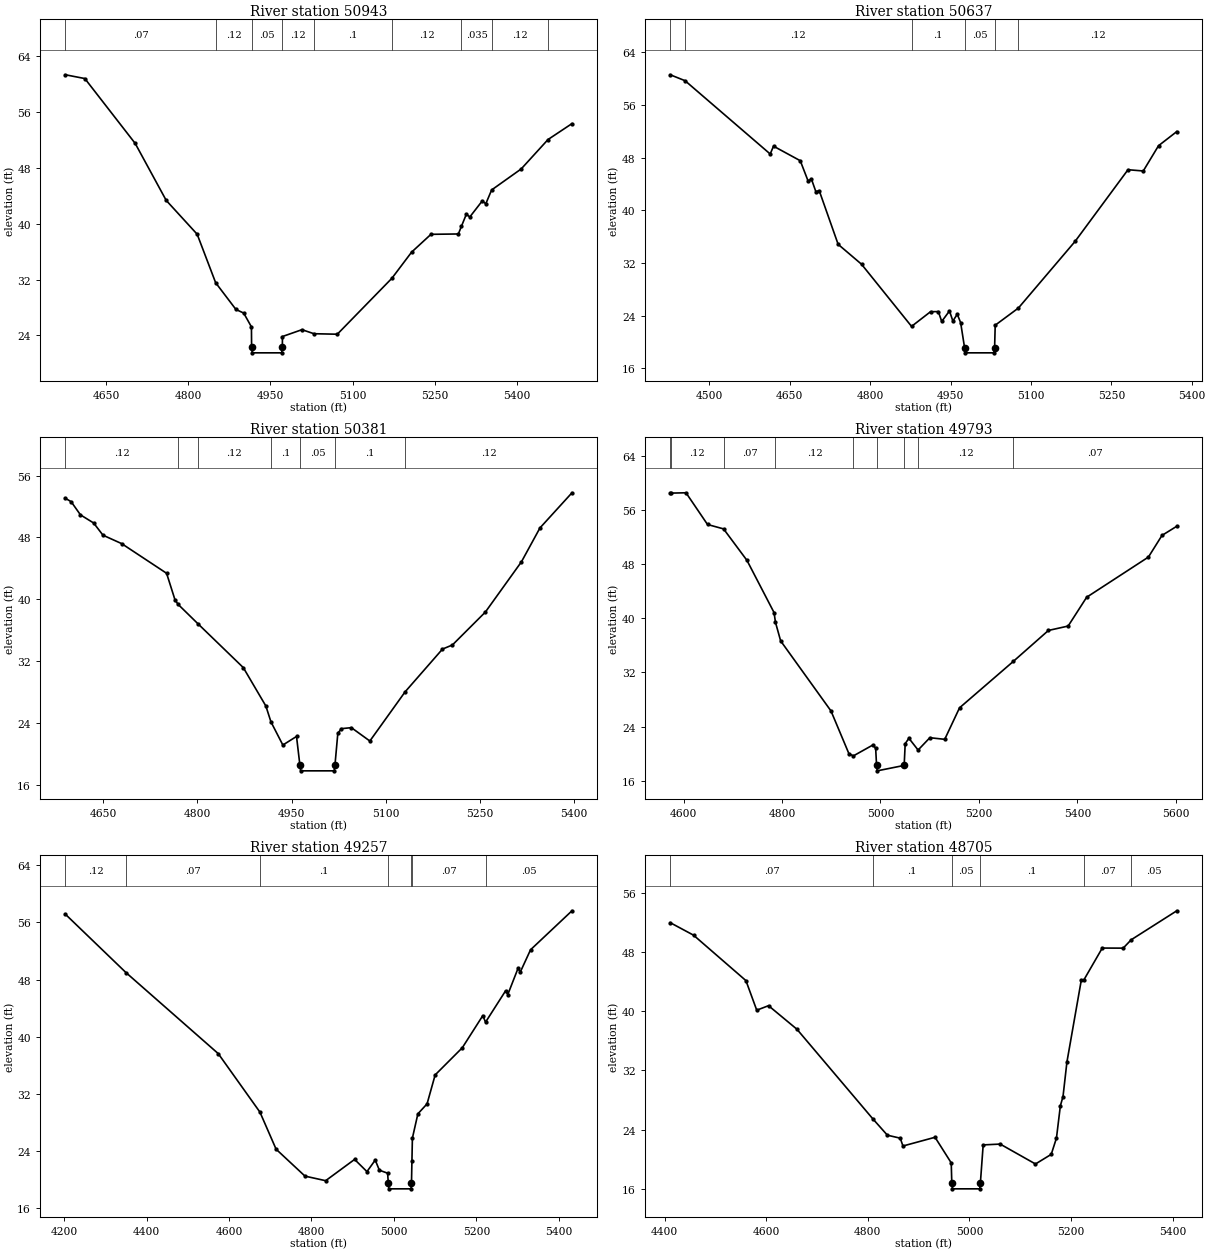
Type RM Length L Ch R = 1 ,50943   ,306,306,306
BEGIN DESCRIPTION:
KUY CREEK 41.0
END DESCRIPTION:
XS GIS Cut Line= 3
      2616725.01     13392025.01        2616425.       13391725.
      2616124.98     13391324.98
#Sta/Elev= 30
    4576   61.37  4611.4   60.83  4703.3   51.53  4759.9   43.36  4816.4   38.51
  4850.1   31.56  4887.1   27.73  4901.3   27.21  4915.4   25.23  4915.7   22.31
  4916.9   21.51  4970.5   21.51  4971.8   22.31    4972   23.85  5007.6   24.83
  5029.5   24.25  5072.1   24.18  5171.7    32.2  5207.6   35.94    5243    38.5
    5293   38.55  5298.7   39.67  5307.6   41.39  5313.8   40.98  5336.7    43.3
    5343   42.87  5353.7   44.86  5407.6   47.87  5456.6   52.09  5500.3   54.37
#Mann= 9 ,-1 , 0
    4576     .07       0  4850.1     .12       0  4915.7     .05       0
  4971.8     .12       0  5029.5      .1       0  5171.7     .12       0
  5298.7    .035       0  5353.7     .12       0  5456.6    .035       0
Bank Sta=4915.7,4971.8
XS Rating Curve= 0 ,0
Exp/Cntr=0.3,0.1

Type RM Length L Ch R = 1 ,50637   ,256,256,256
BEGIN DESCRIPTION:
Mapping XS 8411f29a
END DESCRIPTION:
XS GIS Cut Line= 3
      2617033.22     13391826.96      2616555.78     13391462.37
      2616295.39     13391236.69
#Sta/Elev= 30
  4426.9   60.61  4454.5   59.71  4613.4   48.57  4619.6   49.76  4669.5   47.55
  4684.1   44.47  4690.3   44.77  4698.6   42.85  4704.9      43  4740.2   34.84
  4783.8   31.82  4877.2   22.37  4912.6    24.6  4927.2   24.62  4933.5   23.12
    4948   24.72  4954.3   23.18  4962.5   24.22  4968.8   22.94  4976.1   19.15
  4977.4   18.35    5031   18.35  5032.2   19.15  5033.3   22.55  5076.6   25.16
  5182.4   35.29  5281.1   46.18  5309.6   45.99  5338.1   49.83  5372.2   51.98
#Mann= 6 ,-1 , 0
  4426.9     .07       0  4454.5     .12       0  4877.2      .1       0
  4976.1     .05       0  5032.2      .1       0  5076.6     .12       0
Bank Sta=4976.1,5032.2
XS Rating Curve= 0 ,0
Exp/Cntr=0.3,0.1

Type RM Length L Ch R = 1 ,50381   ,588,588,588
BEGIN DESCRIPTION:
KUY CREEK 40.0
END DESCRIPTION:
XS GIS Cut Line= 3
      2617109.12     13391554.05        2616775.       13391325.
        2616425.       13391125.
#Sta/Elev= 30
  4589.3   53.06  4598.4   52.63  4613.3   50.92  4634.3   49.87  4649.2   48.29
    4679    47.2  4750.7   43.36    4764   39.95  4768.9   39.35  4800.3   36.86
  4873.1   31.15  4909.1   26.18  4917.2   24.13  4936.2   21.13    4958   22.24
  4963.3   18.59  4964.6   17.79  5018.2   17.79  5019.4   18.59  5023.9   22.65
  5029.7   23.25  5045.5   23.38    5075   21.65  5131.2   28.01  5190.9   33.55
  5206.7   34.08  5259.3   38.34  5316.9   44.85  5346.4   49.23  5397.5   53.78
#Mann= 7 ,-1 , 0
  4589.3     .12       0  4768.9      .1       0  4800.3     .12       0
  4917.2      .1       0  4963.3     .05       0  5019.4      .1       0
  5131.2     .12       0
Bank Sta=4963.3,5019.4
XS Rating Curve= 0 ,0
Exp/Cntr=0.3,0.1

Type RM Length L Ch R = 1 ,49793   ,536,536,536
BEGIN DESCRIPTION:
KUY CREEK 39.0
END DESCRIPTION:
XS GIS Cut Line= 3
        2617275.       13391275.        2617125.       13390875.
      2616524.98       13390825.
#Sta/Elev= 30
  4572.8   58.45  4573.6   58.45  4604.8    58.5  4648.5   53.82  4681.1   53.17
  4728.6   48.53  4783.7   40.82  4786.6   39.38  4797.1   36.64  4899.4    26.3
  4935.9   19.98    4945   19.67  4984.9   21.29  4990.2   20.78    4992   18.26
  4993.3   17.46  5048.1   18.26  5050.2   21.47  5057.7   22.27  5076.4   20.53
  5100.3   22.35  5130.5   22.11  5160.6   26.76    5270   33.62  5341.2   38.18
  5381.3   38.83  5418.9   43.08  5544.4   49.01    5572   52.21  5602.1   53.56
#Mann= 9 ,-1 , 0
  4572.8     .07       0  4573.6     .12       0  4681.1     .07       0
  4786.6     .12       0    4945      .1       0    4992     .05       0
  5048.1      .1       0  5076.4     .12       0    5270     .07       0
Bank Sta=4992,5048.1
XS Rating Curve= 0 ,0
Exp/Cntr=0.3,0.1

Type RM Length L Ch R = 1 ,49257   ,552,552,552
BEGIN DESCRIPTION:
KUY CREEK 38.0
END DESCRIPTION:
XS GIS Cut Line= 3
        2617325.     13391224.99        2617375.       13390425.
      2617225.02     13390025.05
#Sta/Elev= 30
  4203.3   57.15  4350.1   48.99    4574   37.64  4675.1   29.45  4714.3   24.26
  4784.4   20.49  4834.5   19.85  4904.7   22.83  4934.7   21.12  4954.8   22.74
  4964.8   21.32  4984.8    20.9  4986.5   19.51  4987.8   18.71  5041.5   18.71
  5042.7   19.51  5043.8   22.66  5044.9   25.81  5058.2   29.21  5080.5   30.61
  5100.1   34.66  5165.9   38.46  5215.8   42.97  5222.3   42.04    5271   46.44
  5276.3   45.91  5301.2   49.59  5306.6   49.06  5331.5   52.18    5432   57.64
#Mann= 7 ,-1 , 0
  4203.3     .12       0  4350.1     .07       0  4675.1      .1       0
  4986.5     .05       0  5042.7      .1       0  5043.8     .07       0
  5222.3     .05       0
Bank Sta=4986.5,5042.7
XS Rating Curve= 0 ,0
Exp/Cntr=0.3,0.1

Type RM Length L Ch R = 1 ,48705   ,523,523,523
BEGIN DESCRIPTION:
KUY CREEK 37.0
END DESCRIPTION:
XS GIS Cut Line= 3
        2617625.       13391175.        2617825.       13390625.
      2617924.99     13390225.04
#Sta/Elev= 30
  4410.9   51.98  4456.8   50.29  4559.9   44.15  4581.2   40.15  4604.4   40.76
  4660.3   37.58  4809.7   25.47  4838.5   23.25  4863.8   22.85  4869.1   21.79
  4932.3   22.97  4964.2   19.51  4965.3    16.8  4966.6      16  5020.3      16
  5021.6    16.8  5027.1   21.94  5060.6   22.05  5130.1   19.36  5161.1   20.66
  5171.4   22.86  5179.1   27.23  5184.3   28.47    5192   33.14  5220.3   44.21
  5225.1   44.21  5261.6   48.55  5302.8   48.54  5318.6   49.67  5408.4   53.59
#Mann= 6 ,-1 , 0
  4410.9     .07       0  4809.7      .1       0  4965.3     .05       0
  5021.6      .1       0  5225.1     .07       0  5318.6     .05       0
Bank Sta=4965.3,5021.6
XS Rating Curve= 0 ,0
Exp/Cntr=0.3,0.1

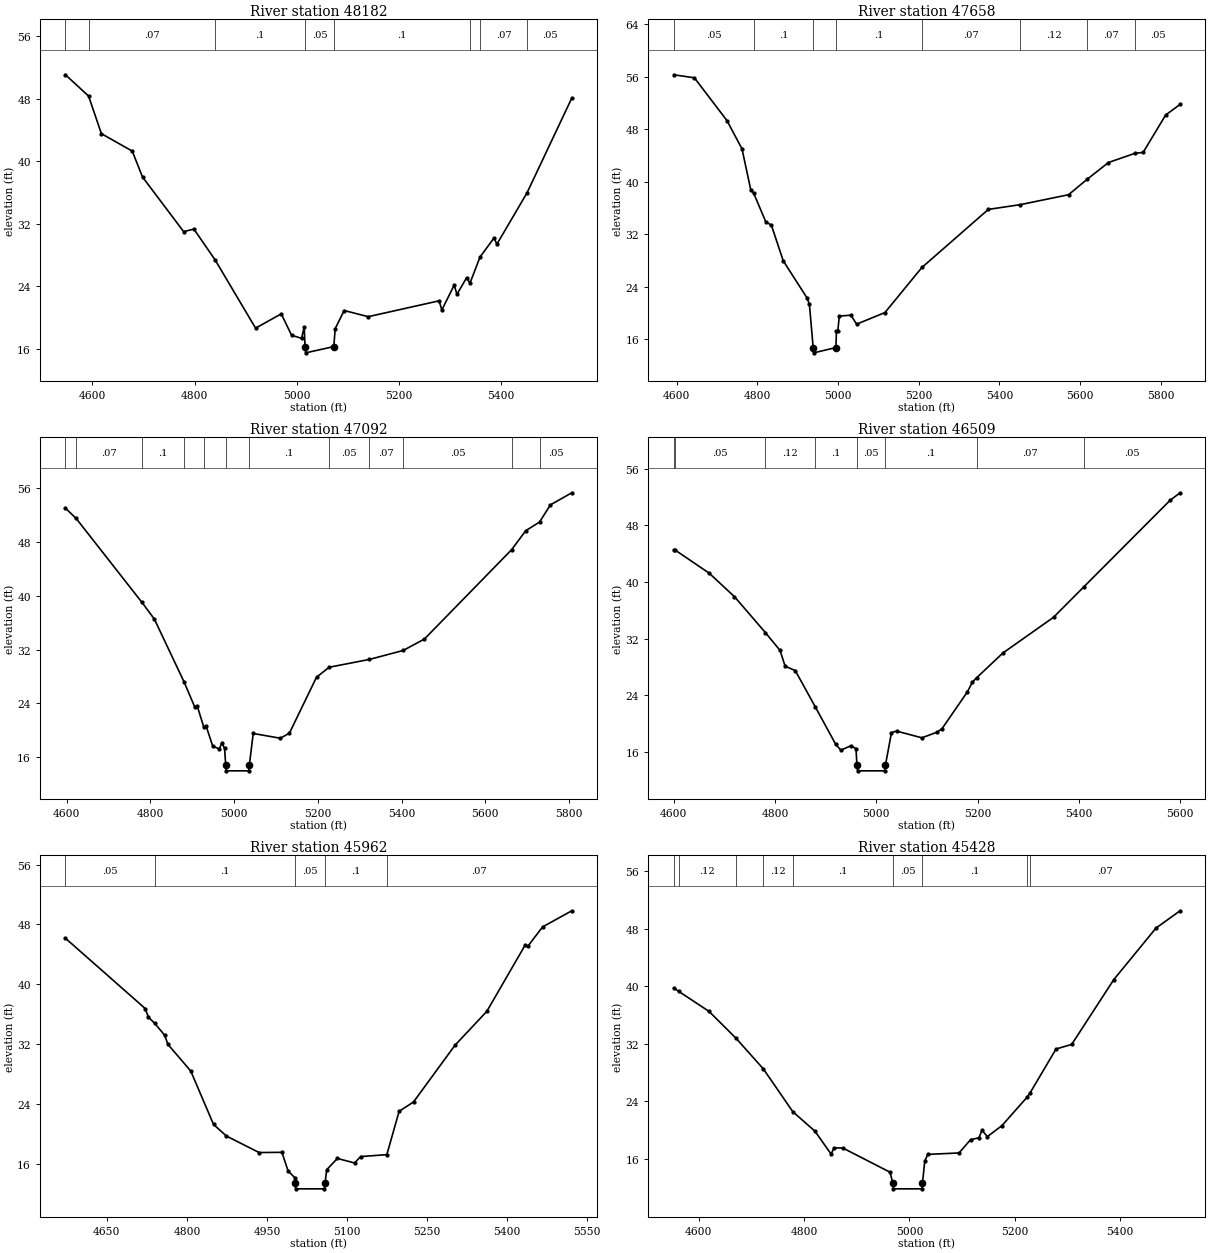
Type RM Length L Ch R = 1 ,48182   ,524,524,524
BEGIN DESCRIPTION:
KUY CREEK 36.0
END DESCRIPTION:
XS GIS Cut Line= 3
        2618125.     13391274.96        2618175.       13390825.
      2617975.02     13390325.04
#Sta/Elev= 30
  4547.3   51.07  4592.6   48.35  4617.7   43.53  4678.1    41.3  4698.2   37.98
  4778.7   30.99  4798.8   31.31  4840.4   27.36  4919.5   18.63  4969.8   20.46
    4990   17.72  5009.5   17.33  5014.8   18.77  5016.3   16.27  5017.6   15.47
  5072.6   16.27  5075.4   18.57  5092.9   20.89    5140    20.1  5278.7   22.13
  5284.1   20.96  5308.3   24.14  5313.7   22.96  5332.6   25.09  5339.1   24.38
  5358.9   27.74  5386.4   30.19  5391.8   29.37  5450.9   35.96  5538.5   48.09
#Mann= 8 ,-1 , 0
  4547.3     .05       0  4592.6     .07       0  4840.4      .1       0
  5016.3     .05       0  5072.6      .1       0  5339.1     .12       0
  5358.9     .07       0  5450.9     .05       0
Bank Sta=5016.3,5072.6
XS Rating Curve= 0 ,0
Exp/Cntr=0.3,0.1

Type RM Length L Ch R = 1 ,47658   ,566,566,566
BEGIN DESCRIPTION:
KUY CREEK 35.0
END DESCRIPTION:
XS GIS Cut Line= 3
      2618825.02     13391175.04        2618625.       13390825.
      2617975.02     13390275.02
#Sta/Elev= 30
  4592.9   56.27  4644.1   55.81  4724.7    49.3  4762.1   44.98  4783.7   38.76
  4791.1    38.2  4821.1   33.85  4834.8   33.36  4864.3   27.91  4923.4   22.24
  4929.1   21.27  4938.4   14.69  4939.6   13.89  4994.7   14.69  4996.1   17.15
  4999.3   17.15  5003.2   19.49  5031.8   19.63  5046.1   18.26  5116.3   20.03
  5207.8    26.9  5372.4   35.75  5451.9   36.48  5571.2   37.99  5616.9   40.33
  5670.1    42.9  5736.2   44.31  5755.8   44.43  5811.8   50.14  5847.5   51.76
#Mann= 8 ,-1 , 0
  4592.9     .05       0  4791.1      .1       0  4938.4     .05       0
  4994.7      .1       0  5207.8     .07       0  5451.9     .12       0
  5616.9     .07       0  5736.2     .05       0
Bank Sta=4938.4,4994.7
XS Rating Curve= 0 ,0
Exp/Cntr=0.3,0.1

Type RM Length L Ch R = 1 ,47092   ,583,583,583
BEGIN DESCRIPTION:
KUY CREEK 34.0
END DESCRIPTION:
XS GIS Cut Line= 3
      2619175.04     13390525.02        2618825.       13390325.
      2618124.98     13389924.99
#Sta/Elev= 30
  4597.3   53.03  4622.8   51.51  4780.2      39  4809.7   36.53  4880.8   27.16
  4906.2   23.44  4911.9   23.64    4928    20.4  4933.5   20.59  4949.3   17.58
  4965.2   17.23  4970.9   18.13  4977.4   17.28  4980.2   14.75  4981.5   13.95
  5035.3   13.95  5036.5   14.75  5045.8   19.51  5110.6    18.8  5132.2   19.55
    5197   27.88  5227.1   29.36  5323.5   30.53    5404   31.86  5454.7   33.56
  5663.1   46.86  5696.5   49.67  5729.6   50.96  5755.6   53.52  5806.7   55.32
#Mann= 12 ,-1 , 0
  4597.3     .05       0  4622.8     .07       0  4780.2      .1       0
  4880.8     .07       0    4928      .1       0  4980.2     .05       0
  5036.5      .1       0  5227.1     .05       0  5323.5     .07       0
    5404     .05       0  5663.1     .07       0  5729.6     .05       0
Bank Sta=4980.2,5036.5
XS Rating Curve= 0 ,0
Exp/Cntr=0.3,0.1

Type RM Length L Ch R = 1 ,46509   ,547,547,547
BEGIN DESCRIPTION:
KUY CREEK 33.0
END DESCRIPTION:
XS GIS Cut Line= 3
        2619225.       13389775.        2618825.       13389775.
        2618225.       13389775.
#Sta/Elev= 30
    4600   44.56  4601.7   44.56    4670   41.25    4720   37.93  4781.1   32.86
    4810   30.35    4820   28.12    4840   27.51  4879.4   22.41    4920   17.09
    4930   16.28    4950    16.9    4960   16.49  4961.8   14.16  4963.1   13.36
  5016.9   13.36  5018.1   14.16    5030   18.75    5040   18.97    5090   18.02
    5120   18.81    5130   19.32    5180   24.51    5190   25.89    5198   26.48
    5250   29.98    5350   35.02  5410.2   39.34    5580   51.51    5600   52.59
#Mann= 8 ,-1 , 0
    4600     .07       0  4601.7     .05       0  4781.1     .12       0
  4879.4      .1       0  4961.8     .05       0  5018.1      .1       0
    5198     .07       0  5410.2     .05       0
Bank Sta=4961.8,5018.1
XS Rating Curve= 0 ,0
Exp/Cntr=0.3,0.1

Type RM Length L Ch R = 1 ,45962   ,534,534,534
BEGIN DESCRIPTION:
KUY CREEK 32.0
END DESCRIPTION:
XS GIS Cut Line= 3
      2619074.96     13389175.01        2618675.       13389325.
      2618174.97     13389174.99
#Sta/Elev= 30
  4572.3   46.15  4721.8   36.76    4728   35.58  4739.7   34.78  4758.3   33.19
  4764.5   31.96  4807.2   28.41  4849.9   21.27    4874   19.72  4935.4   17.51
  4978.1   17.54  4989.7   15.05  5002.1   14.16  5002.6   13.46  5003.9   12.66
  5057.7   12.66    5059   13.46  5062.1   15.22  5082.1   16.72  5114.3   16.12
  5125.6   16.97  5174.8   17.23  5197.8   23.02  5224.8   24.27  5302.2   31.82
  5362.3   36.39  5433.6   45.18  5438.8   45.05  5466.7   47.66  5521.5   49.82
#Mann= 5 ,-1 , 0
  4572.3     .05       0  4739.7      .1       0  5002.6     .05       0
    5059      .1       0  5174.8     .07       0
Bank Sta=5002.6,5059
XS Rating Curve= 0 ,0
Exp/Cntr=0.3,0.1

Type RM Length L Ch R = 1 ,45428   ,302,302,302
BEGIN DESCRIPTION:
KUY CREEK 31.0
END DESCRIPTION:
XS GIS Cut Line= 3
      2618974.98     13389024.99        2618575.       13388825.
      2618124.97     13389075.02
#Sta/Elev= 30
  4552.3   39.75  4561.9   39.27  4619.4    36.5  4670.2   32.81  4722.6   28.52
  4778.6   22.58  4820.6   19.88  4851.3    16.7  4856.9   17.57  4873.7   17.54
  4963.2   14.19  4968.5   12.68  4969.7   11.88  5023.6   11.88  5024.9   12.68
  5029.2   15.72  5034.9   16.66  5094.4   16.86  5116.2    18.7  5132.2   18.96
  5137.9   20.01  5148.2   19.13  5175.7   20.64  5223.3   24.57  5228.9   25.14
  5278.6   31.28  5308.4   31.92  5388.4   40.92  5468.5   48.06  5514.3   50.46
#Mann= 9 ,-1 , 0
  4552.3     .05       0  4561.9     .12       0  4670.2     .07       0
  4722.6     .12       0  4778.6      .1       0  4968.5     .05       0
  5024.9      .1       0  5223.3     .05       0  5228.9     .07       0
Bank Sta=4968.5,5024.9
XS Rating Curve= 0 ,0
Exp/Cntr=0.3,0.1

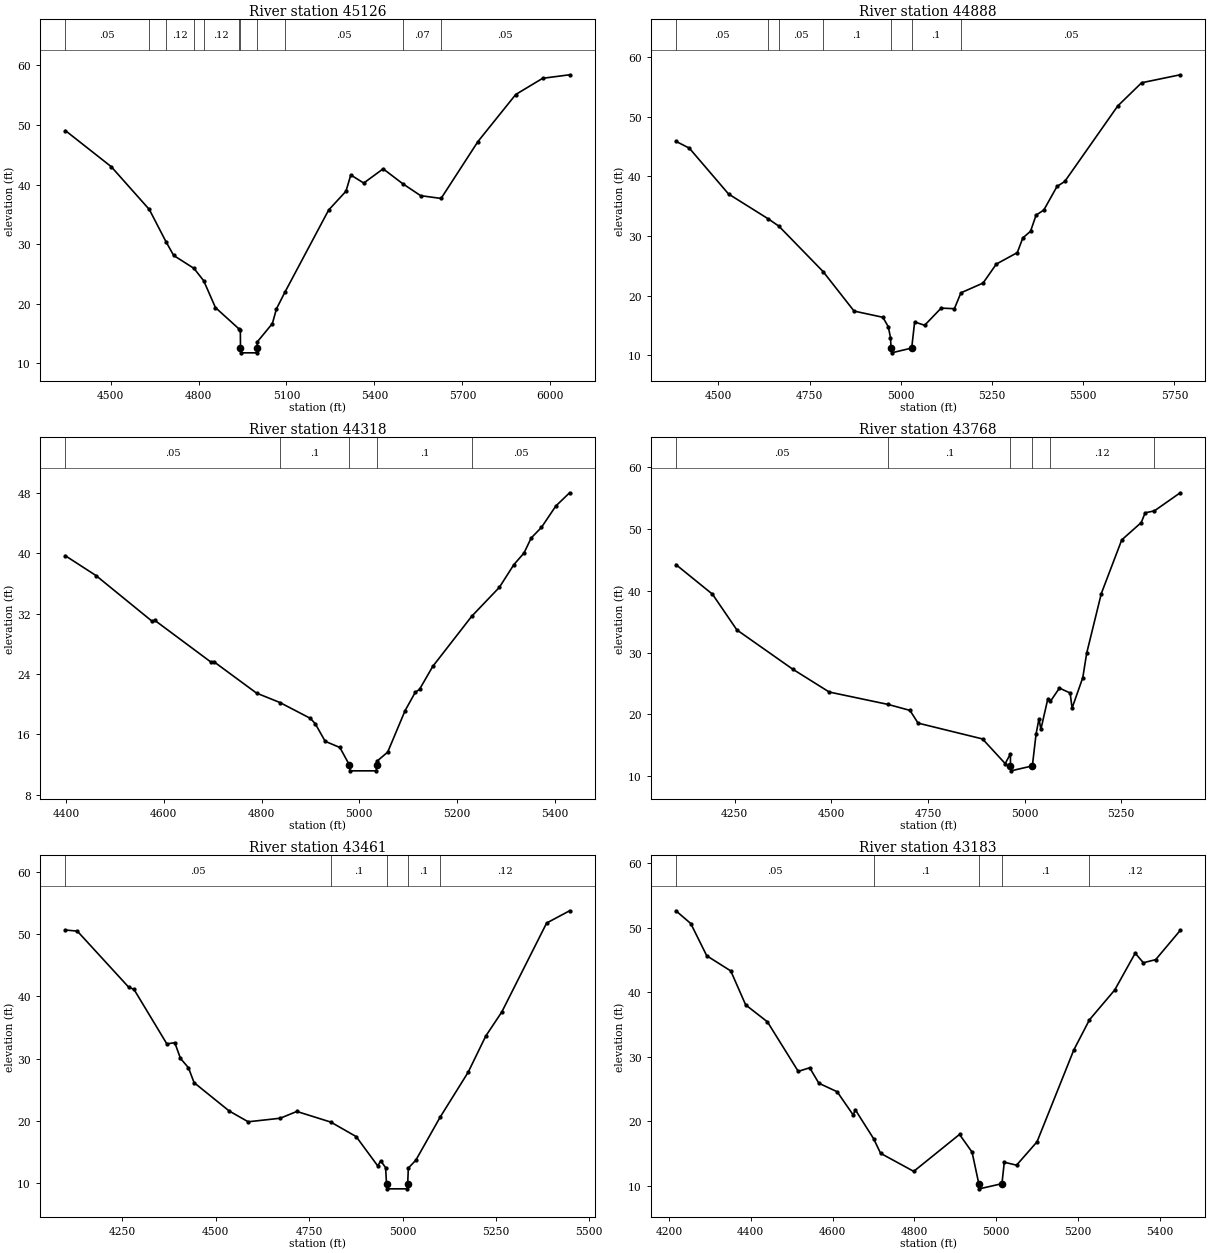
Type RM Length L Ch R = 1 ,45126   ,238,238,238
BEGIN DESCRIPTION:
Mapping XS 4b2668d6
END DESCRIPTION:
XS GIS Cut Line= 4
      2619148.37     13389121.45      2618739.54     13388608.46
      2618356.73     13388407.94      2617739.98     13388270.02
#Sta/Elev= 30
  4345.6   49.06  4502.2      43  4632.1   35.82  4688.6   30.45  4715.2   28.11
  4784.5   25.94  4817.6   23.87  4857.7   19.37  4936.9   15.84  4942.6   15.67
  4943.1   12.58  4944.4   11.78  4998.3   11.78  4999.6   12.58  5000.2   13.61
  5051.9   16.69  5065.8   19.16  5094.1    21.9  5243.8   35.73  5302.9   38.88
  5319.3   41.61  5363.5   40.25  5429.7   42.64    5496   40.16  5557.5   38.14
  5627.3   37.67  5753.1   47.22  5881.9    55.1  5973.8   57.82  6065.7   58.41
#Mann= 11 ,-1 , 0
  4345.6     .05       0  4632.1     .07       0  4688.6     .12       0
  4784.5     .07       0  4817.6     .12       0  4936.9      .1       0
  4943.1     .05       0  4999.6      .1       0  5094.1     .05       0
    5496     .07       0  5627.3     .05       0
Bank Sta=4943.1,4999.6
XS Rating Curve= 0 ,0
Exp/Cntr=0.3,0.1

Type RM Length L Ch R = 1 ,44888   ,570,570,570
BEGIN DESCRIPTION:
KUY CREEK 30.0
END DESCRIPTION:
XS GIS Cut Line= 3
      2619225.02     13388925.04        2618875.       13388425.
      2618457.43       13387776.
#Sta/Elev= 30
  4383.8   45.88  4420.5   44.74  4528.1   37.05  4637.2   32.87    4666   31.66
  4787.1   24.05  4872.1   17.42    4951   16.38  4965.8   14.81  4971.9   12.97
  4973.5   11.22  4974.8   10.42    5030   11.22  5038.1    15.6  5065.5   15.04
  5110.7   17.92    5147   17.82  5164.9   20.48  5225.6   22.12  5261.9    25.3
  5319.4   27.22  5334.6   29.69  5355.7    30.8  5370.9   33.51    5392   34.35
  5428.3   38.32  5449.5   39.15  5594.7   51.81  5660.1    55.7  5765.9   57.04
#Mann= 7 ,-1 , 0
  4383.8     .05       0  4637.2     .07       0    4666     .05       0
  4787.1      .1       0  4973.5     .05       0    5030      .1       0
  5164.9     .05       0
Bank Sta=4973.5,5030
XS Rating Curve= 0 ,0
Exp/Cntr=0.3,0.1

Type RM Length L Ch R = 1 ,44318   ,550,550,550
BEGIN DESCRIPTION:
KUY CREEK 29.0
END DESCRIPTION:
XS GIS Cut Line= 3
        2619275.     13388774.95        2619325.       13388175.
      2618975.04     13387925.03
#Sta/Elev= 30
  4398.3   39.65    4461   37.03  4576.4   30.95  4581.4    31.1  4696.8   25.55
  4701.8   25.65  4789.6   21.47  4837.5   20.22    4900   18.12    4910    17.4
  4930.1   15.09  4960.2   14.27  4979.5   11.98  4980.8   11.18  5034.7   11.18
    5036   11.98  5037.2   12.51  5058.1   13.66  5093.7   19.15  5114.6   21.58
  5123.2   21.96  5150.3      25  5230.1   31.64  5286.7   35.47  5316.2   38.46
  5337.1   40.01  5351.8      42  5372.7   43.39  5402.2   46.23  5430.4   47.98
#Mann= 5 ,-1 , 0
  4398.3     .05       0  4837.5      .1       0  4979.5     .05       0
    5036      .1       0  5230.1     .05       0
Bank Sta=4979.5,5036
XS Rating Curve= 0 ,0
Exp/Cntr=0.3,0.1

Type RM Length L Ch R = 1 ,43768   ,307,307,307
BEGIN DESCRIPTION:
KUY CREEK 28.0
END DESCRIPTION:
XS GIS Cut Line= 3
      2619325.02     13388874.97        2619825.       13388125.
        2619775.     13387724.96
#Sta/Elev= 30
  4098.2   44.25  4192.8   39.46  4255.9   33.68  4400.1   27.34  4494.8   23.63
  4647.4   21.62  4703.6   20.66  4724.6    18.6  4891.4   16.04    4950   12.05
  4963.5   13.63  4963.7   11.68    4965   10.88  5020.3   11.68  5029.8   16.82
  5037.3   19.27  5042.4   17.62    5060   22.46  5067.1   22.14  5090.3   24.27
    5118   23.47    5123   21.03  5150.7   25.96  5160.8   29.92  5198.6   39.56
  5251.5   48.25  5301.9   51.05    5312   52.63  5335.9   52.94  5402.7   55.87
#Mann= 6 ,-1 , 0
  4098.2     .05       0  4647.4      .1       0  4963.7     .05       0
  5020.3      .1       0  5067.1     .12       0  5335.9     .07       0
Bank Sta=4963.7,5020.3
XS Rating Curve= 0 ,0
Exp/Cntr=0.3,0.1

Type RM Length L Ch R = 1 ,43461   ,278,278,278
BEGIN DESCRIPTION:
Mapping XS afecaf0b
END DESCRIPTION:
XS GIS Cut Line= 3
      2619543.89     13389128.75      2620008.31     13388395.23
        2620030.      13387913.6
#Sta/Elev= 30
  4096.9   50.67    4129   50.49    4267   41.45  4280.7   41.13  4368.8   32.36
    4390   32.56  4405.3   30.02  4426.5   28.54  4441.7   26.13  4535.8   21.57
  4586.6   19.84  4672.3   20.41  4716.8    21.5  4807.8   19.79  4875.7   17.46
  4933.3   12.76  4941.7   13.56  4954.5   12.46    4957    9.86  4958.3    9.06
  5012.3    9.06  5013.6    9.86  5015.4    12.4  5035.4   13.66  5100.2   20.55
  5175.5    27.8  5222.7   33.62  5265.6   37.49  5385.7   51.79  5447.2   53.76
#Mann= 5 ,-1 , 0
  4096.9     .05       0  4807.8      .1       0    4957     .05       0
  5013.6      .1       0  5100.2     .12       0
Bank Sta=4957,5013.6
XS Rating Curve= 0 ,0
Exp/Cntr=0.3,0.1

Type RM Length L Ch R = 1 ,43183   ,566,566,566
BEGIN DESCRIPTION:
KUY CREEK 27.0
END DESCRIPTION:
XS GIS Cut Line= 3
      2619875.01     13389224.97        2620225.       13388525.
        2620225.       13388075.
#Sta/Elev= 30
  4217.1   52.64  4253.4   50.66  4292.5   45.66  4351.2   43.31  4387.6   38.04
  4440.7   35.42  4516.1   27.73  4544.1   28.29  4566.5   25.89  4611.2   24.57
  4650.3   20.98  4655.9   21.74  4700.2    17.3  4717.4   15.02  4798.4   12.22
  4910.3   17.95    4941    15.2  4957.4   10.31  4958.7    9.51    5014   10.31
  5019.7   13.64  5049.7   13.18  5099.7    16.8  5189.7   31.06  5227.9   35.73
  5289.7   40.36  5339.7   46.06  5359.7   44.58  5389.7   45.06  5449.7   49.59
#Mann= 5 ,-1 , 0
  4217.1     .05       0  4700.2      .1       0  4957.4     .05       0
    5014      .1       0  5227.9     .12       0
Bank Sta=4957.4,5014
XS Rating Curve= 0 ,0
Exp/Cntr=0.3,0.1

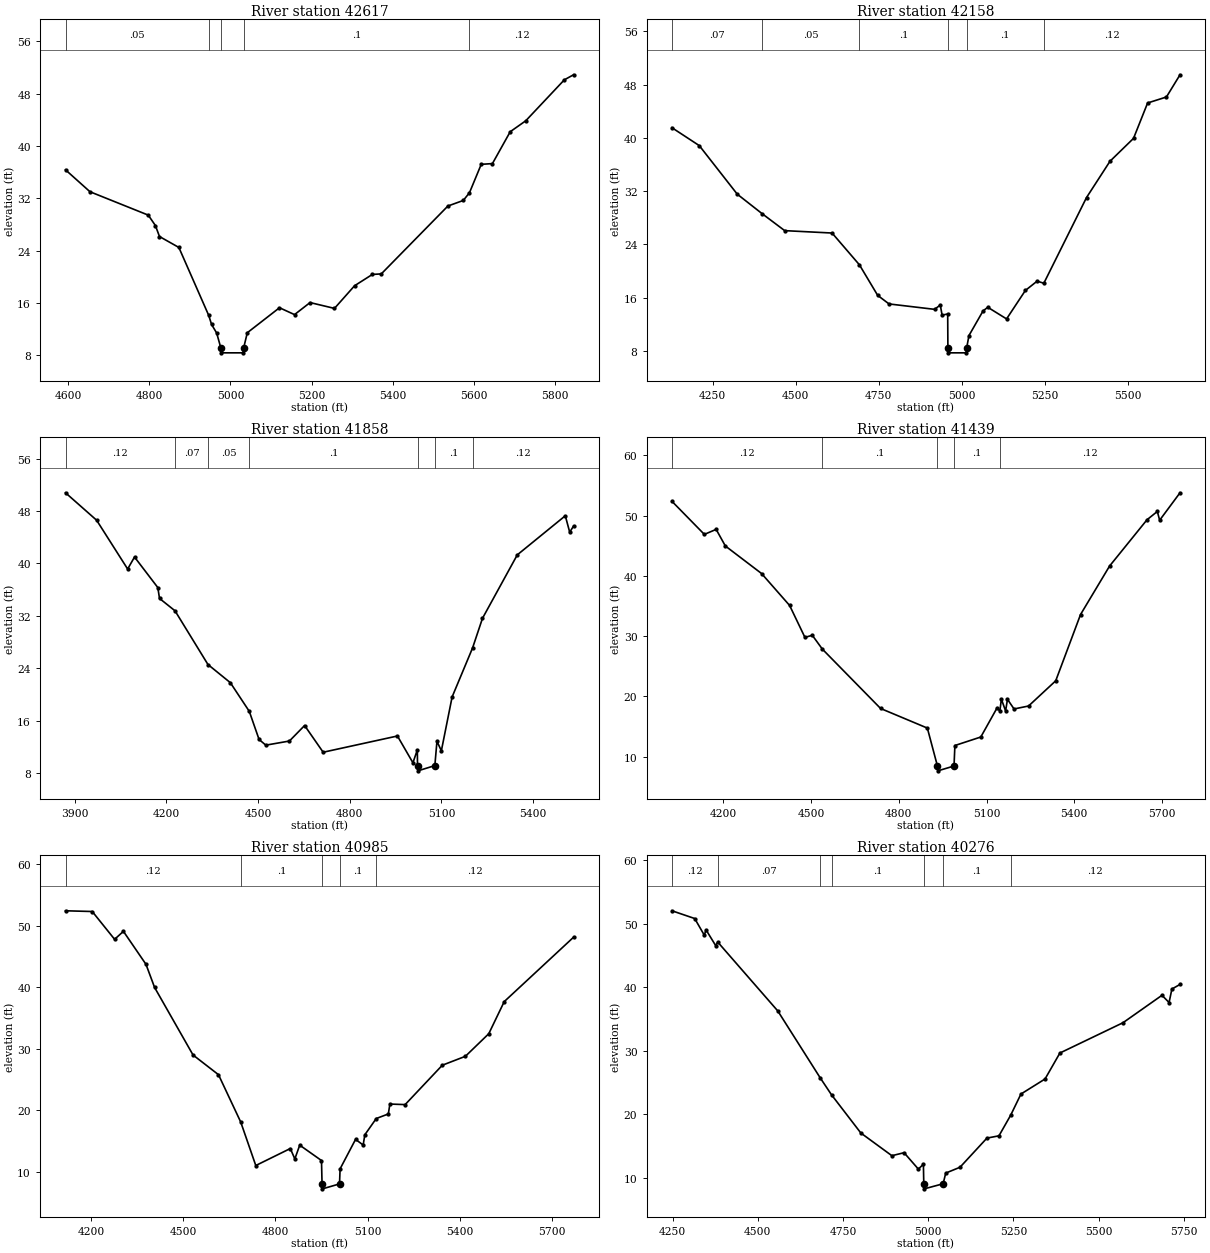
Type RM Length L Ch R = 1 ,42617   ,459,459,459
BEGIN DESCRIPTION:
KUY CREEK 26.0
END DESCRIPTION:
XS GIS Cut Line= 3
        2620725.     13389224.98        2620675.       13388825.
        2620275.     13388074.99
#Sta/Elev= 30
  4593.1   36.35  4653.5      33  4797.2   29.43  4814.8   27.84  4824.9   26.16
  4872.7   24.49  4946.4    14.1  4953.4   12.72    4966   11.41    4976    9.19
  4977.3    8.39  5031.4    8.39  5032.7    9.19  5041.5   11.46  5120.9   15.28
    5158   14.23  5196.3   16.07  5256.5   15.18  5306.1   18.64    5350   20.37
    5372   20.45  5536.3   30.82  5574.2   31.67  5589.5   32.85  5618.5   37.19
  5646.1    37.3    5690   42.17  5728.3   43.84  5823.5    50.1  5846.2   50.87
#Mann= 5 ,-1 , 0
  4593.1     .05       0  4946.4      .1       0    4976     .05       0
  5032.7      .1       0  5589.5     .12       0
Bank Sta=4976,5032.7
XS Rating Curve= 0 ,0
Exp/Cntr=0.3,0.1

Type RM Length L Ch R = 1 ,42158   ,300,300,300
BEGIN DESCRIPTION:
Mapping XS 116fc0b9
END DESCRIPTION:
XS GIS Cut Line= 3
      2621283.66     13389276.88      2620919.07     13388495.64
      2620455.54     13388016.48
#Sta/Elev= 30
  4127.6   41.53  4209.8   38.84  4324.1   31.54  4398.9   28.61  4466.8   26.06
  4609.4    25.7  4691.7   20.92  4746.6   16.33  4780.8   15.04  4917.6   14.23
    4935   14.87  4940.5   13.36  4957.3   13.53  4957.9    8.49  4959.2    7.69
  5013.3    7.69  5014.6    8.49  5021.3   10.29  5063.7   13.99  5077.9   14.54
  5134.5   12.79  5191.1   17.07  5226.5   18.47  5246.6   18.15    5375   31.03
  5445.7   36.49  5516.5   39.93  5558.9   45.25  5615.5   46.15  5656.4   49.49
#Mann= 6 ,-1 , 0
  4127.6     .07       0  4398.9     .05       0  4691.7      .1       0
  4957.9     .05       0  5014.6      .1       0  5246.6     .12       0
Bank Sta=4957.9,5014.6
XS Rating Curve= 0 ,0
Exp/Cntr=0.3,0.1

Type RM Length L Ch R = 1 ,41858   ,419,419,419
BEGIN DESCRIPTION:
Mapping XS 9b9c8b5a
END DESCRIPTION:
XS GIS Cut Line= 3
      2621590.95     13389235.23      2621085.74     13388266.47
      2620638.92     13387913.17
#Sta/Elev= 30
  3869.9   50.77  3971.7   46.58  4073.2   39.13  4095.7   40.96  4171.9    36.3
  4177.5   34.64  4228.2   32.75    4336   24.55  4409.2   21.78  4471.2    17.4
  4503.2   13.11  4525.3   12.24  4602.4   12.87  4652.2   15.24  4712.9   11.16
  4955.9   13.64  5006.6    9.55    5021   11.52  5021.6    9.12  5022.9    8.32
  5078.3    9.12  5085.2   12.83  5099.6   11.38  5134.8    19.6  5201.8   27.09
  5234.2   31.61    5348   41.29  5505.1   47.26  5519.5   44.76  5532.1   45.68
#Mann= 7 ,-1 , 0
  3869.9     .12       0  4228.2     .07       0    4336     .05       0
  4471.2      .1       0  5021.6     .05       0  5078.3      .1       0
  5201.8     .12       0
Bank Sta=5021.6,5078.3
XS Rating Curve= 0 ,0
Exp/Cntr=0.3,0.1

Type RM Length L Ch R = 1 ,41439   ,454,454,454
BEGIN DESCRIPTION:
Mapping XS 46028d73
END DESCRIPTION:
XS GIS Cut Line= 3
      2621731.57     13389089.38      2621439.91     13388146.68
      2620852.69     13387678.98
#Sta/Elev= 30
    4024   52.35  4134.7   46.87  4175.1    47.7  4206.5   44.95  4330.4   40.38
  4426.4   35.08  4478.7   29.79  4503.9   30.14  4538.4   27.84  4737.5      18
  4897.4   14.75  4931.9    8.46  4933.2    7.66  4988.6    8.46  4991.6   11.86
  5080.2   13.27  5136.2   18.13  5145.3   17.55  5150.6   19.55    5165   17.59
  5171.4   19.52  5193.9   17.92  5243.5   18.41  5336.4   22.59  5421.3   33.58
  5520.6   41.62  5648.7    49.3  5683.9   50.67  5691.9   49.22  5761.5   53.77
#Mann= 5 ,-1 , 0
    4024     .12       0  4538.4      .1       0  4931.9     .05       0
  4988.6      .1       0  5145.3     .12       0
Bank Sta=4931.9,4988.6
XS Rating Curve= 0 ,0
Exp/Cntr=0.3,0.1

Type RM Length L Ch R = 1 ,40985   ,709,709,709
BEGIN DESCRIPTION:
Mapping XS 6856926b
END DESCRIPTION:
XS GIS Cut Line= 3
      2622018.04     13388891.51      2621861.78     13388120.64
      2621757.62     13387261.28
#Sta/Elev= 30
  4117.1   52.42  4204.1    52.3  4276.8   47.78  4305.4   49.08  4378.8   43.72
  4406.8   39.96  4531.9   28.98  4614.6   25.78  4686.9   18.09  4735.9   11.02
  4848.2   13.78  4862.9   12.09  4878.8   14.33  4949.6   11.83  4951.4    8.03
  4952.7    7.23  5008.2    8.03  5010.1   10.48  5060.4   15.27  5085.1   14.35
  5090.6   16.02  5127.7   18.66    5167    19.4    5172   21.01  5221.6   20.92
  5342.5   27.32  5417.6   28.77  5493.6   32.44  5543.9   37.66  5769.3   48.12
#Mann= 5 ,-1 , 0
  4117.1     .12       0  4686.9      .1       0  4951.4     .05       0
  5008.2      .1       0  5127.7     .12       0
Bank Sta=4951.4,5008.2
XS Rating Curve= 0 ,0
Exp/Cntr=0.3,0.1

Type RM Length L Ch R = 1 ,40276   ,198,198,198
BEGIN DESCRIPTION:
Mapping XS b2a24c45
END DESCRIPTION:
XS GIS Cut Line= 4
      2622382.61     13388578.97      2622554.49     13387995.64
      2622424.28     13387808.14      2622028.44     13387287.29
#Sta/Elev= 30
  4248.1   52.03  4314.8   50.81  4342.9   48.19  4348.1   49.02  4376.3   46.55
  4382.3   47.11  4558.5   36.26  4682.4   25.77  4716.2   23.05  4802.3   17.03
  4893.3   13.46  4929.1   13.93    4971   11.35  4985.8   12.12  4986.9    9.04
  4988.2    8.24  5043.7    9.04  5051.3   10.72  5093.2   11.64  5172.2   16.23
  5207.5   16.59  5241.9   19.84    5272   23.17  5342.7   25.54  5386.3   29.63
  5571.4    34.4  5685.8   38.72  5706.6   37.58  5714.9   39.71  5738.7   40.43
#Mann= 7 ,-1 , 0
  4248.1     .12       0  4382.3     .07       0  4682.4     .12       0
  4716.2      .1       0  4986.9     .05       0  5043.7      .1       0
  5241.9     .12       0
Bank Sta=4986.9,5043.7
XS Rating Curve= 0 ,0
Exp/Cntr=0.3,0.1

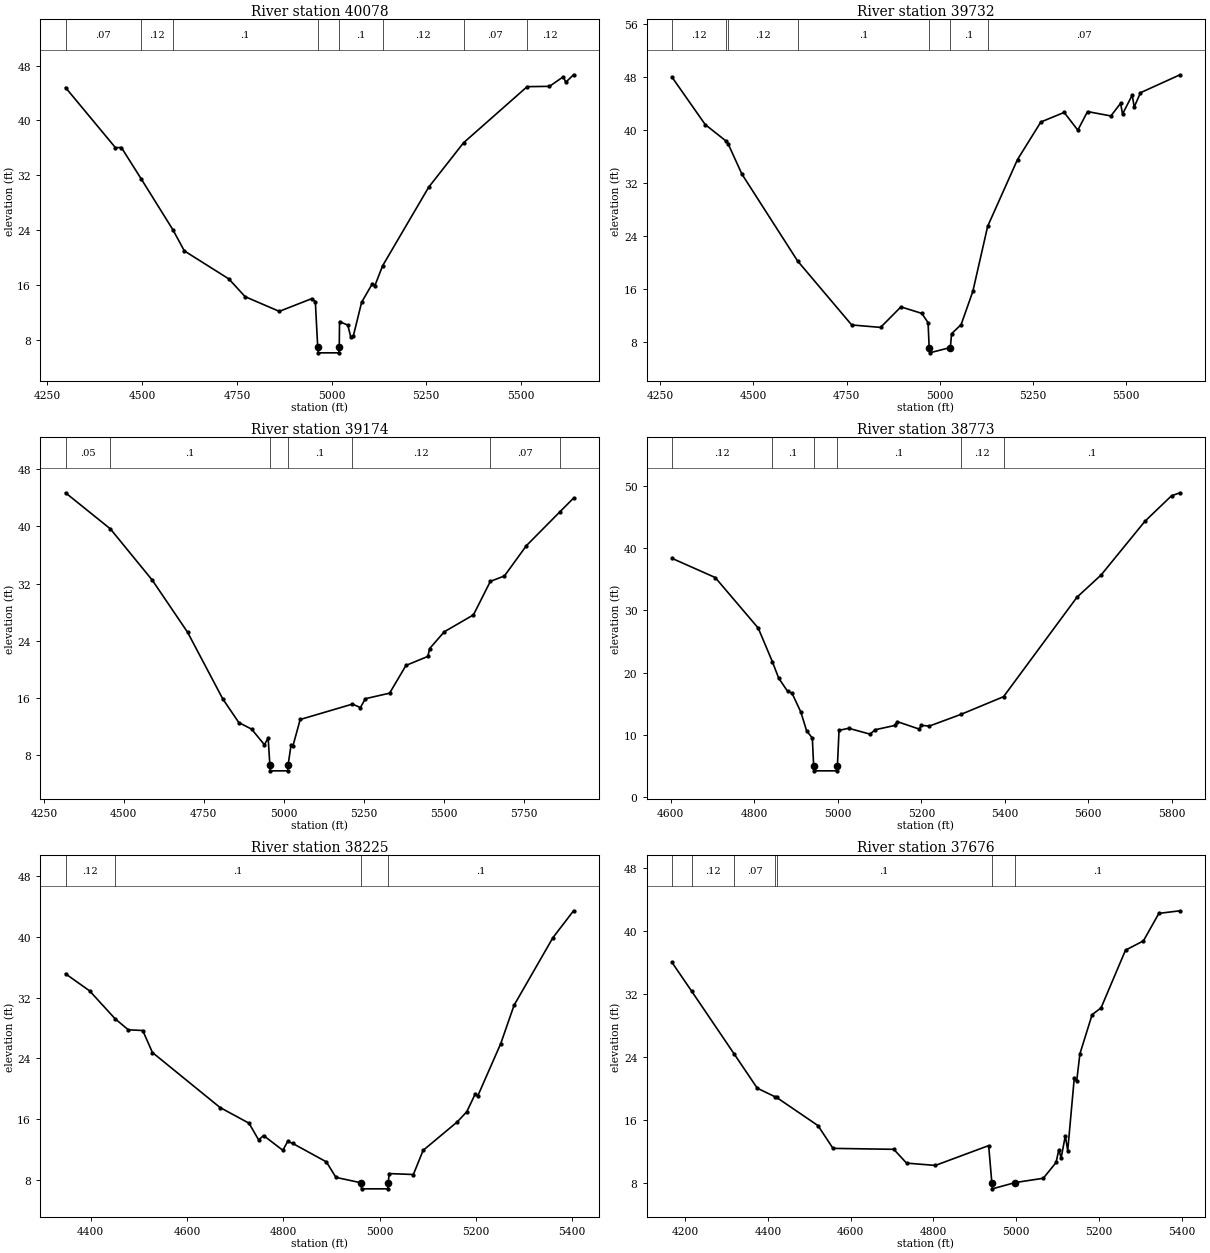
Type RM Length L Ch R = 1 ,40078   ,346,346,346
BEGIN DESCRIPTION:
Mapping XS ae6fa96e
END DESCRIPTION:
XS GIS Cut Line= 3
      2622965.97     13388344.64      2622601.37     13387719.59
      2622205.55     13387245.65
#Sta/Elev= 30
  4297.6   44.79  4429.4   36.02  4445.1   36.04    4497    31.5    4581   24.05
  4611.3   20.96  4728.8   16.87  4771.8   14.28  4861.9   12.14  4947.9      14
  4957.1   13.54  4963.4    6.89  4964.7    6.09  5018.9    6.09  5020.2    6.89
    5021   10.66  5042.8   10.12  5050.6     8.4  5057.2    8.51  5079.3   13.47
  5106.6   16.08  5114.4   15.91  5134.8    18.8  5256.3   30.25  5348.3   36.73
  5516.3   44.92  5575.1   44.96  5611.6   46.36  5618.1   45.56  5638.7   46.65
#Mann= 8 ,-1 , 0
  4297.6     .07       0    4497     .12       0    4581      .1       0
  4963.4     .05       0  5020.2      .1       0  5134.8     .12       0
  5348.3     .07       0  5516.3     .12       0
Bank Sta=4963.4,5020.2
XS Rating Curve= 0 ,0
Exp/Cntr=0.3,0.1

Type RM Length L Ch R = 1 ,39732   ,558,558,558
BEGIN DESCRIPTION:
Mapping XS 63ce948e
END DESCRIPTION:
XS GIS Cut Line= 3
      2623075.32     13388271.67      2622913.87     13387620.64
      2622689.96     13386964.54
#Sta/Elev= 30
  4281.2   47.96  4370.5   40.81  4426.9   38.31  4432.5   37.85  4468.9   33.36
  4618.4   20.28  4763.7   10.64  4841.3   10.27  4895.9   13.36    4952   12.38
  4968.8   10.98  4971.7    7.24    4973    6.44  5028.6    7.24  5031.9    9.32
  5057.5   10.69  5088.9   15.68  5128.8    25.5  5208.9   35.55  5271.6    41.2
  5334.2   42.64  5370.8   39.97  5396.9   42.77  5459.6   42.11  5485.6   44.01
  5490.9   42.41  5516.9   45.24  5522.2   43.46  5539.1   45.61  5645.2   48.31
#Mann= 7 ,-1 , 0
  4281.2     .12       0  4426.9     .07       0  4432.5     .12       0
  4618.4      .1       0  4971.7     .05       0  5028.6      .1       0
  5128.8     .07       0
Bank Sta=4971.7,5028.6
XS Rating Curve= 0 ,0
Exp/Cntr=0.3,0.1

Type RM Length L Ch R = 1 ,39174   ,401,401,401
BEGIN DESCRIPTION:
Mapping XS b04ce440
END DESCRIPTION:
XS GIS Cut Line= 3
      2623429.49     13388256.06      2623398.24     13387589.39
       2623007.6     13386756.01
#Sta/Elev= 30
  4317.6    44.7  4457.9   39.65    4589   32.47  4699.1    25.2  4809.2   15.87
  4859.3   12.57  4899.3   11.65  4939.3    9.47  4950.9   10.41  4956.3    6.62
  4957.6    5.82  5011.9    5.82  5013.2    6.62  5022.7    9.47  5028.2    9.27
  5051.1      13  5214.3   15.15  5239.2   14.67  5254.9   15.91  5330.5   16.68
  5381.7   20.56  5450.1   21.82  5455.7   22.92  5501.3   25.26  5592.6   27.63
  5645.3   32.31  5689.4   33.07  5757.9    37.3  5862.8   42.04  5905.4   43.95
#Mann= 7 ,-1 , 0
  4317.6     .05       0  4457.9      .1       0  4956.3     .05       0
  5013.2      .1       0  5214.3     .12       0  5645.3     .07       0
  5862.8     .12       0
Bank Sta=4956.3,5013.2
XS Rating Curve= 0 ,0
Exp/Cntr=0.3,0.1

Type RM Length L Ch R = 1 ,38773   ,548,548,548
BEGIN DESCRIPTION:
KUY CREEK 19.0
END DESCRIPTION:
XS GIS Cut Line= 3
      2623874.99     13387674.99        2623675.       13387325.
      2623525.01     13386525.04
#Sta/Elev= 30
  4602.7   38.33  4706.3   35.25  4809.3   27.14  4843.3   21.73  4858.2   19.12
  4879.8   16.98  4889.9   16.74  4911.5   13.65  4925.2   10.65  4938.9    9.49
  4942.1    5.03  4943.4    4.23  4997.7    4.23    4999    5.03  5002.9   10.73
  5026.1   11.06    5077   10.12  5089.7   10.83  5137.2   11.52  5142.3   12.13
  5194.9   10.93    5200   11.52  5219.5   11.42  5294.6   13.28    5397   16.13
    5573    32.1  5630.7   35.66  5735.8   44.29  5799.4   48.37  5819.7   48.85
#Mann= 6 ,-1 , 0
  4602.7     .12       0  4843.3      .1       0  4942.1     .05       0
    4999      .1       0  5294.6     .12       0    5397      .1       0
Bank Sta=4942.1,4999
XS Rating Curve= 0 ,0
Exp/Cntr=0.3,0.1

Type RM Length L Ch R = 1 ,38225   ,549,549,549
BEGIN DESCRIPTION:
KUY CREEK 18.0
END DESCRIPTION:
XS GIS Cut Line= 3
        2623975.     13387524.97        2623925.       13386875.
        2623975.       13386475.
#Sta/Elev= 30
  4347.7   35.15  4397.8   32.89  4450.5   29.23  4478.1   27.76  4508.1   27.67
  4528.2   24.77  4668.6   17.52  4728.8   15.45  4748.8   13.24  4758.9   13.83
    4799   11.88    4809   13.04  4819.1    12.8  4889.3   10.36  4909.3    8.31
  4961.1     7.6  4962.4     6.8  5016.7     6.8    5018     7.6  5019.7    8.81
  5070.1    8.69  5090.3   11.87  5160.8    15.6    5181   16.96  5198.6   19.32
  5203.7   19.03  5251.5   25.94  5279.2      31  5359.9   39.91  5402.7   43.45
#Mann= 4 ,-1 , 0
  4347.7     .12       0  4450.5      .1       0  4961.1     .05       0
    5018      .1       0
Bank Sta=4961.1,5018
XS Rating Curve= 0 ,0
Exp/Cntr=0.3,0.1

Type RM Length L Ch R = 1 ,37676   ,523,523,523
BEGIN DESCRIPTION:
KUY CREEK 17.0
END DESCRIPTION:
XS GIS Cut Line= 3
      2624574.99     13387574.97        2624375.       13386775.
        2624175.       13386425.
#Sta/Elev= 30
  4168.3   36.03  4216.2   32.35  4318.6   24.42  4374.4   20.08  4418.3   18.97
  4421.1   18.91  4521.3   15.33  4557.4   12.45  4704.3   12.33  4735.2   10.58
  4804.8   10.29  4933.6    12.8  4941.2    8.12  4942.5    7.32  4998.1    8.12
  5065.6    8.66  5096.5   10.66    5103   12.25  5108.8   11.25  5118.9   14.06
  5124.6   12.15  5140.5   21.39  5146.2   20.93  5154.1   24.44  5183.6    29.4
  5205.2   30.26  5264.3   37.58  5307.5   38.75  5344.9   42.24    5396   42.57
#Mann= 7 ,-1 , 0
  4168.3     .07       0  4216.2     .12       0  4318.6     .07       0
  4418.3     .12       0  4421.1      .1       0  4941.2     .05       0
  4998.1      .1       0
Bank Sta=4941.2,4998.1
XS Rating Curve= 0 ,0
Exp/Cntr=0.3,0.1