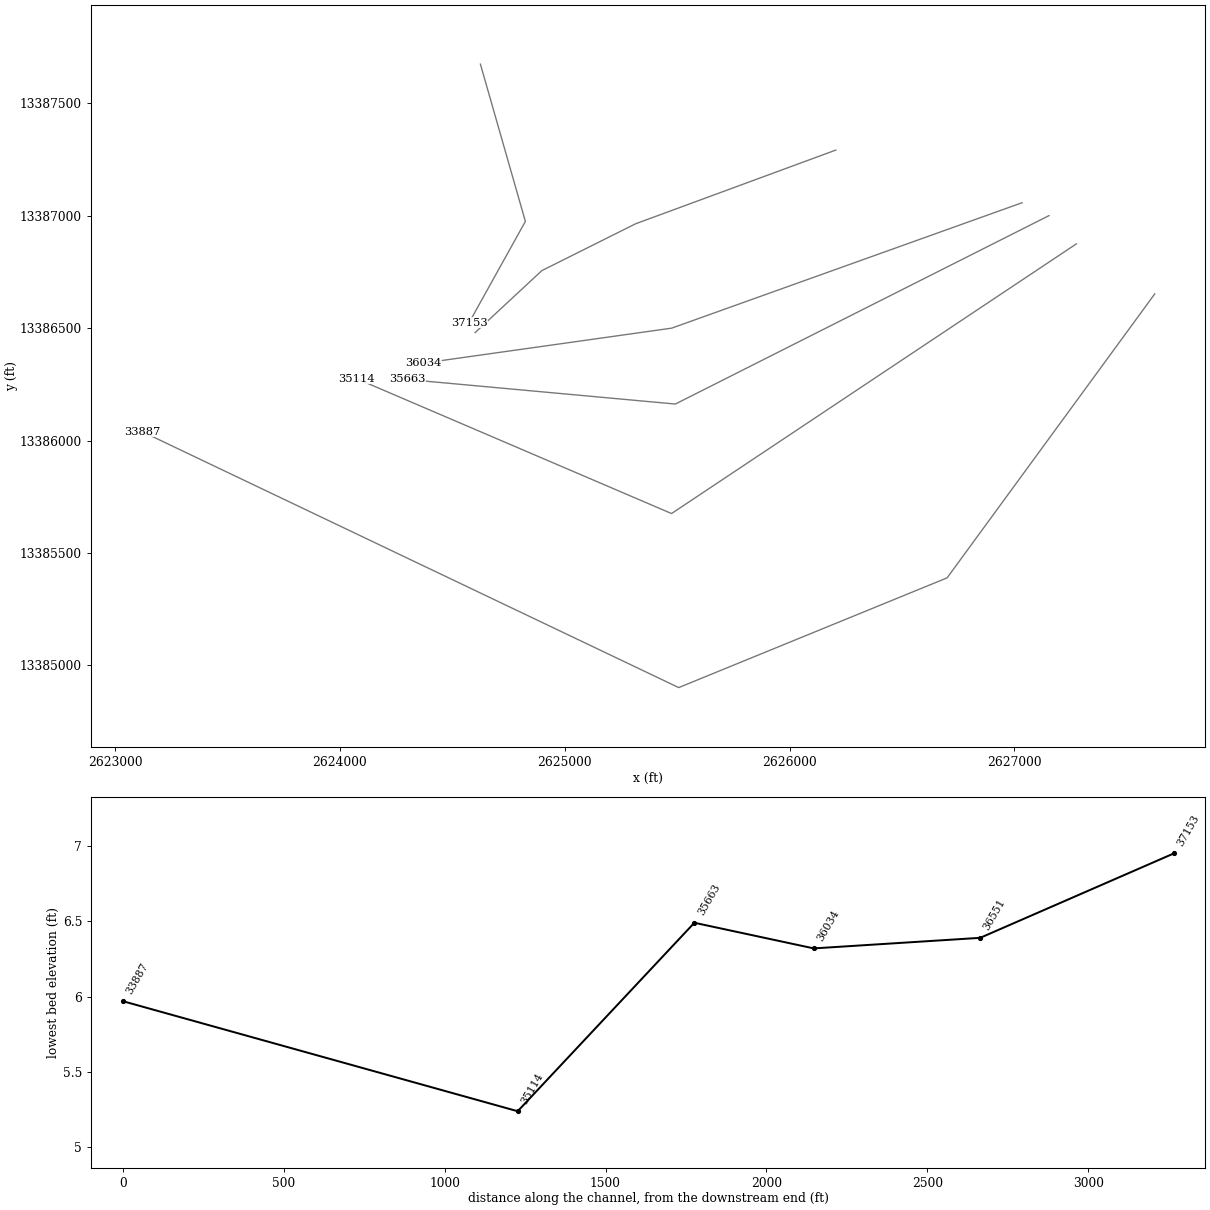
HEC-RAS study KUY CREEK.prj: KUY CREEK Base Level Engineering

--- KUY CREEK.g01 (geometry) --- (continued)

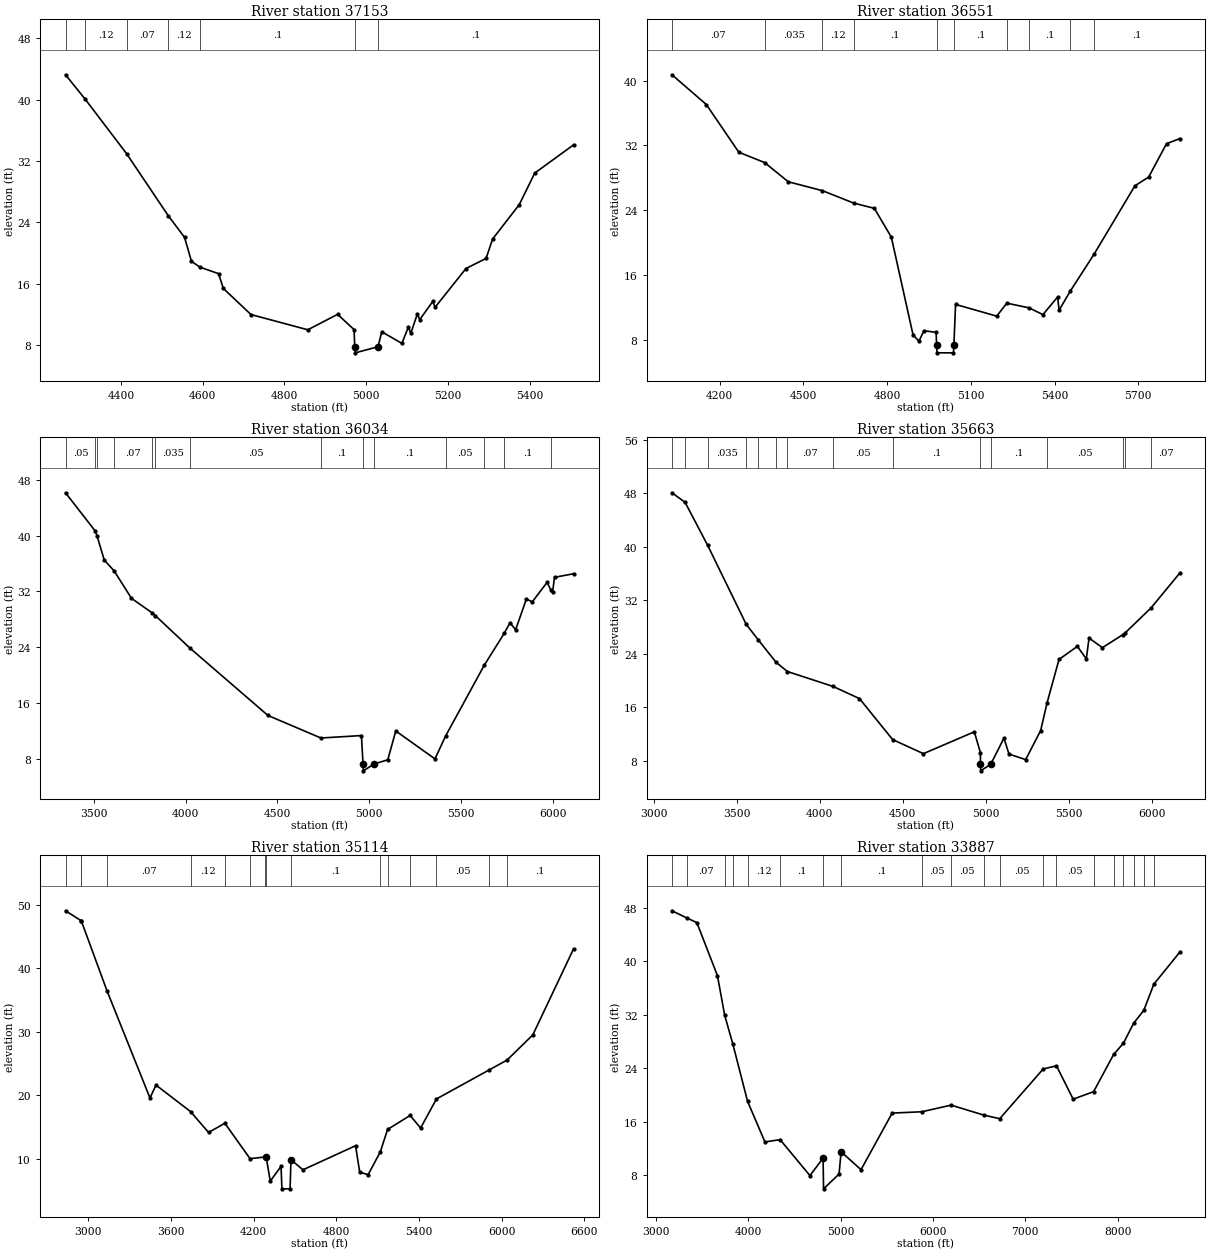
Type RM Length L Ch R = 1 ,37153   ,602,602,602
BEGIN DESCRIPTION:
KUY CREEK 16.0
END DESCRIPTION:
XS GIS Cut Line= 3
      2624625.01     13387674.97        2624825.       13386975.
      2624574.98     13386524.96
#Sta/Elev= 30
  4264.3   43.26  4311.9   40.11  4413.7   32.96  4515.5   24.87  4555.5   22.03
  4572.4    18.9  4593.5   18.13  4638.7   17.29  4650.4   15.36    4718   11.95
  4857.1    9.96  4929.9   11.98  4970.2    9.98  4971.8    7.75  4973.1    6.95
  5028.8    7.75    5038     9.7  5087.2    8.18  5103.2   10.34    5109    9.49
    5125   12.04  5130.7   11.28  5162.7   13.66  5168.4    12.9  5243.9   17.96
  5293.1   19.28  5309.2   21.82  5374.4   26.31  5412.1   30.42  5507.1   34.11
#Mann= 7 ,-1 , 0
  4264.3     .07       0  4311.9     .12       0  4413.7     .07       0
  4515.5     .12       0  4593.5      .1       0  4971.8     .05       0
  5028.8      .1       0
Bank Sta=4971.8,5028.8
XS Rating Curve= 0 ,0
Exp/Cntr=0.3,0.1

Type RM Length L Ch R = 1 ,36551   ,517,517,517
BEGIN DESCRIPTION:
Mapping XS 0112619c
END DESCRIPTION:
XS GIS Cut Line= 4
       2626205.5      13387292.5      2625314.91     13386964.39
      2624898.24     13386756.05       2624601.4     13386480.04
#Sta/Elev= 30
  4029.1   40.72  4152.1   37.05  4268.6   31.16  4361.1   29.88  4445.9   27.51
  4568.4   26.41  4680.1   24.88  4754.2   24.23  4815.1   20.67  4892.9     8.6
  4914.2    7.83  4931.6    9.12  4975.5    8.92  4977.2    7.39  4978.7    6.39
  5037.8    6.39  5039.3    7.39  5045.2   12.37  5192.7   10.92  5228.8   12.52
  5308.2   11.95  5358.2   11.11  5410.7   13.28  5416.3   11.66  5455.8   13.99
  5541.7   18.58  5687.7   27.01    5737   28.09    5801   32.21  5849.4   32.85
#Mann= 10 ,-1 , 0
  4029.1     .07       0  4361.1    .035       0  4568.4     .12       0
  4680.1      .1       0  4977.2     .05       0  5039.3      .1       0
  5228.8    .035       0  5308.2      .1       0  5455.8     .05       0
  5541.7      .1       0
Bank Sta=4977.2,5039.3
XS Rating Curve= 0 ,0
Exp/Cntr=0.3,0.1

Type RM Length L Ch R = 1 ,36034   ,371,371,371
BEGIN DESCRIPTION:
KUY CREEK 15.0
END DESCRIPTION:
XS GIS Cut Line= 3
      2627033.66     13387058.14       2625475.4       13386500.
      2624372.19     13386344.59
#Sta/Elev= 30
  3344.8   46.12  3508.2    40.6  3516.9   39.92  3555.8   36.51  3610.1   34.93
  3704.5   31.01  3816.8   28.94    3834   28.55  4023.4   23.88  4448.1   14.25
    4737   11.02  4957.9   11.37  4966.5    7.32    4968    6.32  5028.7    7.32
  5101.4     7.9  5145.1   12.03  5358.7    8.03    5417   11.32  5627.1   21.42
  5736.4   26.01  5767.9   27.52  5798.2    26.5    5857   30.91  5889.1   30.51
  5969.9    33.3  5989.2   32.27  5999.4   31.85  6010.3   34.02  6114.1   34.53
#Mann= 14 ,-1 , 0
  3344.8     .05       0  3508.2     .07       0  3516.9     .05       0
  3610.1     .07       0  3816.8     .05       0    3834    .035       0
  4023.4     .05       0    4737      .1       0  4966.5     .05       0
  5028.7      .1       0    5417     .05       0  5627.1    .035       0
  5736.4      .1       0  5989.2     .07       0
Bank Sta=4966.5,5028.7
XS Rating Curve= 0 ,0
Exp/Cntr=0.3,0.1

Type RM Length L Ch R = 1 ,35663   ,549,549,549
BEGIN DESCRIPTION:
Mapping XS df20b5b7
END DESCRIPTION:
XS GIS Cut Line= 3
      2627153.44     13387000.84      2625491.99      13386162.3
      2624299.65     13386271.64
#Sta/Elev= 30
  3110.4    48.1  3189.4   46.67  3325.6   40.22  3557.2   28.42  3628.2   26.14
  3736.7   22.74  3805.6   21.35  4079.1   19.13  4239.3    17.3  4438.7   11.17
    4624    9.06  4930.5   12.33    4967    9.23  4967.5    7.49    4969    6.49
  5029.7    7.49    5109   11.39  5139.1       9  5239.6    8.17  5329.9   12.52
  5368.4   16.66  5440.4   23.16  5550.9   25.12  5604.7   23.24  5621.2   26.36
  5701.5   24.92  5824.8   26.87  5836.7   27.09  5994.8   30.88  6168.8   36.13
#Mann= 15 ,-1 , 0
  3110.4     .05       0  3189.4     .07       0  3325.6    .035       0
  3557.2     .05       0  3628.2     .07       0  3736.7     .05       0
  3805.6     .07       0  4079.1     .05       0  4438.7      .1       0
  4967.5     .05       0  5029.7      .1       0  5368.4     .05       0
  5824.8    .035       0  5836.7      .1       0  5994.8     .07       0
Bank Sta=4967.5,5029.7
XS Rating Curve= 0 ,0
Exp/Cntr=0.3,0.1

Type RM Length L Ch R = 1 ,35114   ,1227,1227,1227
BEGIN DESCRIPTION:
KUY CREEK 14.0
END DESCRIPTION:
XS GIS Cut Line= 3
      2627275.02     13386875.01        2625475.       13385675.
      2624075.01       13386275.
#Sta/Elev= 30
  2835.4   49.08  2948.7   47.52  2950.4   47.47    3136   36.49  3448.4   19.56
  3491.9    21.6  3742.8   17.42  3873.5   14.13  3991.7   15.58  4174.4      10
  4285.2   10.26  4291.2    10.3  4321.2    6.46  4399.3    8.78  4405.8    5.24
    4465    5.24  4471.4    9.83  4558.6    8.24  4940.2   12.04  4970.2    7.86
  5031.4    7.48  5119.8   11.07  5172.4    14.6    5336   16.81  5412.2   14.83
    5527   19.41  5910.6      24  6039.3   25.54  6226.3   29.51  6521.9   43.07
#Mann= 16 ,-1 , 0
  2835.4     .05       0  2948.7     .07       0  2950.4    .035       0
    3136     .07       0  3742.8     .12       0  3991.7     .05       0
  4174.4      .1       0  4285.2     .05       0  4291.2     .03       0
  4471.4      .1       0  5119.8     .05       0  5172.4      .1       0
    5336     .07       0    5527     .05       0  5910.6    .035       0
  6039.3      .1       0
Bank Sta=4291.2,4471.4
XS Rating Curve= 0 ,0
Exp/Cntr=0.3,0.1

Type RM Length L Ch R = 1 ,33887   ,0,0,0
BEGIN DESCRIPTION:
KUY CREEK 13.0
END DESCRIPTION:
XS GIS Cut Line= 4
      2627623.82     13386652.56      2626700.39      13385388.8
      2625506.82     13384900.51       2623119.9     13386039.92
#Sta/Elev= 30
  3175.1   47.56  3333.2    46.5  3444.5   45.79  3667.2   37.86  3745.4   31.95
    3834   27.63  3993.5   19.06  4181.5   12.98  4345.5   13.33  4668.8    7.95
  4810.9   10.57  4816.1    5.97  4983.8    8.18    5006   11.51  5221.5    8.84
  5558.8    17.3  5880.5    17.5  6196.6   18.49  6548.3   17.01  6723.1   16.46
  7193.9    23.9  7337.4   24.37  7518.3   19.38  7739.7   20.51  7956.2   26.07
  8061.9   27.75  8172.8   30.74  8282.5   32.66  8392.1   36.59  8674.8   41.42
#Mann= 20 ,-1 , 0
  3175.1    .035       0  3333.2     .07       0  3745.4     .05       0
    3834     .07       0  3993.5     .12       0  4345.5      .1       0
  4810.9     .03       0    5006      .1       0  5880.5     .05       0
  6196.6     .05       0  6548.3     .07       0  6723.1     .05       0
  7193.9    .035       0  7337.4     .05       0  7739.7    .035       0
  7956.2      .1       0  8061.9     .12       0  8172.8      .1       0
  8282.5     .12       0  8392.1     .12       0
Bank Sta=4810.9,5006
XS Rating Curve= 0 ,0
Exp/Cntr=0.3,0.1

Chan Stop Cuts=-1
Use User Specified Reach Order=0
Composite Channel Slope=5