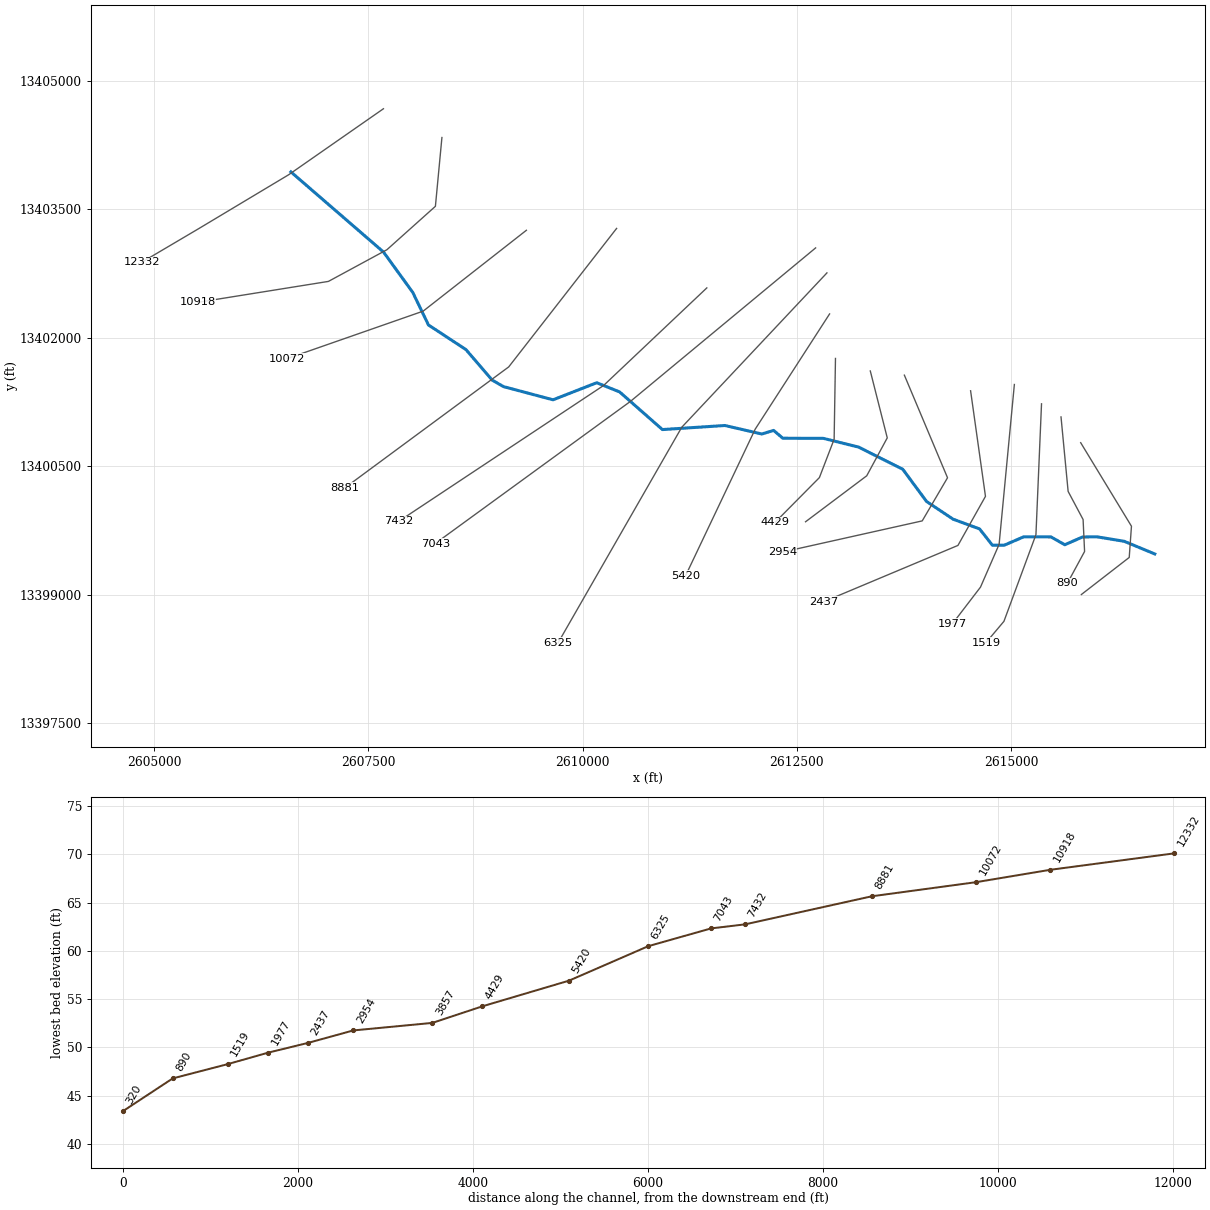
--- TRIB 1 TO DRY KUY CREEK.prj (project) ---

Proj Title=TRIB 1 TO DRY KUY CREEK Detailed Study
Current Plan=p01
Default Exp/Contr=0.3,0.1
English Units
Geom File=g01
Flow File=f01
Plan File=p01
BEGIN DESCRIPTION:
TRIB 1 TO DRY KUY CREEK
END DESCRIPTION:

--- TRIB 1 TO DRY KUY CREEK.p01 (plan) ---

Plan Title=Multiple Run
Short Identifier=Multiple
Geom File=g01
Flow File=f01
Subcritical Flow
K Sum by GR= 0
Std Step Tol= 0.01
Critical Tol= 0.01
Num of Std Step Trials= 20
Max Error Tol= 0.3
Flow Tol Ratio= 0.001
Split Flow NTrial= 30
Split Flow Tol= 0.02
Split Flow Ratio= 0.02
Log Output Level= 0
Friction Slope Method= 1
Unsteady Friction Slope Method= 2
Unsteady Bridges Friction Slope Method= 1
Parabolic Critical Depth
Global Vel Dist=  1 , 1 , 1
Global Log Level= 0
CheckData=True
Encroach Param= -1, 0, 0, 0
BEGIN DESCRIPTION:
Multiple Run
END DESCRIPTION:

--- TRIB 1 TO DRY KUY CREEK.f01 (steady flow) ---

Flow Title=Multiple
Number of Profiles=4
Profile Names=10-year,50-year,100-year,500-year
River Rch & RM= TRIB 1 TO DRY KU,Reach-1,12332
     300     500     600     700
Boundary for River Rch & Prof#=TRIB 1 TO DRY KU,Reach-1,1
Up Type=0
Dn Type=3
Dn Slope=0.005
Boundary for River Rch & Prof#=TRIB 1 TO DRY KU,Reach-1,2
Up Type=0
Dn Type=3
Dn Slope=0.005
Boundary for River Rch & Prof#=TRIB 1 TO DRY KU,Reach-1,3
Up Type=0
Dn Type=3
Dn Slope=0.005
Boundary for River Rch & Prof#=TRIB 1 TO DRY KU,Reach-1,4
Up Type=0
Dn Type=3
Dn Slope=0.005

--- TRIB 1 TO DRY KUY CREEK.g01 (geometry) ---

Geom Title=Existing Conditions

River Reach=TRIB 1 TO DRY KU,Reach-1
Reach XY= 30
      2606596.24     13403935.35      2607677.09     13402999.55
      2608018.92     13402527.20      2608201.29     13402148.18
      2608638.21     13401861.37      2608944.77     13401504.58
      2609076.56     13401428.76      2609654.82     13401274.72
      2610164.45     13401473.90      2610431.06     13401366.86
      2610930.93     13400927.24      2611659.85     13400974.64
      2612090.28     13400875.39      2612228.41     13400917.19
      2612335.43     13400826.06      2612809.78     13400824.48
      2613219.07     13400722.75      2613734.68     13400464.22
      2614011.76     13400088.61      2614322.70     13399880.83
      2614631.19     13399767.15      2614780.68     13399576.97
      2614919.06     13399577.25      2615145.03     13399674.93
      2615464.50     13399673.80      2615624.99     13399582.53
      2615830.94     13399672.74      2616000.08     13399675.20
      2616319.07     13399622.76      2616675.00     13399475.00

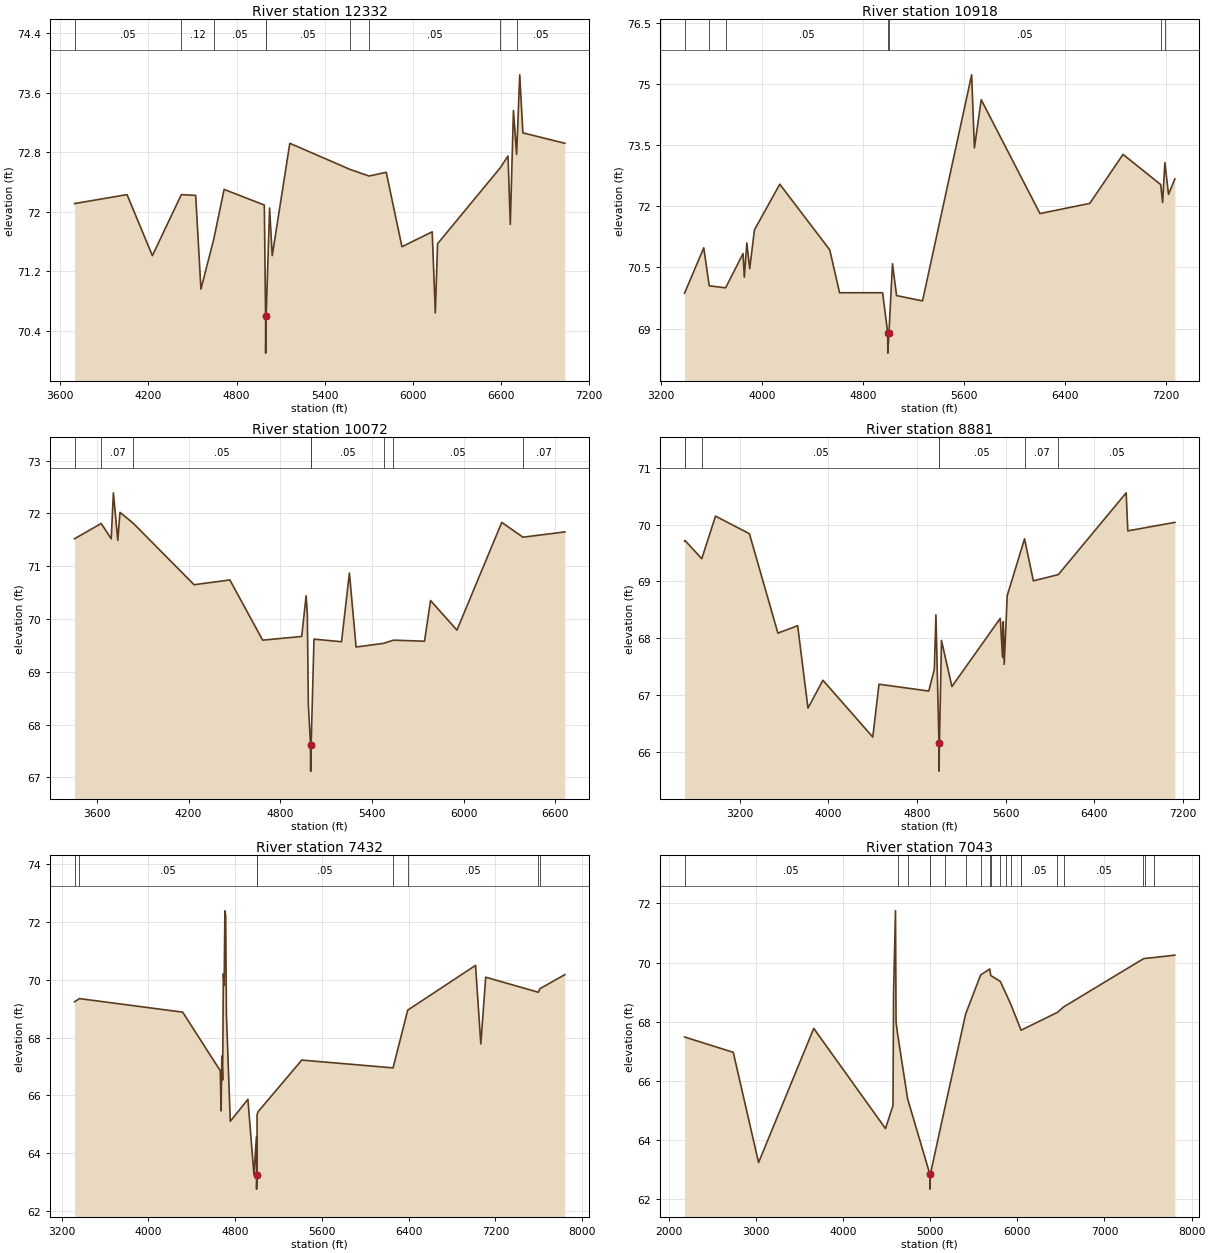
Type RM Length L Ch R = 1,12332,1414,1414,1414
BEGIN DESCRIPTION:
TRIB 1 TO DRY KUY CREEK 21.0
END DESCRIPTION:
XS GIS Cut Line= 4
      2607676.09     13404672.47      2606571.19     13403902.46
      2605518.54     13403271.43      2604858.58     13402881.69
#Sta/Elev= 30
  3696.5   72.11  4054.0   72.23  4226.8   71.41  4424.0   72.23  4521.7   72.22
  4557.5   70.96  4644.8   71.63  4715.4   72.30  4989.4   72.09  4998.0   70.60
  4998.3   70.10  5002.0   70.60  5025.2   72.05  5043.2   71.41  5163.0   72.92
  5572.1   72.57  5702.4   72.48  5820.0   72.53  5927.0   71.53  6133.1   71.73
  6154.4   70.64  6169.7   71.57  6596.5   72.59  6649.6   72.75  6665.2   71.83
  6686.6   73.36  6708.2   72.77  6729.5   73.84  6751.0   73.06  7037.0   72.92
#Mann=9,-1,0
  3696.5    0.05       0  4424.0    0.12       0  4644.8    0.05       0
  4998.0    0.05       0  5002.0    0.05       0  5572.1   0.035       0
  5702.4    0.05       0  6596.5   0.035       0  6708.2    0.05       0
Bank Sta=4998,5002
Exp/Cntr=0.3,0.1

Type RM Length L Ch R = 1,10918,846,846,846
BEGIN DESCRIPTION:
Mapping XS d97ab103
END DESCRIPTION:
XS GIS Cut Line= 5
      2608358.40     13404336.55      2608282.44     13403533.55
      2607716.45     13403026.64      2607034.16     13402656.85
      2605509.10     13402412.21
#Sta/Elev= 30
  3384.6   69.87  3536.8   70.98  3580.3   70.05  3710.1   70.00  3848.2   70.84
  3858.3   70.26  3878.3   71.10  3901.0   70.47  3938.6   71.42  4139.5   72.54
  4535.7   70.93  4613.4   69.88  4954.7   69.88  4995.0   68.90  4995.8   68.40
  5005.0   68.90  5032.9   70.59  5065.3   69.81  5271.1   69.68  5660.5   75.22
  5682.4   73.43  5736.3   74.61  6202.2   71.82  6597.2   72.07  6860.5   73.27
  7159.4   72.53  7174.5   72.09  7192.2   73.07  7221.2   72.29  7271.6   72.67
#Mann=7,-1,0
  3384.6    0.05       0  3580.3    0.12       0  3710.1    0.05       0
  4995.0    0.05       0  5005.0    0.05       0  7159.4   0.035       0
  7192.2    0.05       0
Bank Sta=4995,5005
Exp/Cntr=0.3,0.1

Type RM Length L Ch R = 1,10072,1191,1191,1191
BEGIN DESCRIPTION:
Mapping XS 80ac0b10
END DESCRIPTION:
XS GIS Cut Line= 3
      2609343.81     13403253.72      2608139.41     13402309.73
      2606555.24     13401756.36
#Sta/Elev= 30
  3454.0   71.52  3628.4   71.81  3693.9   71.52  3708.1   72.39  3737.0   71.49
  3751.4   72.02  3839.6   71.81  4236.0   70.65  4470.2   70.74  4684.9   69.60
  4940.3   69.67  4969.2   70.44  4977.2   70.09  4983.7   68.39  4998.0   67.62
  4998.3   67.12  5001.8   67.12  5002.0   67.62  5020.7   69.62  5200.9   69.57
  5252.4   70.87  5296.1   69.47  5476.5   69.54  5540.3   69.60  5743.9   69.58
  5783.4   70.35  5956.0   69.79  6249.4   71.83  6388.1   71.55  6662.3   71.65
#Mann=8,-1,0
  3454.0    0.05       0  3628.4    0.07       0  3839.6    0.05       0
  4998.0    0.05       0  5002.0    0.05       0  5476.5    0.12       0
  5540.3    0.05       0  6388.1    0.07       0
Bank Sta=4998,5002
Exp/Cntr=0.3,0.1

Type RM Length L Ch R = 1,8881,1449,1449,1449
BEGIN DESCRIPTION:
Mapping XS e0d712f8
END DESCRIPTION:
XS GIS Cut Line= 3
      2610396.37     13403275.46      2609137.68     13401658.69
      2607227.92     13400248.07
#Sta/Elev= 30
  2702.9   69.71  2707.2   69.72  2858.1   69.40  2982.3   70.15  3287.9   69.84
  3544.9   68.09  3723.1   68.22  3816.3   66.77  3951.1   67.26  4400.8   66.26
  4456.9   67.19  4905.9   67.07  4956.0   67.45  4970.6   68.41  4997.8   66.16
  4998.1   65.66  5002.2   66.16  5020.7   67.96  5114.7   67.15  5550.8   68.35
  5571.9   67.66  5578.2   68.29  5586.6   67.54  5613.6   68.75  5770.0   69.75
  5849.6   69.01  6074.5   69.12  6686.8   70.56  6701.4   69.89  7126.1   70.04
#Mann=7,-1,0
  2702.9    0.05       0  2707.2    0.07       0  2858.1    0.05       0
  4997.8    0.05       0  5002.2    0.05       0  5770.0    0.07       0
  6074.5    0.05       0
Bank Sta=4997.8,5002.2
Exp/Cntr=0.3,0.1

Type RM Length L Ch R = 1,7432,389,389,389
BEGIN DESCRIPTION:
Mapping XS 3572ca49
END DESCRIPTION:
XS GIS Cut Line= 3
      2611448.84     13402580.97      2610244.45     13401441.68
      2607858.69     13399858.40
#Sta/Elev= 30
  3319.7   69.24  3364.4   69.35  4316.8   68.88  4663.5   66.85  4670.8   65.46
  4677.6   67.36  4684.9   66.53  4691.8   70.21  4699.1   69.80  4706.0   72.39
  4713.2   72.23  4720.1   68.78  4755.7   65.10  4918.3   65.86  4973.8   63.25
  4996.8   64.57  4997.6   63.25  4998.0   62.75  5002.4   63.25  5002.8   65.33
  5011.8   65.43  5414.8   67.22  6256.6   66.95  6391.8   68.95  7017.2   70.50
  7065.8   67.78  7110.9   70.09  7596.1   69.57  7609.8   69.69  7840.9   70.18
#Mann=8,-1,0
  3319.7    0.07       0  3364.4    0.05       0  4997.6    0.05       0
  5002.4    0.05       0  6256.6    0.07       0  6391.8    0.05       0
  7596.1    0.07       0  7609.8    0.05       0
Bank Sta=4997.6,5002.4
Exp/Cntr=0.3,0.1

Type RM Length L Ch R = 1,7043,718,718,718
BEGIN DESCRIPTION:
Mapping XS 12bac251
END DESCRIPTION:
XS GIS Cut Line= 3
      2612718.36     13403048.02      2610559.12     13401257.22
      2608280.48     13399597.07
#Sta/Elev= 30
  2183.1   67.48  2741.8   66.96  3032.2   63.23  3665.1   67.77  4488.1   64.38
  4574.1   65.16  4580.6   68.99  4602.7   71.75  4609.2   67.99  4626.0   67.60
  4741.5   65.39  4997.6   62.83  4998.0   62.33  5002.4   62.83  5173.1   65.14
  5407.8   68.26  5579.5   69.58  5684.4   69.78  5695.1   69.56  5805.6   69.36
  5869.3   68.95  5924.8   68.59  6043.4   67.71  6043.9   67.71  6458.3   68.31
  6533.2   68.50  7447.6   70.13  7467.9   70.14  7570.2   70.17  7807.6   70.25
#Mann=20,-1,0
  2183.1    0.05       0  4626.0    0.07       0  4741.5    0.05       0
  4997.6    0.05       0  5002.4    0.05       0  5173.1   0.035       0
  5407.8    0.05       0  5579.5   0.035       0  5684.4    0.05       0
  5695.1   0.035       0  5805.6    0.05       0  5869.3   0.035       0
  5924.8    0.05       0  6043.4   0.035       0  6043.9    0.05       0
  6458.3    0.07       0  6533.2    0.05       0  7447.6    0.07       0
  7467.9    0.05       0  7570.2   0.035       0
Bank Sta=4997.6,5002.4
Exp/Cntr=0.3,0.1

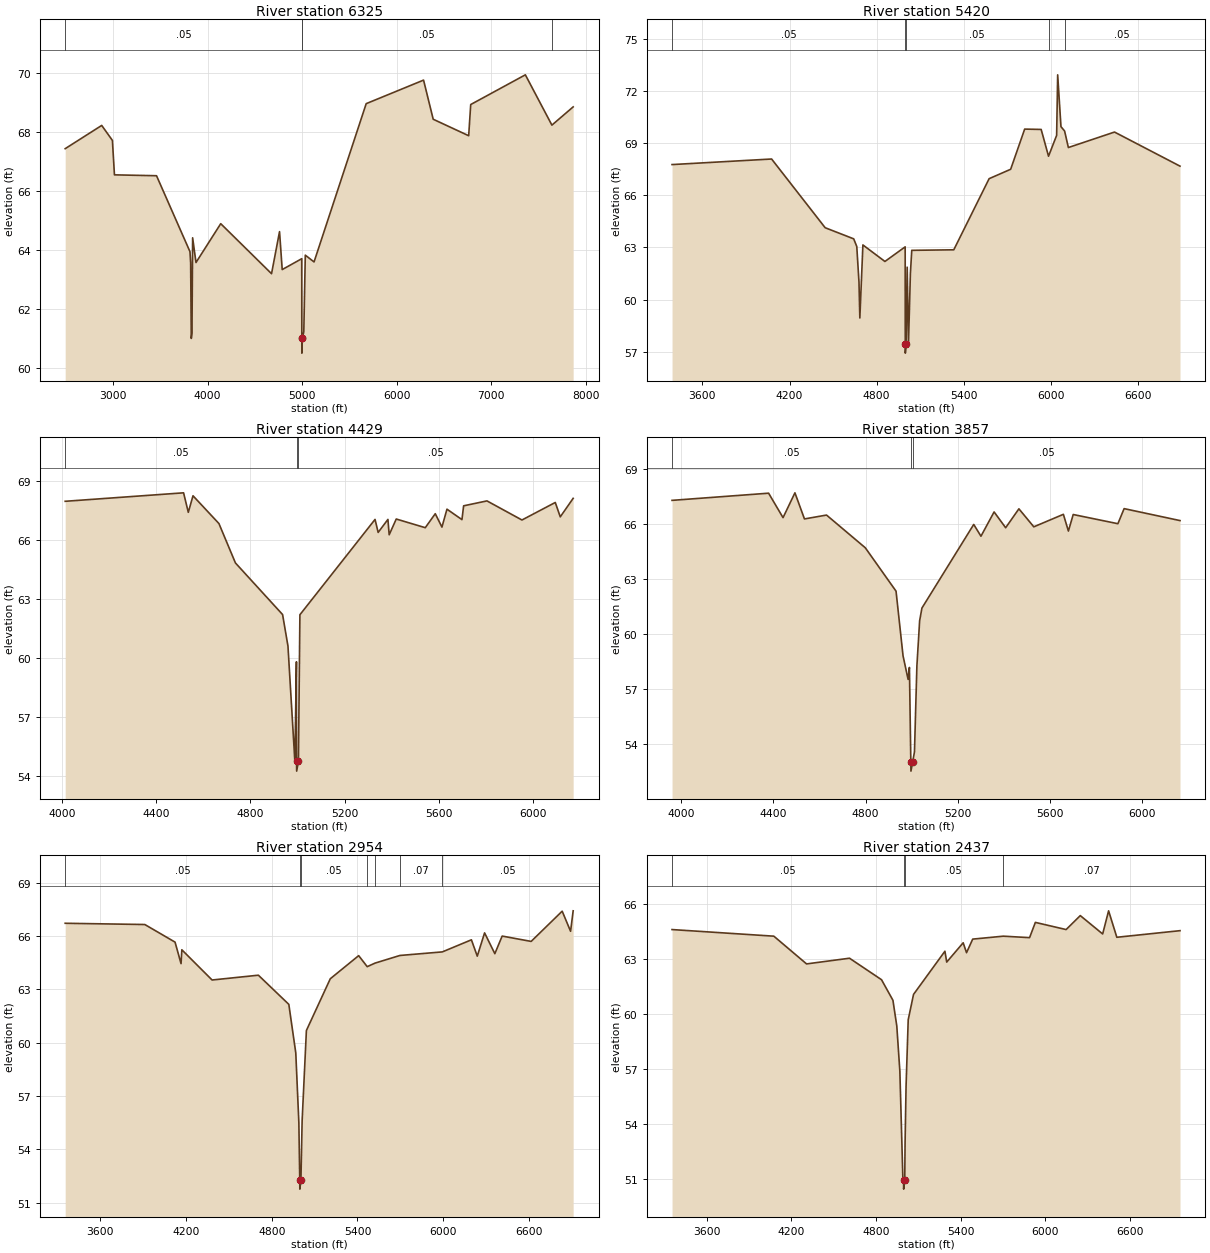
Type RM Length L Ch R = 1,6325,905,905,905
BEGIN DESCRIPTION:
Mapping XS d23b2095
END DESCRIPTION:
XS GIS Cut Line= 3
      2612850.29     13402756.33      2611155.91     13400953.40
      2609712.79     13398436.08
#Sta/Elev= 30
  2493.1   67.44  2879.6   68.23  2992.9   67.72  3014.4   66.55  3459.8   66.52
  3813.5   63.94  3820.8   63.56  3827.6   60.99  3834.9   61.17  3841.8   64.41
  3877.4   63.57  4139.2   64.89  4676.9   63.19  4761.5   64.62  4789.8   63.33
  4996.7   63.70  4997.3   60.99  4997.8   60.49  5002.7   60.99  5018.3   61.22
  5034.1   63.82  5126.8   63.59  5678.6   68.97  6285.7   69.77  6387.8   68.44
  6763.2   67.88  6784.8   68.94  7363.0   69.95  7643.9   68.24  7868.9   68.86
#Mann=4,-1,0
  2493.1    0.05       0  4997.3    0.05       0  5002.7    0.05       0
  7643.9    0.07       0
Bank Sta=4997.3,5002.7
Exp/Cntr=0.3,0.1

Type RM Length L Ch R = 1,5420,991,991,991
BEGIN DESCRIPTION:
Mapping XS 021d6fca
END DESCRIPTION:
XS GIS Cut Line= 3
      2612881.18     13402277.19      2612013.11     13400931.70
      2611199.30     13399217.26
#Sta/Elev= 30
  3390.8   67.76  4076.6   68.08  4445.5   64.13  4642.2   63.49  4663.3   63.05
  4678.5   61.00  4684.4   58.94  4705.5   63.14  4857.2   62.19  4996.6   63.03
  4997.3   57.42  4997.7   56.92  5002.8   57.42  5010.5   61.86  5019.3   57.42
  5032.6   61.49  5042.0   62.83  5331.5   62.86  5575.0   66.95  5723.3   67.49
  5819.8   69.80  5933.4   69.78  5984.1   68.24  6040.0   69.44  6047.1   72.92
  6069.8   69.94  6094.8   69.69  6120.8   68.74  6438.5   69.63  6889.8   67.67
#Mann=5,-1,0
  3390.8    0.05       0  4997.3    0.05       0  5002.8    0.05       0
  5984.1    0.07       0  6094.8    0.05       0
Bank Sta=4997.3,5002.8
Exp/Cntr=0.3,0.1

Type RM Length L Ch R = 1,4429,572,572,572
BEGIN DESCRIPTION:
Mapping XS fcae9985
END DESCRIPTION:
XS GIS Cut Line= 4
      2612949.86     13401757.35      2612934.23     13400814.59
      2612762.36     13400366.68      2612246.76     13399845.87
#Sta/Elev= 30
  4014.3   67.96  4516.7   68.39  4536.7   67.40  4556.7   68.24  4666.7   66.83
  4736.7   64.83  4936.8   62.21  4959.6   60.61  4988.9   54.76  4995.6   59.81
  4996.0   54.76  4996.5   54.26  5004.0   54.76  5010.3   62.20  5329.1   67.04
  5342.3   66.38  5383.8   67.04  5389.1   66.26  5419.1   67.06  5542.3   66.62
  5584.7   67.33  5613.0   66.65  5634.3   67.56  5697.9   67.03  5705.0   67.73
  5804.0   67.98  5952.5   67.01  6093.9   67.90  6115.1   67.17  6169.8   68.11
#Mann=3,-1,0
  4014.3    0.05       0  4996.0    0.05       0  5004.0    0.05       0
Bank Sta=4996,5004
Exp/Cntr=0.3,0.1

Type RM Length L Ch R = 1,3857,903,903,903
BEGIN DESCRIPTION:
Mapping XS ae1a766a
END DESCRIPTION:
XS GIS Cut Line= 4
      2613356.12     13401611.42      2613554.02     13400830.22
      2613314.44     13400387.51      2612600.88     13399851.03
#Sta/Elev= 30
  3960.9   67.27  4379.5   67.66  4442.1   66.33  4493.6   67.68  4534.9   66.26
  4630.6   66.47  4798.7   64.69  4931.9   62.33  4962.3   58.81  4984.2   57.53
  4989.9   58.18  4996.0   53.04  4996.5   52.54  5004.1   53.04  5011.8   53.59
  5022.3   58.26  5034.2   60.72  5044.1   61.41  5268.7   65.96  5300.0   65.32
  5357.0   66.64  5407.1   65.78  5464.5   66.81  5529.1   65.83  5657.3   66.51
  5679.1   65.60  5699.9   66.50  5893.6   66.00  5920.6   66.82  6162.9   66.17
#Mann=3,-1,0
  3960.9    0.05       0  4996.0    0.05       0  5004.1    0.05       0
Bank Sta=4996,5004.1
Exp/Cntr=0.3,0.1

Type RM Length L Ch R = 1,2954,517,517,517
BEGIN DESCRIPTION:
Mapping XS 14381053
END DESCRIPTION:
XS GIS Cut Line= 4
      2613753.63     13401562.56      2614257.10     13400364.64
      2613961.96     13399861.16      2612330.02     13399496.58
#Sta/Elev= 30
  3354.2   66.71  3911.4   66.64  4123.1   65.65  4165.1   64.44  4170.6   65.22
  4382.3   63.52  4706.3   63.79  4919.4   62.15  4968.1   59.42  4989.6   55.50
  4995.9   52.26  4996.4   51.76  5004.1   52.26  5012.5   55.61  5042.4   60.68
  5209.6   63.59  5408.3   64.89  5468.0   64.27  5522.8   64.47  5697.1   64.90
  5993.7   65.10  6197.3   65.78  6238.3   64.86  6289.5   66.17  6361.2   65.00
  6412.5   65.99  6615.4   65.69  6832.6   67.39  6891.3   66.26  6909.4   67.41
#Mann=7,-1,0
  3354.2    0.05       0  4995.9    0.05       0  5004.1    0.05       0
  5468.0    0.07       0  5522.8    0.05       0  5697.1    0.07       0
  5993.7    0.05       0
Bank Sta=4995.9,5004.1
Exp/Cntr=0.3,0.1

Type RM Length L Ch R = 1,2437,460,460,460
BEGIN DESCRIPTION:
Mapping XS 4c46add9
END DESCRIPTION:
XS GIS Cut Line= 4
      2614526.21     13401380.21      2614699.81     13400147.62
      2614378.63     13399574.71      2612808.76     13398915.54
#Sta/Elev= 30
  3353.1   64.60  4075.4   64.24  4307.5   62.73  4612.3   63.04  4839.4   61.87
  4920.4   60.75  4947.8   59.35  4969.5   56.89  4991.2   50.97  4995.9   50.97
  4996.4   50.47  5004.2   50.97  5006.5   52.96  5013.6   56.08  5028.8   59.69
  5066.5   61.07  5289.2   63.42  5302.0   62.83  5418.8   63.88  5442.6   63.34
  5486.4   64.08  5703.6   64.24  5889.9   64.16  5931.0   64.99  6149.2   64.60
  6249.7   65.36  6408.5   64.36  6450.6   65.62  6509.0   64.18  6957.3   64.54
#Mann=4,-1,0
  3353.1    0.05       0  4995.9    0.05       0  5004.2    0.05       0
  5703.6    0.07       0
Bank Sta=4995.9,5004.2
Exp/Cntr=0.3,0.1

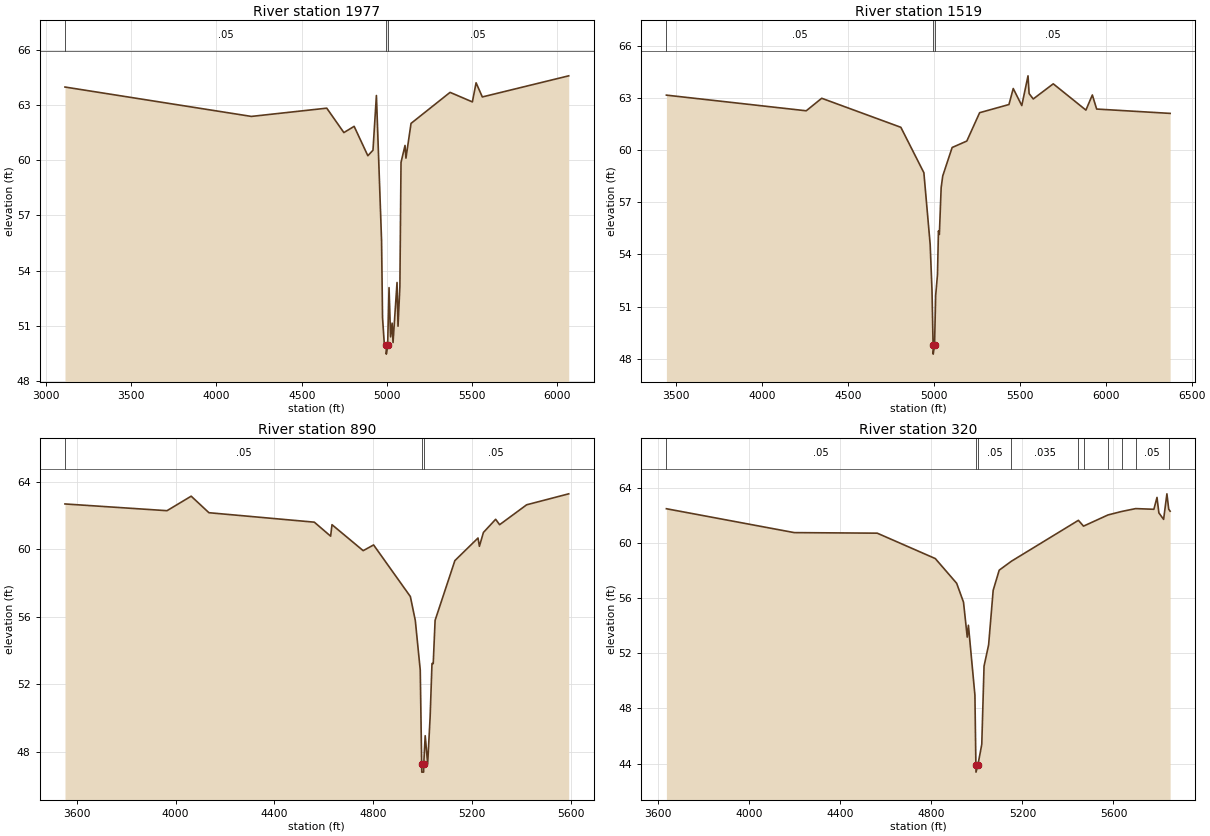
Type RM Length L Ch R = 1,1977,458,458,458
BEGIN DESCRIPTION:
Mapping XS f0fc1b14
END DESCRIPTION:
XS GIS Cut Line= 4
      2615036.88     13401453.48      2614858.93     13399587.12
      2614641.91     13399087.99      2614316.39     13398662.65
#Sta/Elev= 30
  3111.5   63.99  4204.9   62.39  4646.9   62.84  4747.4   61.51  4807.6   61.85
  4888.0   60.25  4918.1   60.55  4938.2   63.53  4968.4   55.64  4974.2   51.43
  4984.9   49.95  4995.8   49.95  4996.3   49.45  5004.2   49.95  5012.3   53.07
  5021.3   50.39  5030.3   51.14  5035.7   50.08  5059.2   53.35  5065.0   50.97
  5075.9   53.13  5082.6   59.89  5106.1   60.81  5111.5   60.12  5141.3   62.01
  5370.3   63.70  5501.1   63.18  5522.9   64.22  5559.5   63.45  6066.2   64.60
#Mann=3,-1,0
  3111.5    0.05       0  4995.8    0.05       0  5004.2    0.05       0
Bank Sta=4995.8,5004.2
Exp/Cntr=0.3,0.1

Type RM Length L Ch R = 1,1519,629,629,629
BEGIN DESCRIPTION:
Mapping XS 4fcbb2a4
END DESCRIPTION:
XS GIS Cut Line= 4
      2615353.72     13401227.79      2615288.61     13399699.97
      2614915.35     13398688.69      2614707.02     13398441.30
#Sta/Elev= 30
  3444.2   63.16  4257.7   62.26  4347.8   62.98  4808.2   61.31  4942.1   58.70
  4978.7   54.58  4989.4   51.93  4995.8   48.77  4996.3   48.27  5004.2   48.77
  5010.7   51.64  5021.3   52.84  5026.9   55.35  5032.2   55.15  5042.7   57.85
  5052.0   58.52  5106.6   60.15  5191.9   60.52  5266.5   62.15  5437.1   62.62
  5462.0   63.54  5511.7   62.56  5548.0   64.27  5554.3   63.25  5578.4   62.94
  5694.8   63.81  5884.8   62.30  5922.2   63.17  5947.3   62.36  6374.8   62.11
#Mann=3,-1,0
  3444.2    0.05       0  4995.8    0.05       0  5004.2    0.05       0
Bank Sta=4995.8,5004.2
Exp/Cntr=0.3,0.1

Type RM Length L Ch R = 1,890,570,570,570
BEGIN DESCRIPTION:
Mapping XS a1b16b59
END DESCRIPTION:
XS GIS Cut Line= 5
      2615581.15     13401074.99      2615664.15     13400205.34
      2615838.75     13399877.09      2615856.11     13399503.83
      2615656.47     13399134.94
#Sta/Elev= 30
  3552.4   62.69  3965.3   62.29  4063.1   63.15  4135.0   62.17  4561.4   61.61
  4627.4   60.78  4633.0   61.46  4759.2   59.92  4801.3   60.26  4950.1   57.20
  4970.1   55.78  4990.1   52.84  4995.8   47.29  4996.3   46.79  5003.8   46.79
  5004.3   47.29  5010.1   48.95  5020.1   47.29  5030.1   50.07  5037.6   53.23
  5042.6   53.22  5050.2   55.79  5130.2   59.33  5223.8   60.67  5229.5   60.18
  5245.7   61.00  5295.2   61.78  5311.3   61.46  5420.7   62.64  5590.9   63.29
#Mann=3,-1,0
  3552.4    0.05       0  4995.8    0.05       0  5004.3    0.05       0
Bank Sta=4995.8,5004.3
Exp/Cntr=0.3,0.1

Type RM Length L Ch R = 1,320,0,0,0
BEGIN DESCRIPTION:
Mapping XS 55e6636f
END DESCRIPTION:
XS GIS Cut Line= 4
      2615810.64     13400773.96      2616402.98     13399798.97
      2616376.94     13399434.39      2615818.52     13399001.50
#Sta/Elev= 30
  3636.1   62.47  4197.9   60.74  4562.2   60.70  4817.4   58.86  4911.2   57.07
  4941.3   55.70  4957.7   53.17  4962.8   54.03  4991.4   48.97  4995.7   43.89
  4996.2   43.39  5004.3   43.89  5021.5   45.40  5031.5   51.07  5051.6   52.61
  5071.6   56.56  5098.1   58.02  5151.9   58.67  5446.0   61.63  5468.5   61.21
  5576.0   62.02  5635.5   62.27  5697.7   62.48  5777.5   62.43  5791.3   63.29
  5799.5   62.17  5820.3   61.70  5834.8   63.55  5842.7   62.44  5849.0   62.29
#Mann=10,-1,0
  3636.1    0.05       0  4995.7    0.05       0  5004.3    0.05       0
  5151.9   0.035       0  5446.0    0.05       0  5468.5   0.035       0
  5576.0    0.05       0  5635.5   0.035       0  5697.7    0.05       0
  5842.7   0.035       0
Bank Sta=4995.7,5004.3
Exp/Cntr=0.3,0.1

Chan Stop Cuts=-1