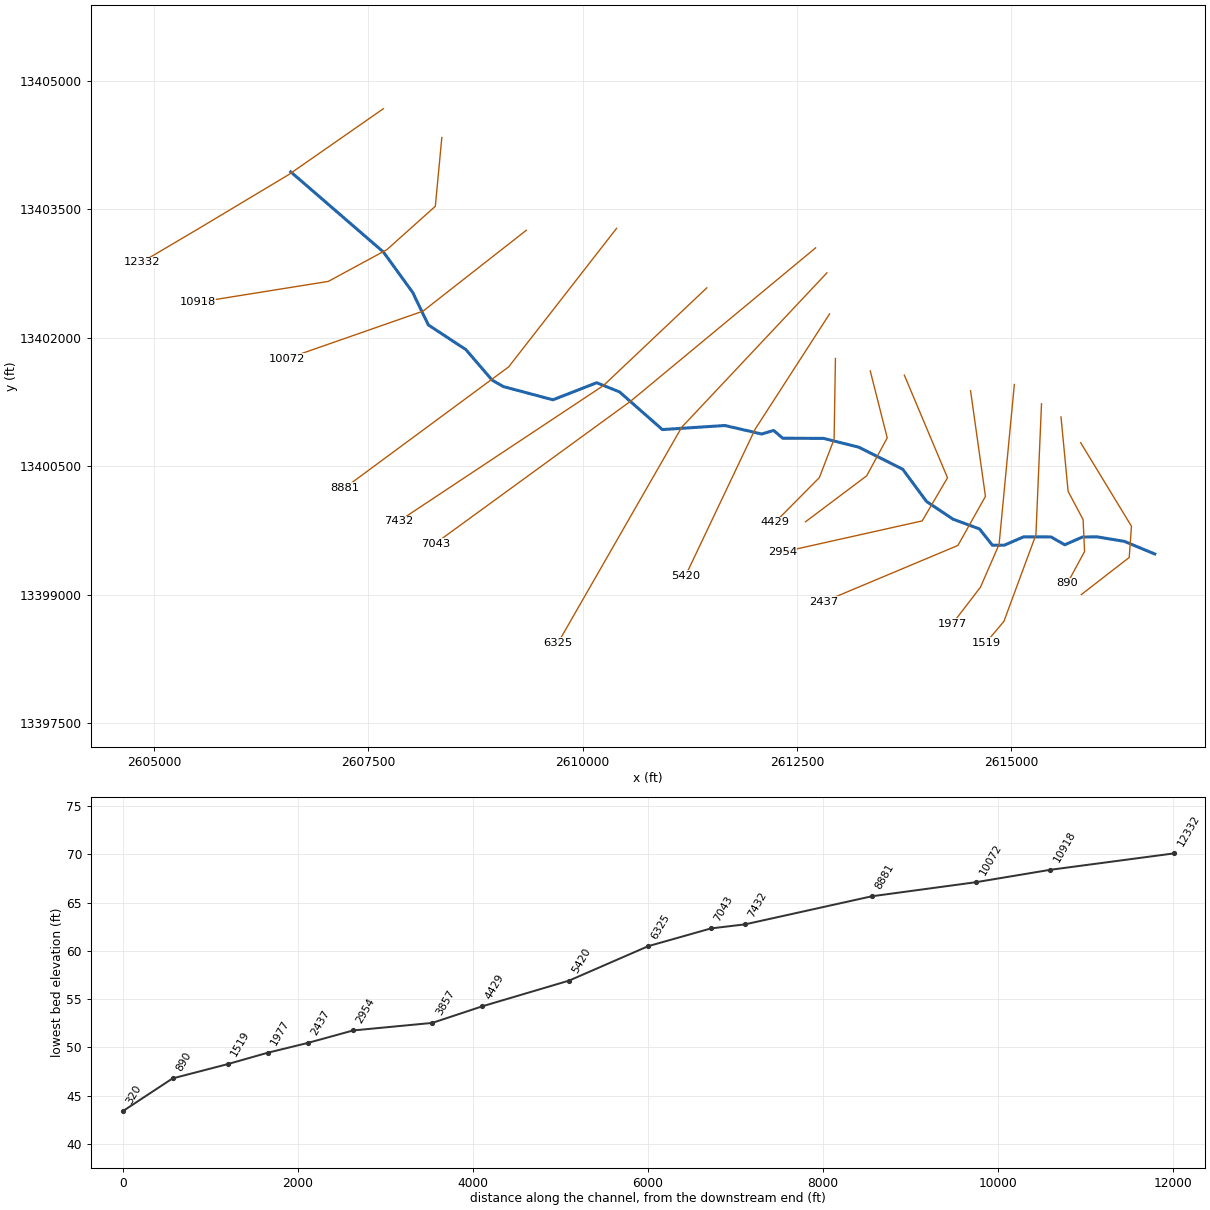
--- TRIB 1 TO DRY KUY CREEK.prj (project) ---

Proj Title=TRIB 1 TO DRY KUY CREEK Base Level Engineering
Current Plan=p01
Default Exp/Contr=0.3,0.1
English Units
Geom File=g01
Flow File=f01
Plan File=p01
Y Axis Title=Elevation
X Axis Title(PF)=Main Channel Distance
X Axis Title(XS)=Station
BEGIN DESCRIPTION:
TRIB 1 TO DRY KUY CREEK
END DESCRIPTION:
DSS Export Rating Curves= 0
DSS Export Rating Curve Sorted= 0
DSS Export Volume Flow Curves= 0
DXF OffsetX= 0
DXF OffsetY= 0
DXF ScaleX= 1
DXF ScaleY= 10

--- TRIB 1 TO DRY KUY CREEK.p01 (plan) ---

Plan Title=Multiple Run
Short Identifier=Multiple
Geom File=g01
Flow File=f01
Subcritical Flow
K Sum by GR= 0
Std Step Tol= 0.01
Critical Tol= 0.01
Num of Std Step Trials= 20
Max Error Tol= 0.3
Flow Tol Ratio= 0.001
Split Flow NTrial= 30
Split Flow Tol= 0.02
Split Flow Ratio= 0.02
Log Output Level= 0
Friction Slope Method= 1
Unsteady Friction Slope Method= 2
Unsteady Bridges Friction Slope Method= 1
Parabolic Critical Depth
Global Vel Dist=  1 , 1 , 1
Global Log Level= 0
CheckData=True
Encroach Param= -1, 0, 0, 0
BEGIN DESCRIPTION:
Multiple Run
END DESCRIPTION:

--- TRIB 1 TO DRY KUY CREEK.f01 (steady flow) ---

Flow Title=Multiple
Number of Profiles=7
Profile Names=10-year,25-year,50-year,1pct_min,100-year,1pct_plu,500-year
River Rch & RM= TRIB 1 TO DRY KU,Reach-1,12332
     273     393     488     293     584    1166     827
River Rch & RM= TRIB 1 TO DRY KU,Reach-1,10072
     421     624     790     483     963    1922    1416
River Rch & RM= TRIB 1 TO DRY KU,Reach-1,7432
     617     940    1213     755    1507    3007    2299
River Rch & RM= TRIB 1 TO DRY KU,Reach-1,4429
     959    1500    1972    1249    2491    4971    3933
River Rch & RM= TRIB 1 TO DRY KU,Reach-1,1977
     982    1546    2040    1298    2590    5168    4130
Boundary for River Rch & Prof#=TRIB 1 TO DRY KU,Reach-1,1
Up Type=0
Dn Type=3
Dn Slope=0.005
Boundary for River Rch & Prof#=TRIB 1 TO DRY KU,Reach-1,2
Up Type=0
Dn Type=3
Dn Slope=0.005
Boundary for River Rch & Prof#=TRIB 1 TO DRY KU,Reach-1,3
Up Type=0
Dn Type=3
Dn Slope=0.005
Boundary for River Rch & Prof#=TRIB 1 TO DRY KU,Reach-1,4
Up Type=0
Dn Type=3
Dn Slope=0.005
Boundary for River Rch & Prof#=TRIB 1 TO DRY KU,Reach-1,5
Up Type=0
Dn Type=3
Dn Slope=0.005
Boundary for River Rch & Prof#=TRIB 1 TO DRY KU,Reach-1,6
Up Type=0
Dn Type=3
Dn Slope=0.005
Boundary for River Rch & Prof#=TRIB 1 TO DRY KU,Reach-1,7
Up Type=0
Dn Type=3
Dn Slope=0.005

--- TRIB 1 TO DRY KUY CREEK.g01 (geometry) ---

Geom Title=Existing Conditions
Program Version=4.10

River Reach=TRIB 1 TO DRY KU,Reach-1
Reach XY= 30
      2606596.24     13403935.35      2607677.09     13402999.55
      2608018.92      13402527.2      2608201.29     13402148.18
      2608638.21     13401861.37      2608944.77     13401504.58
      2609076.56     13401428.76      2609654.82     13401274.72
      2610164.45      13401473.9      2610431.06     13401366.86
      2610930.93     13400927.24      2611659.85     13400974.64
      2612090.28     13400875.39      2612228.41     13400917.19
      2612335.43     13400826.06      2612809.78     13400824.48
      2613219.07     13400722.75      2613734.68     13400464.22
      2614011.76     13400088.61       2614322.7     13399880.83
      2614631.19     13399767.15      2614780.68     13399576.97
      2614919.06     13399577.25      2615145.03     13399674.93
       2615464.5      13399673.8      2615624.99     13399582.53
      2615830.94     13399672.74      2616000.08      13399675.2
      2616319.07     13399622.76        2616675.       13399475.

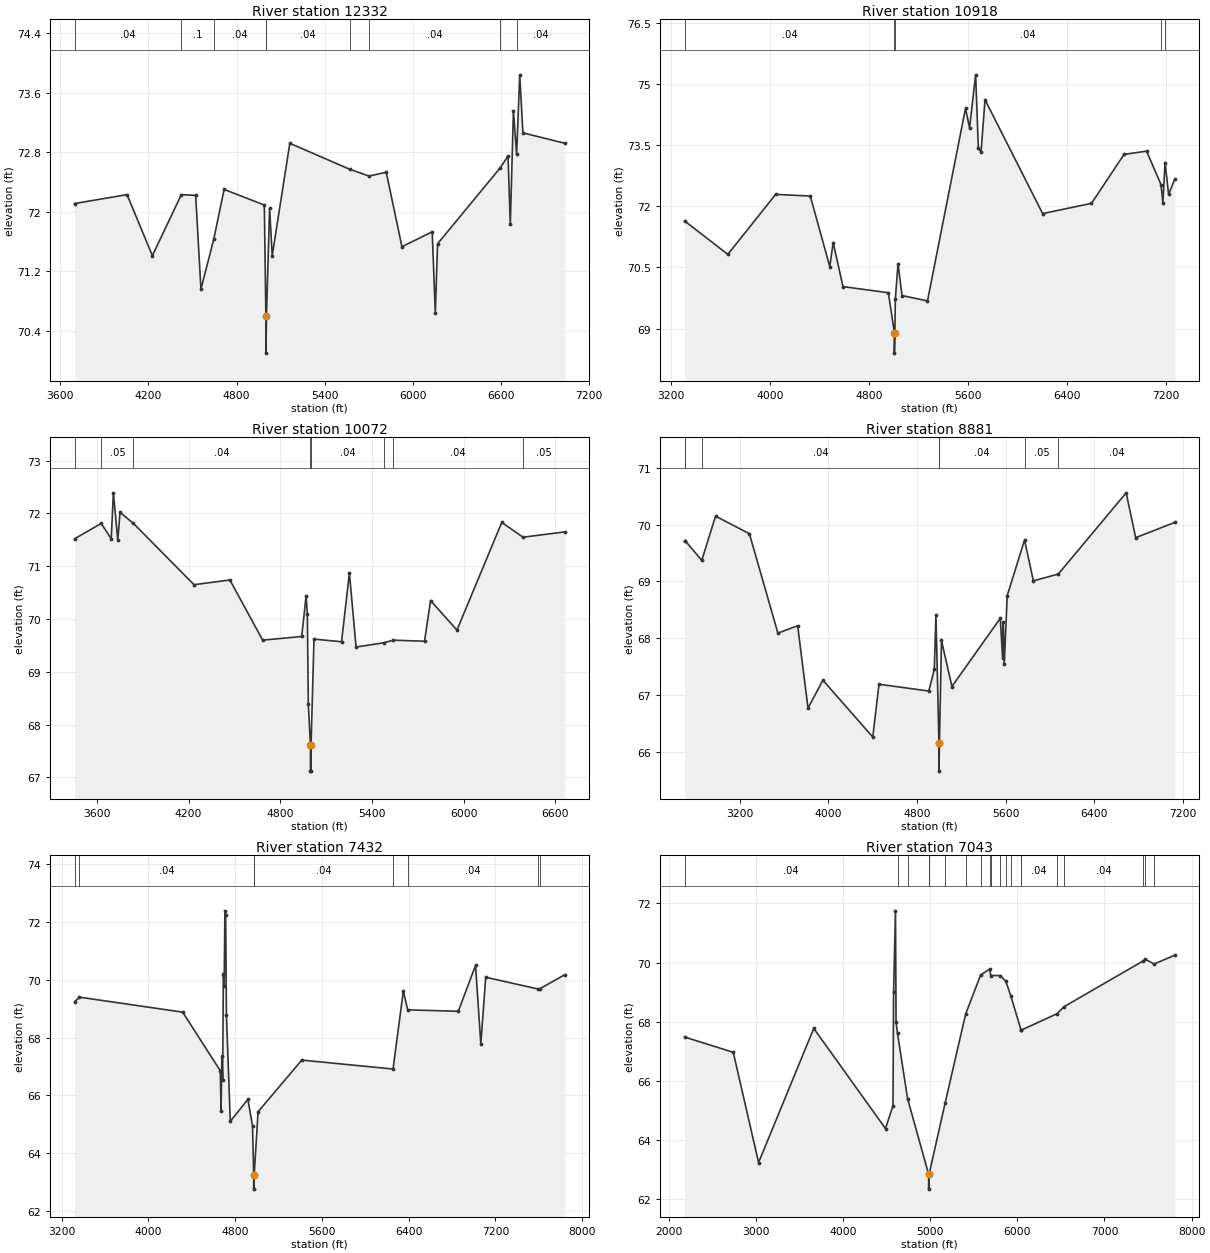
Type RM Length L Ch R = 1 ,12332   ,1414,1414,1414
BEGIN DESCRIPTION:
TRIB 1 TO DRY KUY CREEK 21.0
END DESCRIPTION:
XS GIS Cut Line= 4
      2607676.09     13404672.47      2606571.19     13403902.46
      2605518.54     13403271.43      2604858.58     13402881.69
#Sta/Elev= 30
  3696.5   72.11    4054   72.23  4226.8   71.41    4424   72.23  4521.7   72.22
  4557.5   70.96  4644.8   71.63  4715.4    72.3  4989.4   72.09    5000    70.6
  5000.3    70.1    5004    70.6  5025.2   72.05  5043.2   71.41    5163   72.92
  5572.1   72.57  5702.4   72.48    5820   72.53    5927   71.53  6133.1   71.73
  6154.4   70.64  6169.7   71.57  6596.5   72.59  6649.6   72.75  6665.2   71.83
  6686.6   73.36  6708.2   72.77  6729.5   73.84    6751   73.06    7037   72.92
#Mann= 9 ,-1 , 0
  3696.5     .04       0    4424      .1       0  4644.8     .04       0
    5000     .04       0    5004     .04       0  5572.1    .035       0
  5702.4     .04       0  6596.5    .035       0  6708.2     .04       0
Bank Sta=5000,5004
XS Rating Curve= 0 ,0
Exp/Cntr=0.3,0.1

Type RM Length L Ch R = 1 ,10918   ,846,846,846
BEGIN DESCRIPTION:
Mapping XS d97ab103
END DESCRIPTION:
XS GIS Cut Line= 5
       2608358.4     13404336.55      2608282.44     13403533.55
      2607716.45     13403026.64      2607034.16     13402656.85
       2605509.1     13402412.21
#Sta/Elev= 30
  3306.8   71.64  3656.6   70.82  4043.4   72.29  4323.2   72.25  4481.1   70.52
  4508.4   71.11  4587.9   70.03  4954.7   69.88  5003.4    68.9  5003.6    68.4
  5007.4    68.9    5011   69.72  5032.9   70.59  5065.3   69.81  5271.1   69.68
  5578.7    74.4  5611.1   73.92  5660.5   75.22  5682.4   73.43  5704.2   73.33
  5736.3   74.61  6202.2   71.82  6597.2   72.07  6860.5   73.27  7042.8   73.35
  7159.4   72.53  7174.5   72.09  7192.2   73.07  7221.2   72.29  7271.6   72.67
#Mann= 5 ,-1 , 0
  3306.8     .04       0  5003.4     .04       0  5007.4     .04       0
  7159.4    .035       0  7192.2     .04       0
Bank Sta=5003.4,5007.4
XS Rating Curve= 0 ,0
Exp/Cntr=0.3,0.1

Type RM Length L Ch R = 1 ,10072   ,1191,1191,1191
BEGIN DESCRIPTION:
Mapping XS 80ac0b10
END DESCRIPTION:
XS GIS Cut Line= 3
      2609343.81     13403253.72      2608139.41     13402309.73
      2606555.24     13401756.36
#Sta/Elev= 30
    3454   71.52  3628.4   71.81  3693.9   71.52  3708.1   72.39    3737   71.49
  3751.4   72.02  3839.6   71.81    4236   70.65  4470.2   70.74  4684.9    69.6
  4940.3   69.67  4969.2   70.44  4977.2   70.09  4983.7   68.39  4997.5   67.62
  4997.8   67.12  5001.3   67.12  5001.5   67.62  5020.7   69.62  5200.9   69.57
  5252.4   70.87  5296.1   69.47  5476.5   69.55  5540.3    69.6  5743.9   69.58
  5783.4   70.35    5956   69.79  6249.4   71.83  6388.1   71.55  6662.3   71.65
#Mann= 8 ,-1 , 0
    3454     .04       0  3628.4     .05       0  3839.6     .04       0
  4997.5     .04       0  5001.5     .04       0  5476.5      .1       0
  5540.3     .04       0  6388.1     .05       0
Bank Sta=4997.5,5001.5
XS Rating Curve= 0 ,0
Exp/Cntr=0.3,0.1

Type RM Length L Ch R = 1 ,8881    ,1449,1449,1449
BEGIN DESCRIPTION:
Mapping XS e0d712f8
END DESCRIPTION:
XS GIS Cut Line= 3
      2610396.37     13403275.46      2609137.68     13401658.69
      2607227.92     13400248.07
#Sta/Elev= 30
  2702.9   69.71  2707.2   69.72  2858.1   69.37  2982.3   70.15  3287.9   69.84
  3544.9   68.09  3723.1   68.22  3816.3   66.77  3951.1   67.26  4400.8   66.26
  4456.9   67.19  4905.9   67.07    4956   67.45  4970.6   68.41  4997.7   66.16
    4998   65.66  5002.1   66.16  5020.7   67.96  5114.7   67.15  5550.8   68.35
  5571.9   67.66  5578.2   68.29  5586.6   67.54  5613.6   68.75    5770   69.73
  5849.6   69.01  6074.5   69.13  6686.8   70.56  6772.4   69.77  7126.1   70.04
#Mann= 7 ,-1 , 0
  2702.9     .04       0  2707.2     .05       0  2858.1     .04       0
  4997.7     .04       0  5002.1     .04       0    5770     .05       0
  6074.5     .04       0
Bank Sta=4997.7,5002.1
XS Rating Curve= 0 ,0
Exp/Cntr=0.3,0.1

Type RM Length L Ch R = 1 ,7432    ,389,389,389
BEGIN DESCRIPTION:
Mapping XS 3572ca49
END DESCRIPTION:
XS GIS Cut Line= 3
      2611448.84     13402580.97      2610244.45     13401441.68
      2607858.69      13399858.4
#Sta/Elev= 30
  3319.7   69.24  3364.4    69.4  4316.8   68.88  4663.5   66.85  4670.8   65.46
  4677.6   67.36  4684.9   66.53  4691.8   70.21  4699.1    69.8    4706   72.39
  4713.2   72.23  4720.1   68.78  4755.7    65.1  4918.3   65.86  4960.8   64.93
  4971.4   63.25  4971.7   62.75  4976.2   63.25  5011.8   65.43  5414.8   67.22
  6256.6   66.91  6351.1   69.61  6391.8   68.96  6858.3   68.91  7017.2    70.5
  7065.8   67.78  7110.9   70.09  7596.1   69.68  7609.8   69.69  7840.9   70.18
#Mann= 8 ,-1 , 0
  3319.7     .05       0  3364.4     .04       0  4971.4     .04       0
  4976.2     .04       0  6256.6     .05       0  6391.8     .04       0
  7596.1     .05       0  7609.8     .04       0
Bank Sta=4971.4,4976.2
XS Rating Curve= 0 ,0
Exp/Cntr=0.3,0.1

Type RM Length L Ch R = 1 ,7043    ,718,718,718
BEGIN DESCRIPTION:
Mapping XS 12bac251
END DESCRIPTION:
XS GIS Cut Line= 3
      2612718.36     13403048.02      2610559.12     13401257.22
      2608280.48     13399597.07
#Sta/Elev= 30
  2183.1   67.48  2741.8   66.96  3032.2   63.23  3665.1   67.77  4488.1   64.38
  4574.1   65.16  4580.6   68.99  4602.7   71.75  4609.2   67.99    4626    67.6
  4741.5   65.39  4983.2   62.83  4983.5   62.33    4988   62.83  5173.1   65.26
  5407.8   68.26  5579.5   69.58  5684.4   69.78  5695.1   69.56  5805.6   69.56
  5869.3   69.36  5924.8   68.88  6043.4   67.71  6043.9   67.71  6458.3   68.27
  6533.2    68.5  7447.6   70.06  7467.9   70.11  7570.2   69.95  7807.6   70.25
#Mann= 20 ,-1 , 0
  2183.1     .04       0    4626     .05       0  4741.5     .04       0
  4983.2     .04       0    4988     .04       0  5173.1    .035       0
  5407.8     .04       0  5579.5    .035       0  5684.4     .04       0
  5695.1    .035       0  5805.6     .04       0  5869.3    .035       0
  5924.8     .04       0  6043.4    .035       0  6043.9     .04       0
  6458.3     .05       0  6533.2     .04       0  7447.6     .05       0
  7467.9     .04       0  7570.2    .035       0
Bank Sta=4983.2,4988
XS Rating Curve= 0 ,0
Exp/Cntr=0.3,0.1

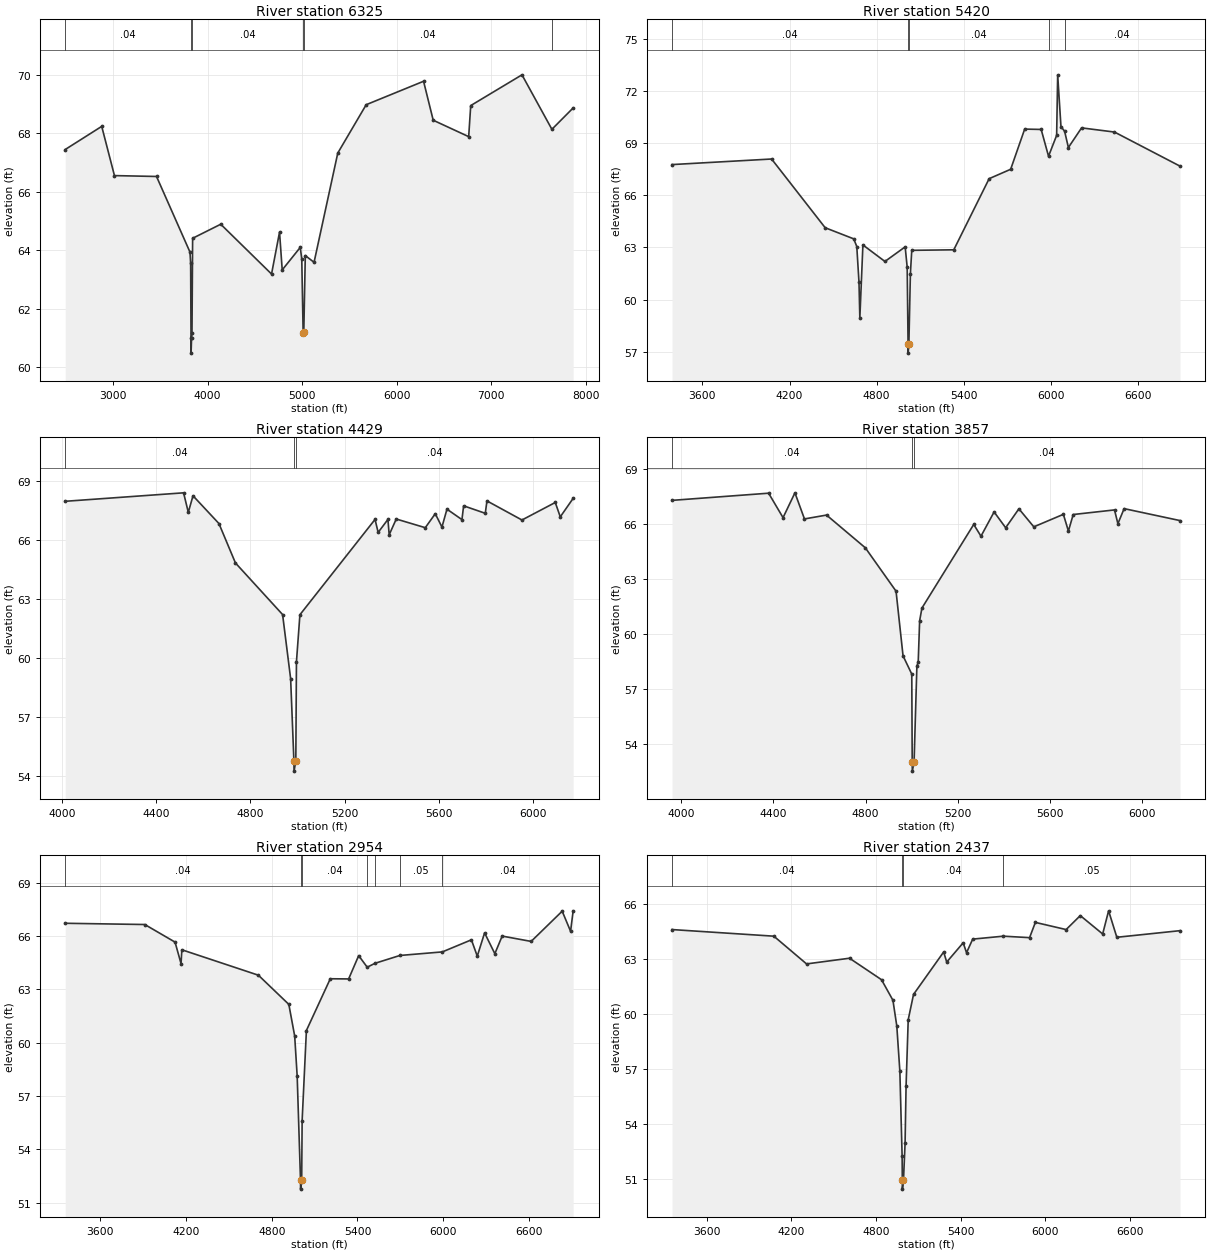
Type RM Length L Ch R = 1 ,6325    ,905,905,905
BEGIN DESCRIPTION:
Mapping XS d23b2095
END DESCRIPTION:
XS GIS Cut Line= 3
      2612850.29     13402756.33      2611155.91      13400953.4
      2609712.79     13398436.08
#Sta/Elev= 30
  2493.1   67.44  2879.6   68.23  3014.4   66.55  3459.8   66.52  3813.5   63.94
  3820.8   63.56  3824.9   60.99  3825.4   60.49  3830.3   60.99  3834.9   61.17
  3841.8   64.41  4139.2   64.89  4676.9   63.19  4761.5   64.62  4789.8   63.33
  4980.9    64.1  4996.7    63.7  5011.5   61.17  5018.3   61.22  5034.1   63.82
  5126.8   63.59  5377.9   67.32  5678.6   68.97  6285.7   69.77  6387.8   68.44
  6763.2   67.88  6784.8   68.94  7327.1   69.99  7643.9   68.13  7868.9   68.86
#Mann= 6 ,-1 , 0
  2493.1     .04       0  3824.9     .04       0  3830.3     .04       0
  5011.5     .04       0  5018.3     .04       0  7643.9     .05       0
Bank Sta=5011.5,5018.3
XS Rating Curve= 0 ,0
Exp/Cntr=0.3,0.1

Type RM Length L Ch R = 1 ,5420    ,991,991,991
BEGIN DESCRIPTION:
Mapping XS 021d6fca
END DESCRIPTION:
XS GIS Cut Line= 3
      2612881.18     13402277.19      2612013.11      13400931.7
       2611199.3     13399217.26
#Sta/Elev= 30
  3390.8   67.76  4076.6   68.08  4445.5   64.13  4642.2   63.49  4663.3   63.05
  4678.5      61  4684.4   58.94  4705.5   63.14  4857.2   62.19  4996.6   63.03
  5010.5   61.86  5016.6   57.42    5017   56.92  5022.1   57.42  5032.6   61.49
    5042   62.83  5331.5   62.86    5575   66.95  5723.3   67.49  5819.8    69.8
  5933.4   69.78  5984.1   68.24    6040   69.44  6047.1   72.92  6069.8   69.94
  6094.8   69.68  6120.8   68.74  6211.7   69.87  6438.5   69.63  6889.8   67.67
#Mann= 5 ,-1 , 0
  3390.8     .04       0  5016.6     .04       0  5022.1     .04       0
  5984.1     .05       0  6094.8     .04       0
Bank Sta=5016.6,5022.1
XS Rating Curve= 0 ,0
Exp/Cntr=0.3,0.1

Type RM Length L Ch R = 1 ,4429    ,572,572,572
BEGIN DESCRIPTION:
Mapping XS fcae9985
END DESCRIPTION:
XS GIS Cut Line= 4
      2612949.86     13401757.35      2612934.23     13400814.59
      2612762.36     13400366.68      2612246.76     13399845.87
#Sta/Elev= 30
  4014.3   67.96  4516.7   68.39  4536.7    67.4  4556.7   68.24  4666.7   66.83
  4736.7   64.83  4936.8   62.21  4970.9   58.96  4984.9   54.76  4985.4   54.26
  4992.9   54.76  4995.6   59.81  5010.3    62.2  5329.1   67.04  5342.3   66.38
  5383.8   67.04  5389.1   66.26  5419.1   67.06  5542.3   66.62  5584.7   67.33
    5613   66.65  5634.3   67.56  5697.9   67.03    5705   67.73  5796.9   67.35
    5804   67.98  5952.5   67.01  6093.9    67.9  6115.1   67.17  6169.8   68.11
#Mann= 3 ,-1 , 0
  4014.3     .04       0  4984.9     .04       0  4992.9     .04       0
Bank Sta=4984.9,4992.9
XS Rating Curve= 0 ,0
Exp/Cntr=0.3,0.1

Type RM Length L Ch R = 1 ,3857    ,903,903,903
BEGIN DESCRIPTION:
Mapping XS ae1a766a
END DESCRIPTION:
XS GIS Cut Line= 4
      2613356.12     13401611.42      2613554.02     13400830.22
      2613314.44     13400387.51      2612600.88     13399851.03
#Sta/Elev= 30
  3960.9   67.27  4379.5   67.66  4442.1   66.33  4493.6   67.68  4534.9   66.26
  4630.6   66.47  4798.7   64.69  4931.9   62.33  4962.3   58.81  5000.1   57.82
    5002   53.04  5002.5   52.54  5010.1   53.04  5022.3   58.26    5028   58.47
  5034.2   60.72  5044.1   61.41  5268.7   65.96    5300   65.32    5357   66.64
  5407.1   65.78  5464.5   66.81  5529.1   65.83  5657.3   66.51  5679.1    65.6
  5699.9    66.5    5879   66.75  5893.6      66  5920.6   66.82  6162.9   66.17
#Mann= 3 ,-1 , 0
  3960.9     .04       0    5002     .04       0  5010.1     .04       0
Bank Sta=5002,5010.1
XS Rating Curve= 0 ,0
Exp/Cntr=0.3,0.1

Type RM Length L Ch R = 1 ,2954    ,517,517,517
BEGIN DESCRIPTION:
Mapping XS 14381053
END DESCRIPTION:
XS GIS Cut Line= 4
      2613753.63     13401562.56       2614257.1     13400364.64
      2613961.96     13399861.16      2612330.02     13399496.58
#Sta/Elev= 30
  3354.2   66.71  3911.4   66.64  4123.1   65.65  4165.1   64.44  4170.6   65.22
  4706.3   63.79  4919.4   62.15  4960.4   60.37  4977.8   58.12  5001.2   52.26
  5001.7   51.76  5009.4   52.26  5012.5   55.61  5042.4   60.68  5209.6   63.59
    5338   63.58  5408.3   64.89    5468   64.24  5522.8   64.46  5697.1    64.9
  5993.7    65.1  6197.3   65.78  6238.3   64.86  6289.5   66.17  6361.2      65
  6412.5   65.99  6615.4   65.69  6832.6   67.39  6891.3   66.26  6909.4   67.41
#Mann= 7 ,-1 , 0
  3354.2     .04       0  5001.2     .04       0  5009.4     .04       0
    5468     .05       0  5522.8     .04       0  5697.1     .05       0
  5993.7     .04       0
Bank Sta=5001.2,5009.4
XS Rating Curve= 0 ,0
Exp/Cntr=0.3,0.1

Type RM Length L Ch R = 1 ,2437    ,460,460,460
BEGIN DESCRIPTION:
Mapping XS 4c46add9
END DESCRIPTION:
XS GIS Cut Line= 4
      2614526.21     13401380.21      2614699.81     13400147.62
      2614378.63     13399574.71      2612808.76     13398915.54
#Sta/Elev= 30
  3353.1    64.6  4075.4   64.24  4307.5   62.73  4612.3   63.04  4839.4   61.87
  4920.4   60.75  4947.8   59.35  4969.5   56.89  4985.5   52.27    4987   50.97
  4987.5   50.47  4995.3   50.97  5006.5   52.96  5013.6   56.08  5028.8   59.69
  5066.5   61.07  5280.3   63.38    5302   62.83  5418.8   63.88  5442.6   63.34
  5486.4   64.08  5703.6   64.24  5889.9   64.16    5931   64.99  6149.2    64.6
  6249.7   65.36  6408.5   64.36  6450.6   65.62    6509   64.18  6957.3   64.54
#Mann= 4 ,-1 , 0
  3353.1     .04       0    4987     .04       0  4995.3     .04       0
  5703.6     .05       0
Bank Sta=4987,4995.3
XS Rating Curve= 0 ,0
Exp/Cntr=0.3,0.1

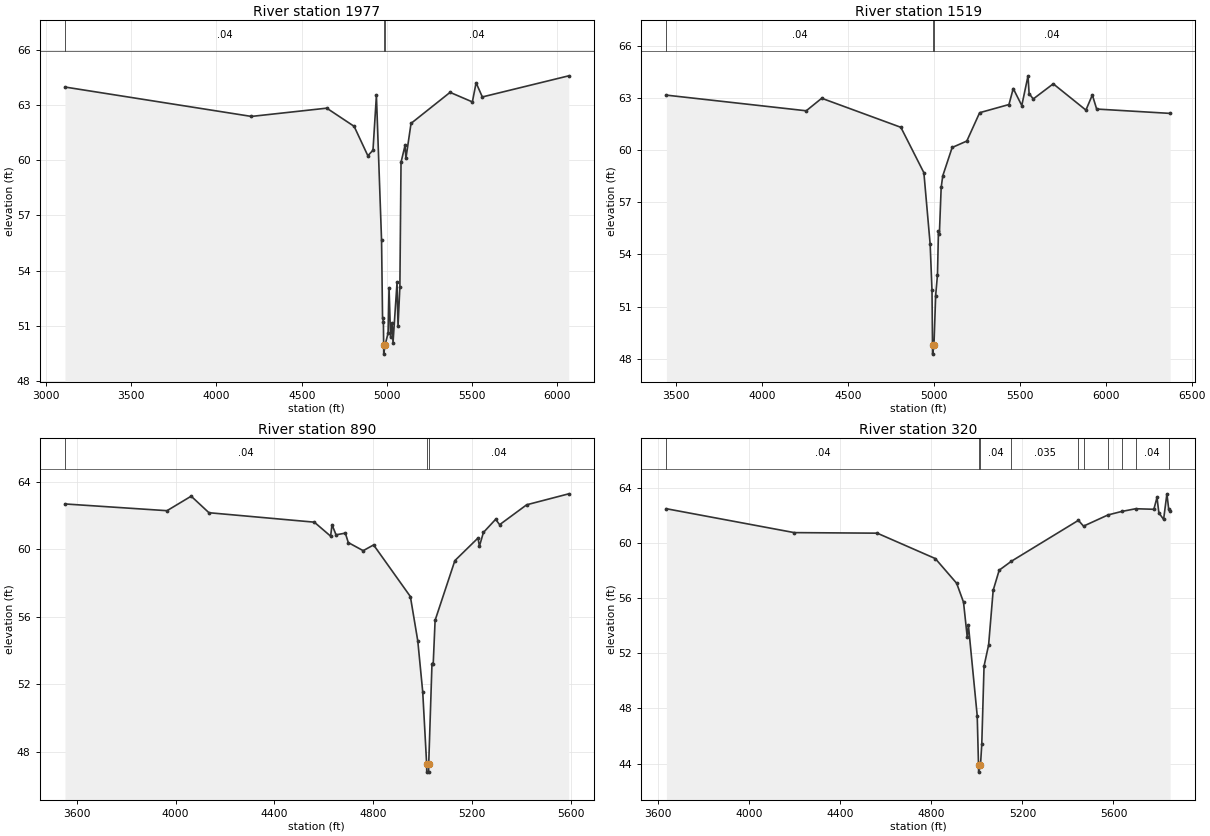
Type RM Length L Ch R = 1 ,1977    ,458,458,458
BEGIN DESCRIPTION:
Mapping XS f0fc1b14
END DESCRIPTION:
XS GIS Cut Line= 4
      2615036.88     13401453.48      2614858.93     13399587.12
      2614641.91     13399087.99      2614316.39     13398662.65
#Sta/Elev= 30
  3111.5   63.99  4204.9   62.39  4646.9   62.84  4807.6   61.85    4888   60.25
  4918.1   60.55  4938.2   63.53  4968.4   55.64  4974.2   51.43  4979.2   51.22
  4980.7   49.95  4981.2   49.45  4989.1   49.95  5006.8    50.6  5012.3   53.07
  5021.3   50.39  5030.3   51.14  5035.7   50.08  5059.2   53.35    5065   50.97
  5075.9   53.13  5082.6   59.89  5106.1   60.81  5111.5   60.12  5141.3   62.01
  5370.3    63.7  5501.1   63.18  5522.9   64.22  5559.5   63.45  6066.2    64.6
#Mann= 3 ,-1 , 0
  3111.5     .04       0  4980.7     .04       0  4989.1     .04       0
Bank Sta=4980.7,4989.1
XS Rating Curve= 0 ,0
Exp/Cntr=0.3,0.1

Type RM Length L Ch R = 1 ,1519    ,629,629,629
BEGIN DESCRIPTION:
Mapping XS 4fcbb2a4
END DESCRIPTION:
XS GIS Cut Line= 4
      2615353.72     13401227.79      2615288.61     13399699.97
      2614915.35     13398688.69      2614707.02      13398441.3
#Sta/Elev= 30
  3444.2   63.16  4257.7   62.26  4347.8   62.98  4808.2   61.31  4942.1    58.7
  4978.7   54.58  4989.4   51.93  4992.3   48.77  4992.8   48.27  5000.7   48.77
  5010.7   51.64  5021.3   52.84  5026.9   55.35  5032.2   55.15  5042.7   57.85
    5052   58.52  5106.6   60.15  5191.9   60.52  5266.5   62.15  5437.1   62.62
    5462   63.54  5511.7   62.56    5548   64.27  5554.3   63.25  5578.4   62.94
  5694.8   63.81  5884.8    62.3  5922.2   63.17  5947.3   62.36  6374.8   62.11
#Mann= 3 ,-1 , 0
  3444.2     .04       0  4992.3     .04       0  5000.7     .04       0
Bank Sta=4992.3,5000.7
XS Rating Curve= 0 ,0
Exp/Cntr=0.3,0.1

Type RM Length L Ch R = 1 ,890     ,570,570,570
BEGIN DESCRIPTION:
Mapping XS a1b16b59
END DESCRIPTION:
XS GIS Cut Line= 5
      2615581.15     13401074.99      2615664.15     13400205.34
      2615838.75     13399877.09      2615856.11     13399503.83
      2615656.47     13399134.94
#Sta/Elev= 30
  3552.4   62.69  3965.3   62.29  4063.1   63.15    4135   62.17  4561.4   61.61
  4627.4   60.78    4633   61.46  4649.3   60.86  4686.9   60.96  4698.9    60.4
  4759.2   59.92  4801.3   60.26  4950.1    57.2  4980.1   54.57  5000.1   51.55
  5015.9   47.29  5016.4   46.79  5023.9   46.79  5024.4   47.29  5037.6   53.23
  5042.6   53.22  5050.2   55.79  5130.2   59.33  5223.8   60.67  5229.5   60.18
  5245.7      61  5295.2   61.78  5311.3   61.46  5420.7   62.64  5590.9   63.29
#Mann= 3 ,-1 , 0
  3552.4     .04       0  5015.9     .04       0  5024.4     .04       0
Bank Sta=5015.9,5024.4
XS Rating Curve= 0 ,0
Exp/Cntr=0.3,0.1

Type RM Length L Ch R = 1 ,320     ,0,0,0
BEGIN DESCRIPTION:
Mapping XS 55e6636f
END DESCRIPTION:
XS GIS Cut Line= 4
      2615810.64     13400773.96      2616402.98     13399798.97
      2616376.94     13399434.39      2615818.52      13399001.5
#Sta/Elev= 30
  3636.1   62.47  4197.9   60.74  4562.2    60.7  4817.4   58.86  4911.2   57.07
  4941.3    55.7  4957.7   53.17  4962.8   54.03  5001.5   47.47  5007.2   43.89
  5007.7   43.39  5015.8   43.89  5021.5    45.4  5031.5   51.07  5051.6   52.61
  5071.6   56.56  5098.1   58.02  5151.9   58.67    5446   61.63  5468.5   61.21
    5576   62.02  5635.5   62.27  5697.7   62.47  5777.5   62.43  5791.3   63.29
  5799.5   62.17  5820.3    61.7  5834.8   63.55  5842.7   62.44    5849   62.29
#Mann= 10 ,-1 , 0
  3636.1     .04       0  5007.2     .04       0  5015.8     .04       0
  5151.9    .035       0    5446     .04       0  5468.5    .035       0
    5576     .04       0  5635.5    .035       0  5697.7     .04       0
  5842.7    .035       0
Bank Sta=5007.2,5015.8
XS Rating Curve= 0 ,0
Exp/Cntr=0.3,0.1

Chan Stop Cuts=-1
Use User Specified Reach Order=0
Composite Channel Slope=5