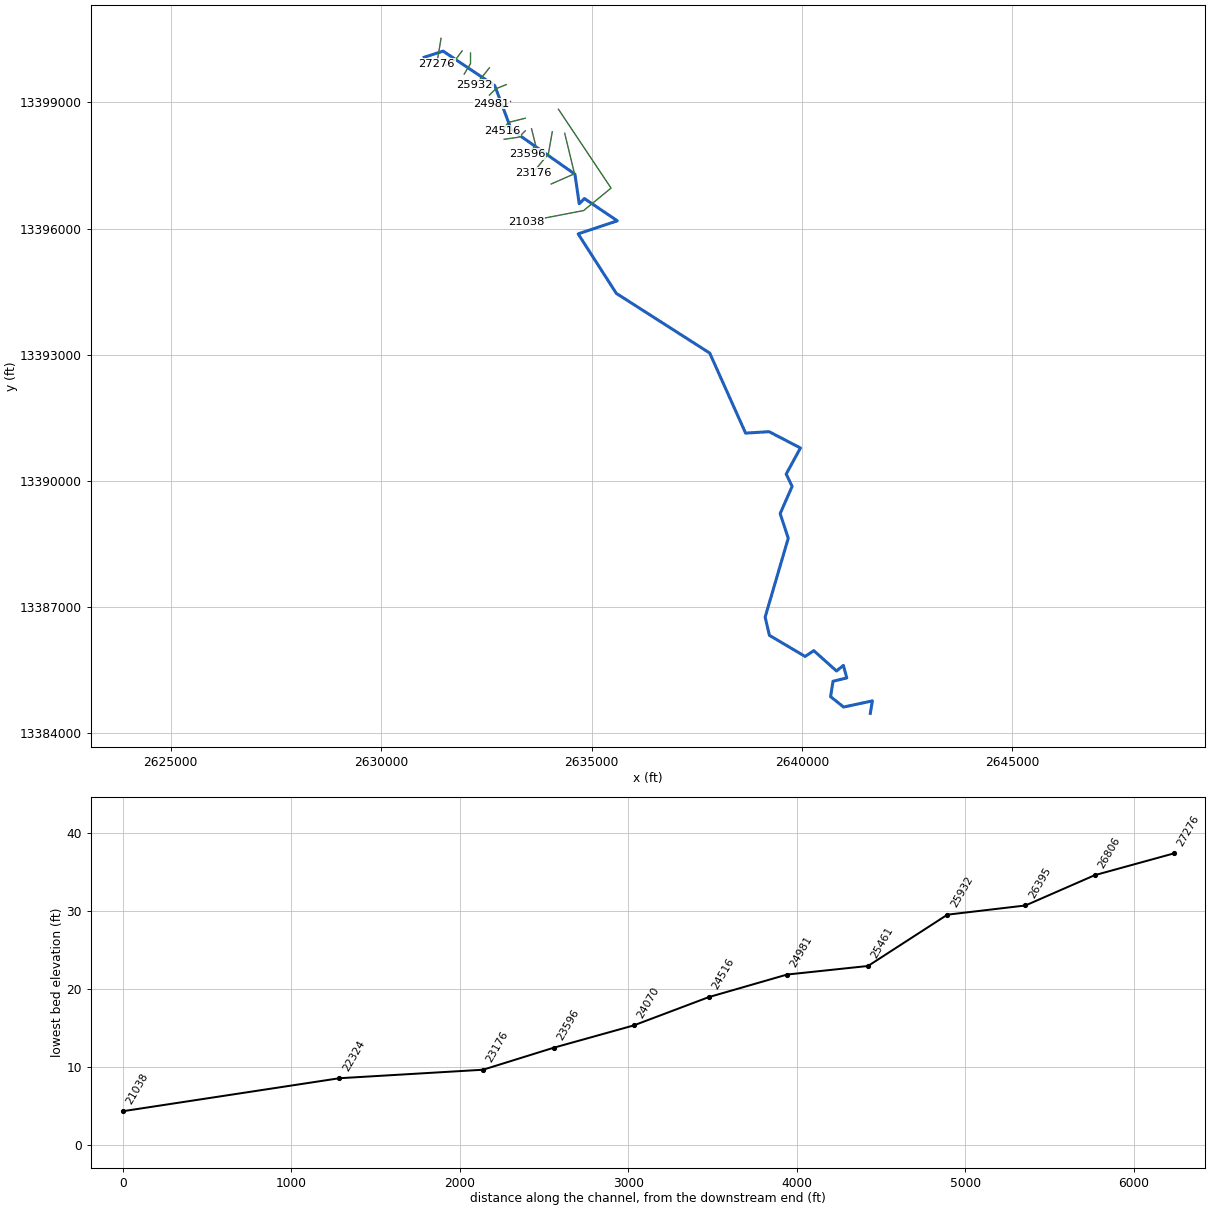
--- TRIB 1 TO GUADALUPE RIVER.prj (project) ---

Proj Title=TRIB 1 TO GUADALUPE RIVER Base Level Engineering
Current Plan=p01
Default Exp/Contr=0.3,0.1
English Units
Geom File=g01
Flow File=f01
Plan File=p01
Y Axis Title=Elevation
X Axis Title(PF)=Main Channel Distance
X Axis Title(XS)=Station
BEGIN DESCRIPTION:
TRIB 1 TO GUADALUPE RIVER
END DESCRIPTION:
DSS Export Rating Curves= 0
DSS Export Rating Curve Sorted= 0
DSS Export Volume Flow Curves= 0
DXF OffsetX= 0
DXF OffsetY= 0
DXF ScaleX= 1
DXF ScaleY= 10

--- TRIB 1 TO GUADALUPE RIVER.p01 (plan) ---

Plan Title=Multiple Run
Short Identifier=Multiple
Geom File=g01
Flow File=f01
Subcritical Flow
K Sum by GR= 0
Std Step Tol= 0.01
Critical Tol= 0.01
Num of Std Step Trials= 20
Max Error Tol= 0.3
Flow Tol Ratio= 0.001
Split Flow NTrial= 30
Split Flow Tol= 0.02
Split Flow Ratio= 0.02
Log Output Level= 0
Friction Slope Method= 1
Unsteady Friction Slope Method= 2
Unsteady Bridges Friction Slope Method= 1
Parabolic Critical Depth
Global Vel Dist=  1 , 1 , 1
Global Log Level= 0
CheckData=True
Encroach Param= -1, 0, 0, 0
BEGIN DESCRIPTION:
Multiple Run
END DESCRIPTION:

--- TRIB 1 TO GUADALUPE RIVER.f01 (steady flow) ---

Flow Title=Multiple
Number of Profiles=7
Profile Names=10-year,25-year,50-year,1pct_min,100-year,1pct_plu,500-year
River Rch & RM= TRIB 1 TO GUADAL,Reach-1,27276
     733    1148    1512     963    1921    3834    3066
River Rch & RM= TRIB 1 TO GUADAL,Reach-1,23176
     756    1186    1563     996    1987    3964    3171
Boundary for River Rch & Prof#=TRIB 1 TO GUADAL,Reach-1,1
Up Type=0
Dn Type=3
Dn Slope=0.005
Boundary for River Rch & Prof#=TRIB 1 TO GUADAL,Reach-1,2
Up Type=0
Dn Type=3
Dn Slope=0.005
Boundary for River Rch & Prof#=TRIB 1 TO GUADAL,Reach-1,3
Up Type=0
Dn Type=3
Dn Slope=0.005
Boundary for River Rch & Prof#=TRIB 1 TO GUADAL,Reach-1,4
Up Type=0
Dn Type=3
Dn Slope=0.005
Boundary for River Rch & Prof#=TRIB 1 TO GUADAL,Reach-1,5
Up Type=0
Dn Type=3
Dn Slope=0.005
Boundary for River Rch & Prof#=TRIB 1 TO GUADAL,Reach-1,6
Up Type=0
Dn Type=3
Dn Slope=0.005
Boundary for River Rch & Prof#=TRIB 1 TO GUADAL,Reach-1,7
Up Type=0
Dn Type=3
Dn Slope=0.005

--- TRIB 1 TO GUADALUPE RIVER.g01 (geometry) ---

Geom Title=Existing Conditions
Program Version=4.10

River Reach=TRIB 1 TO GUADAL,Reach-1
Reach XY= 30
        2631025.       13400075.      2631473.42     13400221.17
      2632702.01     13399398.51      2633091.64     13398358.32
       2634605.7     13397295.03      2634708.39     13396591.14
      2634831.51     13396716.11      2635614.07     13396185.44
       2634682.5       13395875.      2635588.62     13394461.78
      2637808.57     13393041.76      2638661.33     13391138.22
      2639219.07     13391172.76      2639964.02     13390785.37
      2639625.53     13390164.32      2639766.98     13389871.66
      2639482.31     13389224.91      2639675.04     13388640.34
      2639125.72     13386764.29      2639226.98     13386330.67
      2640076.65     13385828.12      2640281.66     13385966.03
      2640821.68     13385482.58      2640984.74     13385615.07
      2641065.85     13385318.23      2640738.23     13385238.67
       2640680.8      13384872.7      2640990.16     13384625.36
      2641673.39     13384771.87        2641625.       13384475.

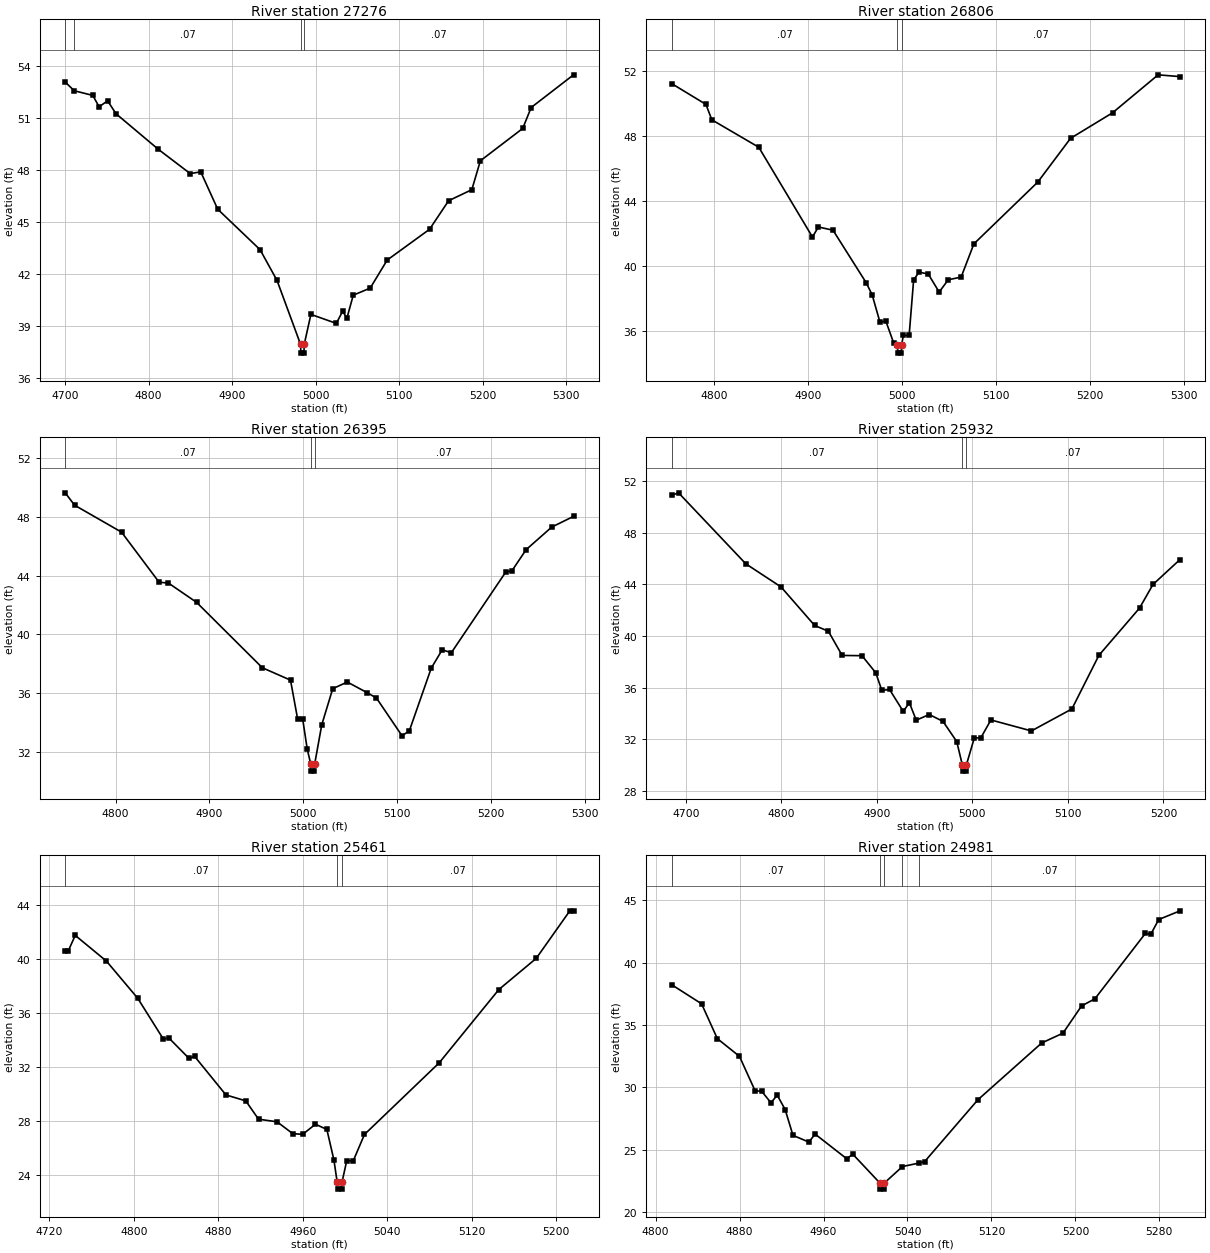
Type RM Length L Ch R = 1 ,27276   ,470,470,470
BEGIN DESCRIPTION:
TRIB 1 TO GUADALUPE RIVER 33.0
END DESCRIPTION:
XS GIS Cut Line= 3
        2631425.     13400525.02        2631375.       13400225.
        2631325.       13399925.
#Sta/Elev= 30
  4700.2   53.08    4711   52.58  4733.2   52.31  4740.8   51.65  4750.9      52
    4761   51.25  4811.7   49.19  4849.8   47.79  4862.4   47.89  4882.7   45.73
  4933.4   43.39  4953.7   41.61  4981.9   37.91  4982.2   37.41  4985.9   37.41
  4986.2   37.91  4994.2   39.65  5024.6   39.13  5032.2   39.83  5037.3   39.43
  5044.9   40.76  5065.2   41.17  5085.5   42.79  5136.2   44.57    5159   46.22
  5186.8   46.86    5197   48.53  5247.7    50.4  5257.8   51.61  5308.5    53.5
#Mann= 4 ,-1 , 0
  4700.2     .05       0    4711     .07       0  4981.9     .05       0
  4986.2     .07       0
Bank Sta=4981.9,4986.2
XS Rating Curve= 0 ,0
Exp/Cntr=0.3,0.1

Type RM Length L Ch R = 1 ,26806   ,411,411,411
BEGIN DESCRIPTION:
TRIB 1 TO GUADALUPE RIVER 32.0
END DESCRIPTION:
XS GIS Cut Line= 3
      2631925.03     13400225.03        2631775.       13400025.
      2631524.99     13399874.99
#Sta/Elev= 30
  4754.5   51.21    4791   49.93  4797.3   48.98  4847.3   47.29  4904.5   41.76
  4910.8   42.38  4926.4   42.18  4961.8   38.94  4968.1    38.2  4976.4   36.52
  4982.7   36.58    4991   35.24  4995.1   35.11  4995.4   34.61  4999.2   34.61
  4999.4   35.11  5001.4    35.7  5007.5    35.7  5012.3   39.12  5018.1    39.6
  5027.9   39.48  5039.5   38.37  5049.2   39.13  5062.9   39.29  5076.5   41.34
  5144.5   45.14  5179.5   47.84  5224.2   49.41  5272.8   51.75  5296.1   51.64
#Mann= 3 ,-1 , 0
  4754.5     .07       0  4995.1     .05       0  4999.4     .07       0
Bank Sta=4995.1,4999.4
XS Rating Curve= 0 ,0
Exp/Cntr=0.3,0.1

Type RM Length L Ch R = 1 ,26395   ,463,463,463
BEGIN DESCRIPTION:
TRIB 1 TO GUADALUPE RIVER 31.0
END DESCRIPTION:
XS GIS Cut Line= 3
        2632125.       13400175.        2632125.       13399925.
      2631975.02     13399675.04
#Sta/Elev= 30
  4746.4   49.62  4756.4   48.78  4806.4   46.95  4846.4   43.55  4856.4   43.49
  4886.4   42.18  4956.4   37.74  4986.4    36.9  4993.9   34.29  4999.3   34.29
  5004.2   32.22  5007.9   31.22  5008.1   30.72  5011.9   30.72  5012.2   31.22
  5019.7   33.87  5031.4   36.32  5046.9   36.77  5068.3   36.04    5078   35.68
  5105.2   33.12    5113   33.46  5136.3   37.71    5148   38.96  5157.7   38.76
    5216   44.27  5221.9   44.29  5237.4   45.76  5264.6   47.29  5287.9   48.02
#Mann= 3 ,-1 , 0
  4746.4     .07       0  5007.9     .05       0  5012.2     .07       0
Bank Sta=5007.9,5012.2
XS Rating Curve= 0 ,0
Exp/Cntr=0.3,0.1

Type RM Length L Ch R = 1 ,25932   ,471,471,471
BEGIN DESCRIPTION:
TRIB 1 TO GUADALUPE RIVER 30.0
END DESCRIPTION:
XS GIS Cut Line= 3
        2632575.       13399825.        2632375.       13399575.
      2632224.99     13399424.99
#Sta/Elev= 30
  4685.1   50.88  4692.3   51.07  4762.7   45.58  4799.6   43.79  4834.8   40.81
  4849.2   40.36  4863.6   38.49  4884.4   38.47  4898.8   37.15  4905.2   35.78
  4913.2   35.86  4927.6   34.16    4934   34.83  4941.2   33.48  4954.8   33.92
  4969.2   33.39  4983.6   31.83  4989.4   30.04  4989.7   29.54  4993.5   29.54
  4993.8   30.04    5002   32.11  5008.8   32.11  5019.4    33.5  5061.8   32.65
  5104.2   34.35  5132.5    38.5    5175   42.15  5189.1   43.98  5217.4   45.91
#Mann= 3 ,-1 , 0
  4685.1     .07       0  4989.4     .05       0  4993.8     .07       0
Bank Sta=4989.4,4993.8
XS Rating Curve= 0 ,0
Exp/Cntr=0.3,0.1

Type RM Length L Ch R = 1 ,25461   ,480,480,480
BEGIN DESCRIPTION:
TRIB 1 TO GUADALUPE RIVER 29.0
END DESCRIPTION:
XS GIS Cut Line= 3
      2632975.05     13399425.02        2632725.       13399325.
      2632575.03     13399175.03
#Sta/Elev= 30
    4735   40.57  4737.7   40.57  4744.5   41.75  4774.1   39.84  4803.7   37.09
  4827.9   34.07  4833.3   34.14  4852.2   32.64  4857.6   32.78  4887.2   29.93
    4906   29.49  4918.1   28.13  4935.6   27.94  4950.5   27.06  4959.9   27.01
    4972   27.76  4982.8   27.37  4989.5    25.1  4992.6   23.45  4992.9   22.95
  4996.8   22.95  4997.1   23.45  5001.6   25.05  5007.8   25.05  5018.4      27
  5089.2   32.31  5145.7   37.74  5181.1   40.05  5212.9   43.57  5216.4   43.57
#Mann= 3 ,-1 , 0
    4735     .07       0  4992.6     .05       0  4997.1     .07       0
Bank Sta=4992.6,4997.1
XS Rating Curve= 0 ,0
Exp/Cntr=0.3,0.1

Type RM Length L Ch R = 1 ,24981   ,465,465,465
BEGIN DESCRIPTION:
TRIB 1 TO GUADALUPE RIVER 28.0
END DESCRIPTION:
XS GIS Cut Line= 3
      2633074.97     13399024.98        2632925.       13398925.
      2632624.98       13398975.
#Sta/Elev= 30
  4815.3   38.23  4843.8    36.7  4858.8   33.91  4879.9   32.49  4894.9   29.71
  4900.9   29.71  4909.9   28.77  4915.9   29.38  4923.4   28.23  4930.9   26.16
    4946   25.62    4952   26.26    4982   24.29    4988   24.64  5013.6   22.35
  5013.9   21.85  5017.8   21.85  5018.1   22.35  5035.2   23.66  5051.1   23.94
  5056.4   24.06  5107.1   29.01  5167.9   33.56  5188.2   34.35  5205.9   36.53
  5218.6    37.1  5266.7   42.34  5271.8   42.26  5279.4   43.45  5299.7   44.15
#Mann= 5 ,-1 , 0
  4815.3     .07       0  5013.6     .05       0  5018.1     .07       0
  5035.2     .05       0  5051.1     .07       0
Bank Sta=5013.6,5018.1
XS Rating Curve= 0 ,0
Exp/Cntr=0.3,0.1

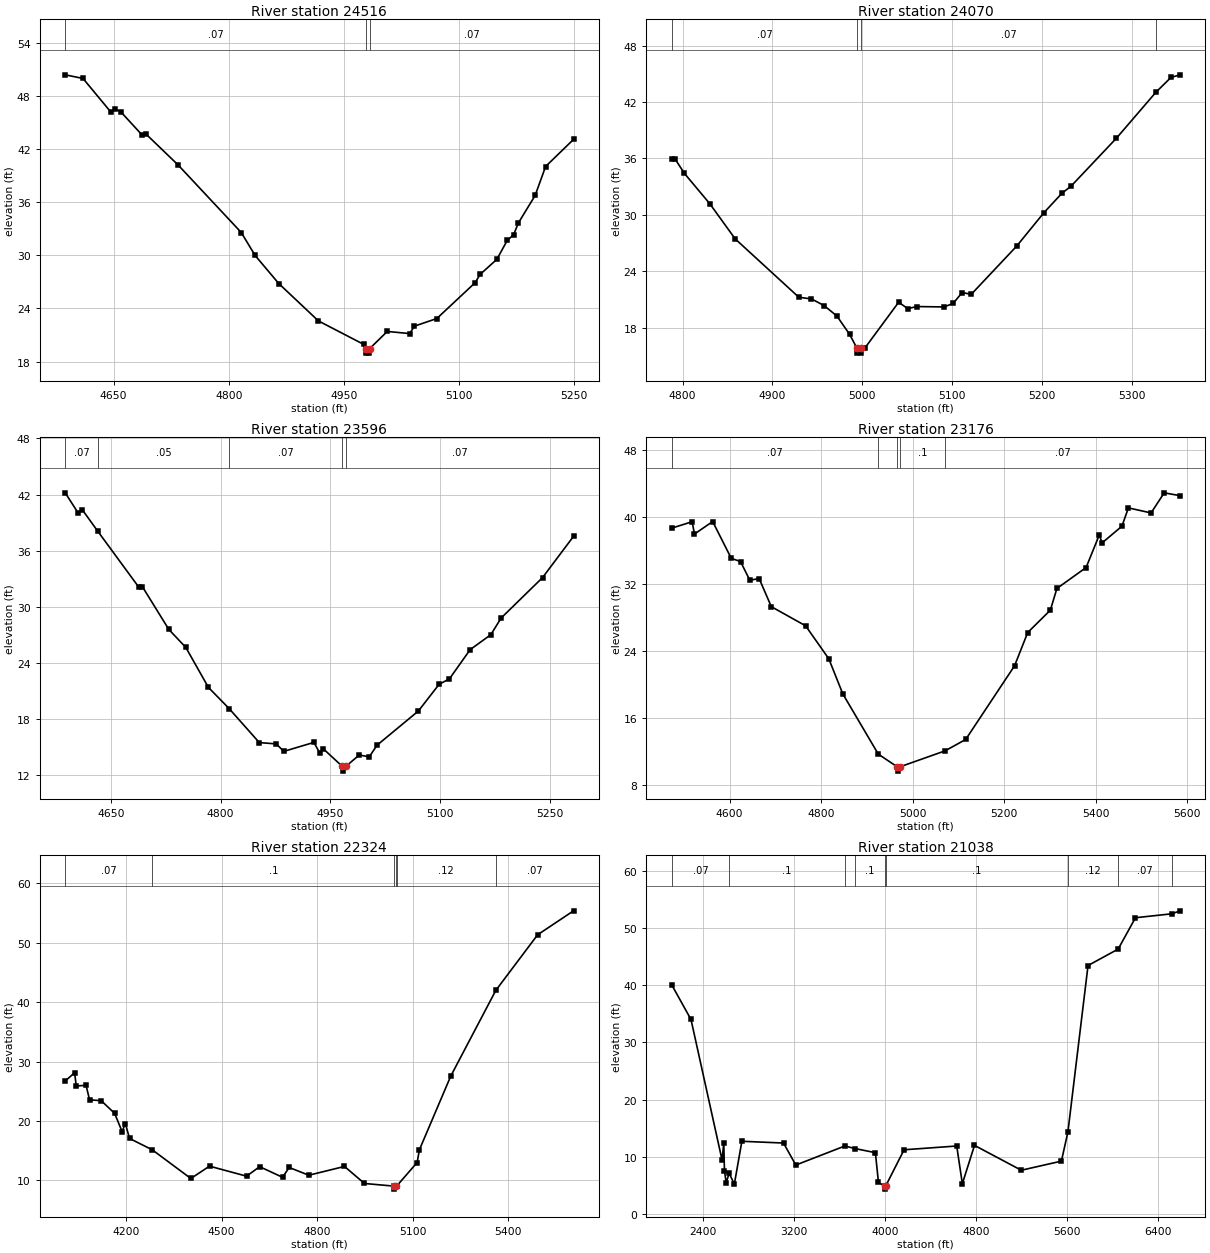
Type RM Length L Ch R = 1 ,24516   ,446,446,446
BEGIN DESCRIPTION:
TRIB 1 TO GUADALUPE RIVER 27.0
END DESCRIPTION:
XS GIS Cut Line= 3
      2633425.02       13398625.        2633025.       13398525.
      2632875.02     13398325.02
#Sta/Elev= 30
    4587    50.4  4610.2   49.99  4646.3   46.21  4651.4   46.55  4659.2   46.24
  4687.5   43.57  4692.7   43.67  4733.9   40.23  4816.4   32.58  4834.4   29.99
  4865.3   26.81  4916.9   22.59  4976.1   19.93  4978.9   19.45  4979.3   18.95
  4983.3   18.95  4983.6   19.45  5006.6    21.4  5035.8   21.16    5042      22
  5071.2   22.86  5121.2   26.92  5127.5   27.84  5149.3   29.54  5162.9   31.68
  5171.2   32.33  5177.5   33.67  5199.3   36.77  5212.9   40.04  5249.3    43.1
#Mann= 3 ,-1 , 0
    4587     .07       0  4978.9     .05       0  4983.6     .07       0
Bank Sta=4978.9,4983.6
XS Rating Curve= 0 ,0
Exp/Cntr=0.3,0.1

Type RM Length L Ch R = 1 ,24070   ,474,474,474
BEGIN DESCRIPTION:
TRIB 1 TO GUADALUPE RIVER 26.0
END DESCRIPTION:
XS GIS Cut Line= 3
      2633425.02     13398325.02        2633275.       13398175.
      2632925.02       13398125.
#Sta/Elev= 30
  4787.8   35.97  4791.4   35.97    4802   34.41  4830.3   31.18  4858.5   27.45
  4929.3   21.25  4943.4   21.07  4957.5   20.36  4971.7   19.25  4985.8   17.31
  4994.1   15.81  4994.4   15.31  4998.4   15.31  4998.8   15.81  5002.5   15.81
  5040.4   20.72  5050.5   20.04  5060.6   20.26  5090.9   20.22    5101   20.59
  5111.1   21.75  5121.2   21.56  5171.7   26.68    5202   30.23  5222.2   32.31
  5232.3   33.06  5282.8   38.16  5326.7   43.04  5343.4   44.61  5353.5   44.89
#Mann= 4 ,-1 , 0
  4787.8     .07       0  4994.1     .05       0  4998.8     .07       0
  5326.7     .05       0
Bank Sta=4994.1,4998.8
XS Rating Curve= 0 ,0
Exp/Cntr=0.3,0.1

Type RM Length L Ch R = 1 ,23596   ,420,420,420
BEGIN DESCRIPTION:
TRIB 1 TO GUADALUPE RIVER 25.0
END DESCRIPTION:
XS GIS Cut Line= 3
        2633575.     13398374.98        2633675.       13397975.
      2633475.03     13397775.03
#Sta/Elev= 30
  4587.6   42.19  4605.6      40  4610.8    40.4  4632.1   38.09  4688.1   32.12
  4693.2   32.15  4729.3   27.59  4752.5   25.67  4783.4    21.4  4811.8   19.13
    4853    15.5  4876.2   15.36  4886.5   14.56  4927.7   15.52  4935.5   14.41
  4940.6   14.83  4966.6   12.95  4966.9   12.45  4971.3   12.95  4989.6   14.17
  5003.4   13.98    5014   15.22  5070.6   18.88  5098.9   21.73    5113   22.31
  5141.3   25.43  5169.6   27.03  5183.7   28.81  5240.3   33.13  5282.7   37.54
#Mann= 5 ,-1 , 0
  4587.6     .07       0  4632.1     .05       0  4811.8     .07       0
  4966.6     .05       0  4971.3     .07       0
Bank Sta=4966.6,4971.3
XS Rating Curve= 0 ,0
Exp/Cntr=0.3,0.1

Type RM Length L Ch R = 1 ,23176   ,852,852,852
BEGIN DESCRIPTION:
TRIB 1 TO GUADALUPE RIVER 24.0
END DESCRIPTION:
XS GIS Cut Line= 3
      2634067.89     13398303.25        2633975.       13397775.
      2633608.89     13397332.34
#Sta/Elev= 30
  4473.4   38.63  4518.1    39.4  4523.2   37.93    4563   39.42  4603.6   35.03
  4623.9   34.64  4644.2   32.41  4664.5   32.62  4691.1   29.26  4766.1   26.97
  4816.8   23.03  4847.3   18.85  4924.9   11.65  4966.7   10.12  4967.1    9.62
  4971.5   10.12  5070.8   12.04  5115.9    13.4  5222.7    22.2  5251.4   26.17
  5300.9   28.84  5315.2   31.43    5379   33.93  5407.7    37.8  5414.2   36.88
  5457.2   38.86  5471.5   41.05    5521   40.45  5549.7   42.85  5584.2   42.51
#Mann= 5 ,-1 , 0
  4473.4     .07       0  4924.9      .1       0  4966.7     .05       0
  4971.5      .1       0  5070.8     .07       0
Bank Sta=4966.7,4971.5
XS Rating Curve= 0 ,0
Exp/Cntr=0.3,0.1

Type RM Length L Ch R = 1 ,22324   ,1286,1286,1286
BEGIN DESCRIPTION:
TRIB 1 TO GUADALUPE RIVER 23.0
END DESCRIPTION:
XS GIS Cut Line= 3
      2634363.03     13398268.57      2634595.94     13397305.02
      2634041.81     13397061.94
#Sta/Elev= 30
  4008.7   26.74  4038.2   28.12  4043.4   25.89  4074.1   26.02  4085.2   23.57
  4121.9   23.42  4163.8   21.29  4187.3   18.23  4197.6   19.57  4210.8   17.06
  4282.1   15.15  4403.3   10.32  4461.9    12.4  4578.2   10.71  4619.4   12.31
  4691.4   10.52    4712   12.18  4773.7   10.87  4885.7   12.35  4948.6    9.48
  5042.3    9.03  5042.6    8.53  5047.2    9.03    5050    9.07  5113.9   13.01
  5121.1   15.16  5219.4   27.55  5361.1      42  5492.4   51.36  5605.1   55.39
#Mann= 6 ,-1 , 0
  4008.7     .07       0  4282.1      .1       0  5042.3     .05       0
  5047.2      .1       0    5050     .12       0  5361.1     .07       0
Bank Sta=5042.3,5047.2
XS Rating Curve= 0 ,0
Exp/Cntr=0.3,0.1

Type RM Length L Ch R = 1 ,21038   ,0,0,0
BEGIN DESCRIPTION:
Mapping XS 0973e483
END DESCRIPTION:
XS GIS Cut Line= 4
      2634214.07     13398838.96      2635464.07     13396963.96
      2634813.03      13396430.1      2633460.23     13396169.95
#Sta/Elev= 30
  2122.7   40.12  2292.7   34.03  2566.1    9.39  2581.1   12.39  2587.1    7.54
  2602.2    5.42  2628.3    7.07  2674.3    5.17  2740.4   12.68  3106.9   12.37
  3215.1    8.51  3646.2   11.85  3734.6   11.41  3915.2   10.68  3942.3    5.47
  3999.9    4.79  4000.2    4.29  4004.8    4.79  4167.6   11.19    4631   11.85
  4680.5    5.24  4787.4   11.96  5199.3     7.6  5552.2     9.2  5609.4   14.32
  5786.4   43.49  6051.3   46.37  6203.9   51.87  6524.6   52.56  6595.7   53.08
#Mann= 9 ,-1 , 0
  2122.7     .07       0  2628.3      .1       0  3646.2     .15       0
  3734.6      .1       0  3999.9     .05       0  4004.8      .1       0
  5609.4     .12       0  6051.3     .07       0  6524.6    .035       0
Bank Sta=3999.9,4004.8
XS Rating Curve= 0 ,0
Exp/Cntr=0.3,0.1

Chan Stop Cuts=-1
Use User Specified Reach Order=0
Composite Channel Slope=5