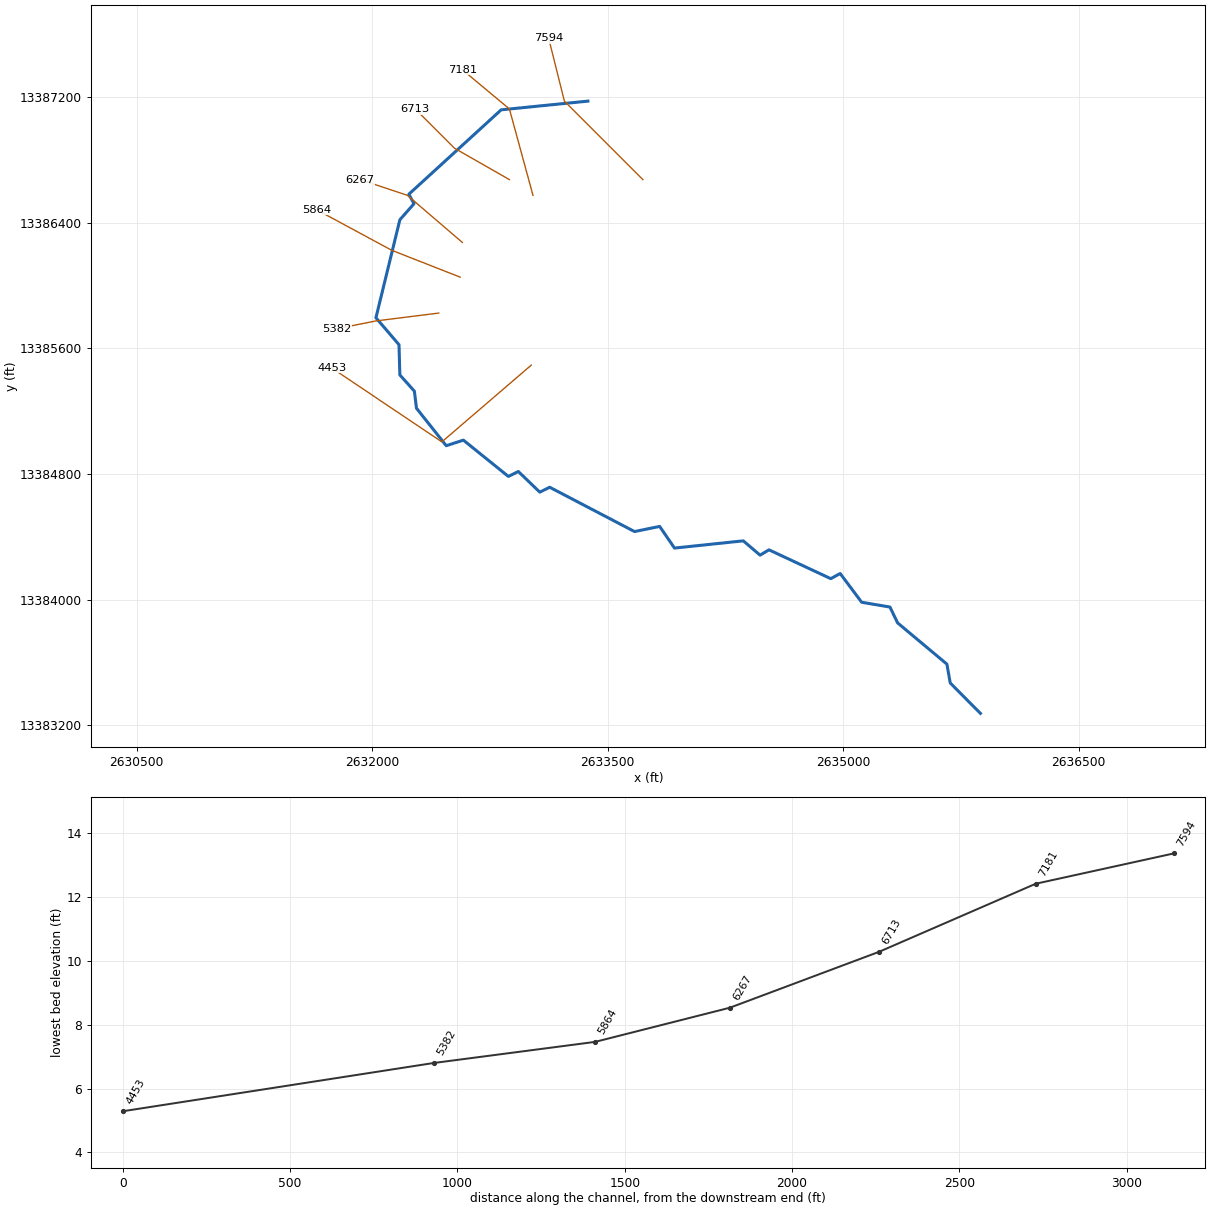
--- TRIB 1 TO KUY CREEK.prj (project) ---

Proj Title=TRIB 1 TO KUY CREEK Base Level Engineering
Current Plan=p01
Default Exp/Contr=0.3,0.1
English Units
Geom File=g01
Flow File=f01
Plan File=p01
Y Axis Title=Elevation
X Axis Title(PF)=Main Channel Distance
X Axis Title(XS)=Station
BEGIN DESCRIPTION:
TRIB 1 TO KUY CREEK
END DESCRIPTION:
DSS Export Rating Curves= 0
DSS Export Rating Curve Sorted= 0
DSS Export Volume Flow Curves= 0
DXF OffsetX= 0
DXF OffsetY= 0
DXF ScaleX= 1
DXF ScaleY= 10

--- TRIB 1 TO KUY CREEK.p01 (plan) ---

Plan Title=Multiple Run
Short Identifier=Multiple
Geom File=g01
Flow File=f01
Subcritical Flow
K Sum by GR= 0
Std Step Tol= 0.01
Critical Tol= 0.01
Num of Std Step Trials= 20
Max Error Tol= 0.3
Flow Tol Ratio= 0.001
Split Flow NTrial= 30
Split Flow Tol= 0.02
Split Flow Ratio= 0.02
Log Output Level= 0
Friction Slope Method= 1
Unsteady Friction Slope Method= 2
Unsteady Bridges Friction Slope Method= 1
Parabolic Critical Depth
Global Vel Dist=  1 , 1 , 1
Global Log Level= 0
CheckData=True
Encroach Param= -1, 0, 0, 0
BEGIN DESCRIPTION:
Multiple Run
END DESCRIPTION:

--- TRIB 1 TO KUY CREEK.f01 (steady flow) ---

Flow Title=Multiple
Number of Profiles=7
Profile Names=10-year,25-year,50-year,1pct_min,100-year,1pct_plu,500-year
River Rch & RM= TRIB 1 TO KUY CR,Reach-1,7594
     689    1081    1426     910    1815    3622    2906
River Rch & RM= TRIB 1 TO KUY CR,Reach-1,7181
     764    1204    1593    1018    2032    4055    3269
Boundary for River Rch & Prof#=TRIB 1 TO KUY CR,Reach-1,1
Up Type=0
Dn Type=3
Dn Slope=0.005
Boundary for River Rch & Prof#=TRIB 1 TO KUY CR,Reach-1,2
Up Type=0
Dn Type=3
Dn Slope=0.005
Boundary for River Rch & Prof#=TRIB 1 TO KUY CR,Reach-1,3
Up Type=0
Dn Type=3
Dn Slope=0.005
Boundary for River Rch & Prof#=TRIB 1 TO KUY CR,Reach-1,4
Up Type=0
Dn Type=3
Dn Slope=0.005
Boundary for River Rch & Prof#=TRIB 1 TO KUY CR,Reach-1,5
Up Type=0
Dn Type=3
Dn Slope=0.005
Boundary for River Rch & Prof#=TRIB 1 TO KUY CR,Reach-1,6
Up Type=0
Dn Type=3
Dn Slope=0.005
Boundary for River Rch & Prof#=TRIB 1 TO KUY CR,Reach-1,7
Up Type=0
Dn Type=3
Dn Slope=0.005

--- TRIB 1 TO KUY CREEK.g01 (geometry) ---

Geom Title=Existing Conditions
Program Version=4.10

River Reach=TRIB 1 TO KUY CR,Reach-1
Reach XY= 30
        2633375.       13387175.      2632822.34     13387119.54
      2632234.23     13386581.93      2632266.98     13386521.68
      2632177.08     13386419.14       2632024.6     13385795.13
      2632171.46     13385623.54      2632177.07     13385430.86
      2632269.46     13385327.42      2632282.86     13385218.83
      2632472.46     13384980.01      2632581.61     13385015.57
      2632868.33      13384784.3      2632931.67      13384815.7
      2633068.33      13384684.3      2633131.55     13384715.41
      2633671.77     13384433.23      2633831.95     13384465.83
      2633926.42     13384328.04      2634364.57     13384373.94
      2634471.67     13384283.01      2634528.23     13384316.75
      2634921.78     13384133.25      2634981.95     13384165.82
      2635118.79     13383982.81       2635298.9     13383952.29
      2635347.87     13383851.17      2635661.74     13383588.65
      2635682.86     13383468.83        2635875.       13383275.

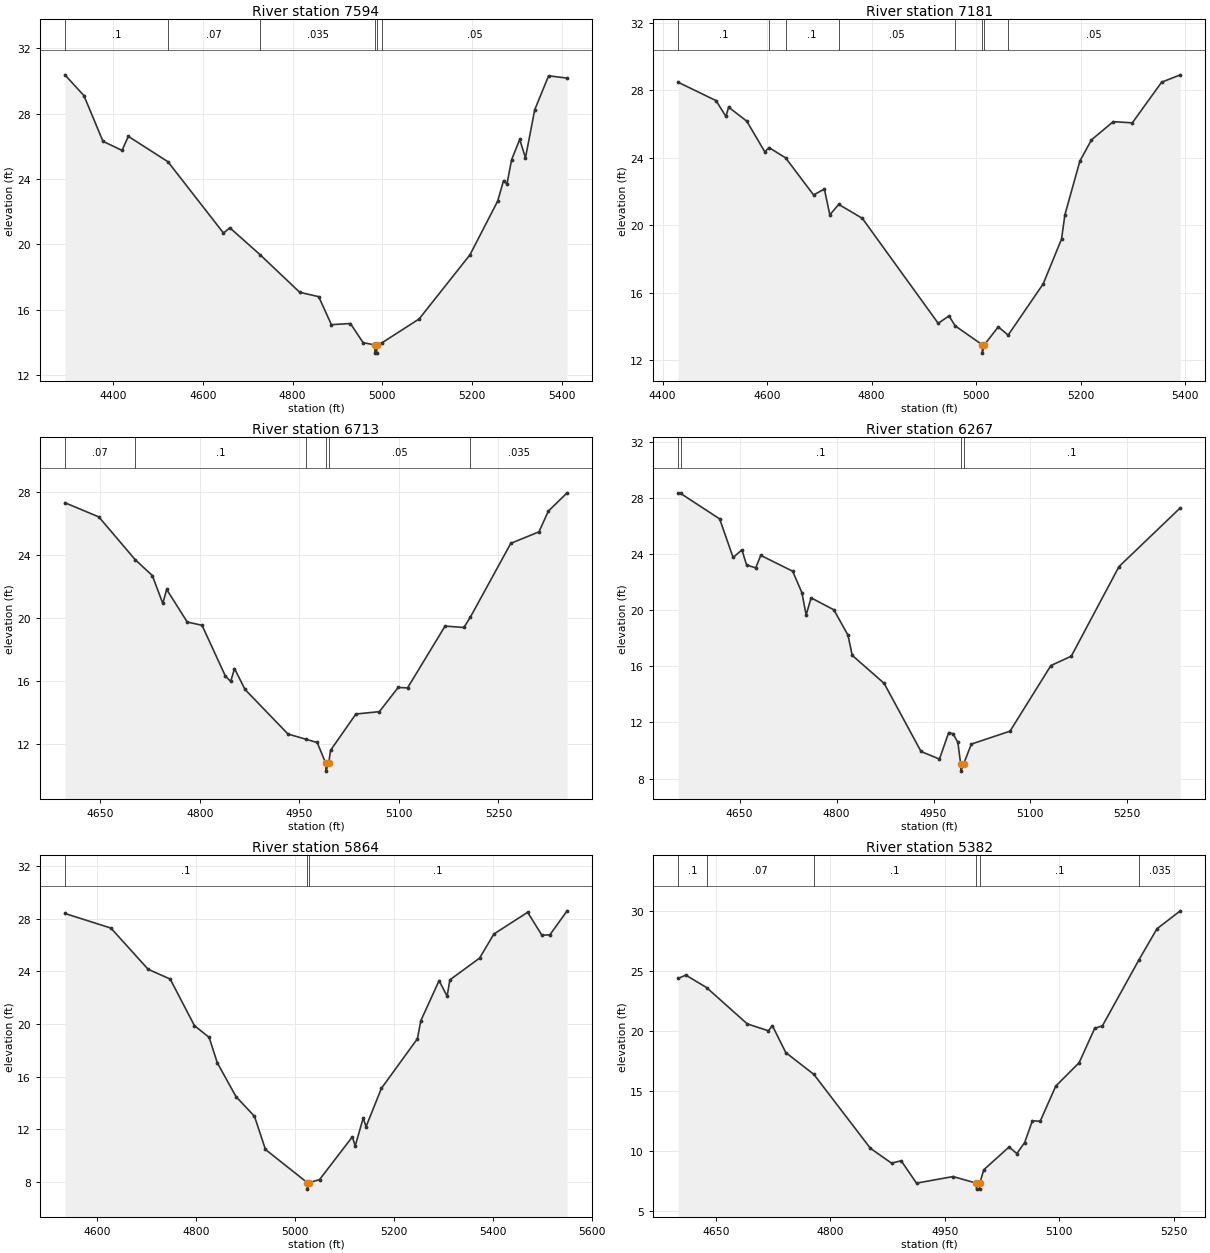
Type RM Length L Ch R = 1 ,7594    ,413,413,413
BEGIN DESCRIPTION:
TRIB 1 TO KUY CREEK 7.0
END DESCRIPTION:
XS GIS Cut Line= 3
      2633724.99     13386675.01        2633225.       13387175.
        2633125.     13387574.99
#Sta/Elev= 30
  4292.5   30.37  4334.9    29.1  4377.3   26.31  4419.8   25.75  4433.9   26.61
  4522.1   25.06    4646    20.7  4660.2   21.02  4728.2   19.36  4815.8   17.08
  4858.2   16.81  4886.5    15.1  4928.9   15.17  4957.2      14  4983.4   13.86
  4983.6   13.36  4987.3   13.36  4987.6   13.86  4999.8      14  5082.1   15.45
  5195.4   19.37  5257.3   22.66  5270.2    23.9  5277.9    23.7  5288.2   25.18
  5306.3   26.42  5319.1    25.3  5339.8   28.24  5370.7   30.31  5411.9   30.17
#Mann= 6 ,-1 , 0
  4292.5      .1       0  4522.1     .07       0  4728.2    .035       0
  4983.4     .05       0  4987.6    .035       0  4999.8     .05       0
Bank Sta=4983.4,4987.6
XS Rating Curve= 0 ,0
Exp/Cntr=0.3,0.1

Type RM Length L Ch R = 1 ,7181    ,468,468,468
BEGIN DESCRIPTION:
TRIB 1 TO KUY CREEK 6.0
END DESCRIPTION:
XS GIS Cut Line= 3
      2633024.99     13386575.04        2632875.       13387125.
      2632574.97     13387375.03
#Sta/Elev= 30
  4429.8   28.49  4502.3    27.4  4521.3   26.46  4526.5   27.01  4561.1   26.18
  4595.6   24.36  4603.7   24.61  4635.5      24  4688.9    21.8  4709.6   22.15
    4720   20.62    4737   21.24  4782.2   20.41  4927.3   14.18    4948   14.62
  4959.7   14.03  5011.4   12.91  5011.7   12.41  5015.7   12.91  5042.2   13.97
  5061.1   13.48  5128.1   16.52  5163.2   19.18  5169.7   20.63  5198.4   23.82
  5220.5   25.07  5262.1   26.15  5298.6   26.08  5354.6   28.49  5390.4   28.93
#Mann= 8 ,-1 , 0
  4429.8      .1       0  4603.7     .07       0  4635.5      .1       0
    4737     .05       0  4959.7    .035       0  5011.4    .035       0
  5015.7    .035       0  5061.1     .05       0
Bank Sta=5011.4,5015.7
XS Rating Curve= 0 ,0
Exp/Cntr=0.3,0.1

Type RM Length L Ch R = 1 ,6713    ,446,446,446
BEGIN DESCRIPTION:
TRIB 1 TO KUY CREEK 5.0
END DESCRIPTION:
XS GIS Cut Line= 3
      2632874.98     13386675.01        2632525.       13386875.
      2632275.03     13387124.97
#Sta/Elev= 30
  4596.9   27.34    4648   26.44  4702.6   23.73  4728.6   22.71  4744.4   20.94
  4750.2   21.83  4781.2   19.76  4803.5   19.55  4838.7   16.32  4846.7   15.98
  4852.4    16.8  4868.3   15.47    4933   12.64  4960.5    12.3    4977    12.1
  4989.9   10.78  4990.2   10.28  4994.3   10.78  4997.1    11.6  5035.3   13.91
  5070.7   14.06    5099    15.6  5113.1   15.57  5169.7    19.5    5198   19.41
  5207.9   20.08  5268.7   24.76  5311.1   25.49  5325.3   26.81  5353.5   27.97
#Mann= 6 ,-1 , 0
  4596.9     .07       0  4702.6      .1       0  4960.5     .05       0
  4989.9     .05       0  4994.3     .05       0  5207.9    .035       0
Bank Sta=4989.9,4994.3
XS Rating Curve= 0 ,0
Exp/Cntr=0.3,0.1

Type RM Length L Ch R = 1 ,6267    ,403,403,403
BEGIN DESCRIPTION:
TRIB 1 TO KUY CREEK 4.0
END DESCRIPTION:
XS GIS Cut Line= 3
      2632575.04     13386274.97        2632225.       13386575.
      2631924.96     13386675.01
#Sta/Elev= 30
  4554.7   28.38  4558.5   28.34    4619   26.52  4639.8   23.77  4653.5   24.31
  4660.7   23.23  4674.9   23.03  4682.6   23.92    4732   22.79  4746.3   21.26
  4752.9   19.67  4760.5   20.89  4795.7   20.04  4817.6   18.23  4824.2   16.79
  4873.6   14.79  4930.7    9.93  4959.2    9.39  4973.5   11.28  4980.1    11.2
  4987.7   10.59  4992.1    9.03  4992.4    8.53  4996.5    9.03  5008.6   10.46
  5068.4   11.38  5131.7   16.06  5163.3   16.73  5237.1   23.12    5332   27.31
#Mann= 4 ,-1 , 0
  4554.7     .07       0  4558.5      .1       0  4992.1     .05       0
  4996.5      .1       0
Bank Sta=4992.1,4996.5
XS Rating Curve= 0 ,0
Exp/Cntr=0.3,0.1

Type RM Length L Ch R = 1 ,5864    ,482,482,482
BEGIN DESCRIPTION:
TRIB 1 TO KUY CREEK 3.0
END DESCRIPTION:
XS GIS Cut Line= 3
      2632561.56     13386053.65        2632125.       13386225.
      2631644.88     13386484.21
#Sta/Elev= 30
  4535.2   28.39  4628.2   27.28  4703.4   24.15  4747.9   23.41  4796.8   19.88
  4826.6   18.98    4843   17.06  4880.8   14.49  4918.2   12.99  4940.4   10.47
  5024.7    7.96    5025    7.46  5029.1    7.96  5049.6    8.18    5116   11.43
  5121.7   10.74  5137.9   12.86  5143.6    12.2  5174.6   15.11  5247.4   18.88
  5254.2   20.24  5291.2   23.29  5307.4   22.11    5313   23.35    5373      25
  5401.9   26.83  5470.1   28.48  5498.7   26.75  5514.9   26.76  5549.8   28.59
#Mann= 3 ,-1 , 0
  4535.2      .1       0  5024.7     .05       0  5029.1      .1       0
Bank Sta=5024.7,5029.1
XS Rating Curve= 0 ,0
Exp/Cntr=0.3,0.1

Type RM Length L Ch R = 1 ,5382    ,929,929,929
BEGIN DESCRIPTION:
TRIB 1 TO KUY CREEK 2.0
END DESCRIPTION:
XS GIS Cut Line= 3
      2632425.03       13385825.        2632025.       13385775.
      2631774.99       13385725.
#Sta/Elev= 30
  4600.6    24.4  4610.7   24.68  4637.9   23.64  4691.3    20.6    4719   20.03
  4724.1   20.46  4741.7   18.21  4778.6   16.38  4852.6   10.21  4880.3    8.97
  4892.9    9.17    4913     7.3  4960.9    7.85  4991.4     7.3  4991.7     6.8
  4995.6     6.8  4995.9     7.3  5001.2    8.42  5034.3   10.32  5044.5    9.77
  5054.7   10.69  5064.9   12.51  5075.1   12.47  5095.5   15.41  5126.1   17.36
  5146.5   20.23  5156.7   20.45  5204.6   25.97  5228.1   28.55  5258.7   30.05
#Mann= 6 ,-1 , 0
  4600.6      .1       0  4637.9     .07       0  4778.6      .1       0
  4991.4     .05       0  4995.9      .1       0  5204.6    .035       0
Bank Sta=4991.4,4995.9
XS Rating Curve= 0 ,0
Exp/Cntr=0.3,0.1

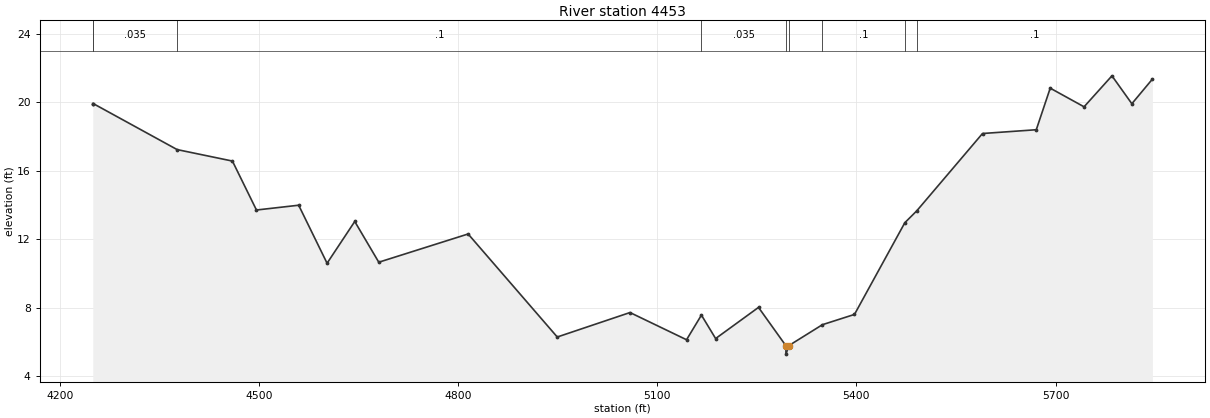
Type RM Length L Ch R = 1 ,4453    ,0,0,0
BEGIN DESCRIPTION:
TRIB 1 TO KUY CREEK 1.0
END DESCRIPTION:
XS GIS Cut Line= 3
      2633013.98     13385493.29      2632444.63     13385004.32
      2631742.28     13385475.94
#Sta/Elev= 30
  4249.5   19.93  4250.1   19.93  4376.6   17.24  4459.9   16.57  4496.1   13.71
  4559.7   13.99  4602.5    10.6  4644.2   13.04  4680.4   10.66    4815   12.31
  4949.3    6.29  5058.9    7.72  5144.1    6.13  5166.5    7.57  5187.9     6.2
  5252.5    8.02  5293.6    5.79  5293.9    5.29  5298.3    5.79  5348.8    7.01
  5397.1    7.61    5473   12.97  5490.9   13.66    5590   18.18    5671    18.4
    5692   20.83    5743   19.74    5785   21.55    5815   19.92    5846   21.36
#Mann= 9 ,-1 , 0
  4249.5      .1       0  4250.1    .035       0  4376.6      .1       0
  5166.5    .035       0  5293.6     .05       0  5298.3    .035       0
  5348.8      .1       0    5473    .035       0  5490.9      .1       0
Bank Sta=5293.6,5298.3
XS Rating Curve= 0 ,0
Exp/Cntr=0.3,0.1

Chan Stop Cuts=-1
Use User Specified Reach Order=0
Composite Channel Slope=5