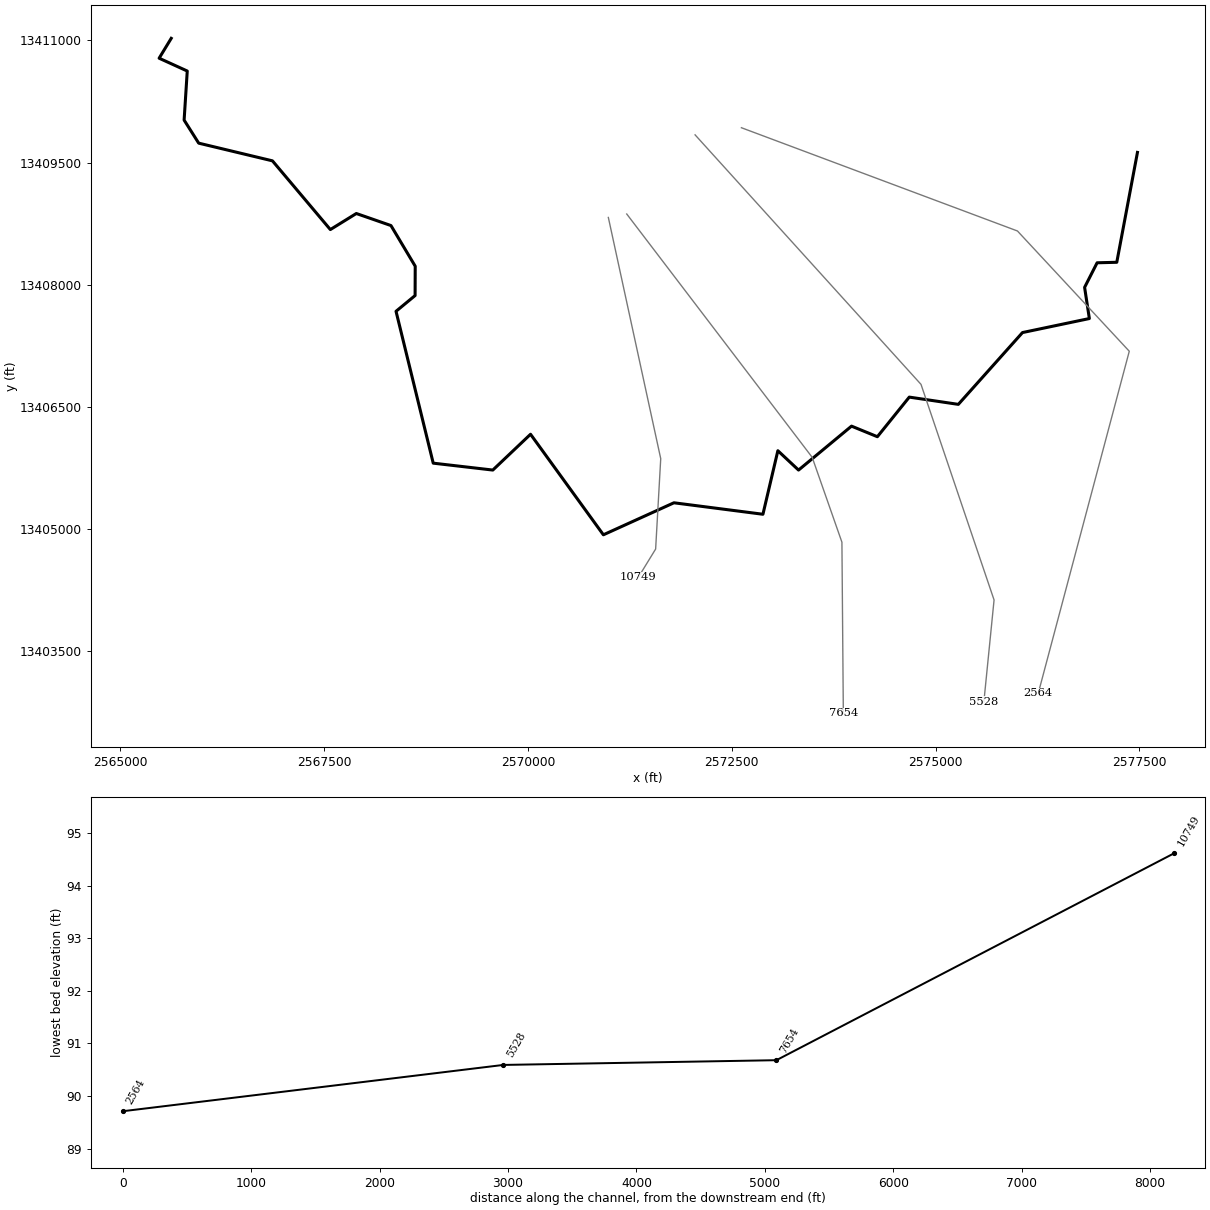
--- TRIB 12 TO KUY CREEK.prj (project) ---

Proj Title=TRIB 12 TO KUY CREEK Base Level Engineering
Current Plan=p01
Default Exp/Contr=0.3,0.1
English Units
Geom File=g01
Flow File=f01
Plan File=p01
Y Axis Title=Elevation
X Axis Title(PF)=Main Channel Distance
X Axis Title(XS)=Station
BEGIN DESCRIPTION:
TRIB 12 TO KUY CREEK
END DESCRIPTION:
DSS Export Rating Curves= 0
DSS Export Rating Curve Sorted= 0
DSS Export Volume Flow Curves= 0
DXF OffsetX= 0
DXF OffsetY= 0
DXF ScaleX= 1
DXF ScaleY= 10

--- TRIB 12 TO KUY CREEK.p01 (plan) ---

Plan Title=Multiple Run
Short Identifier=Multiple
Geom File=g01
Flow File=f01
Subcritical Flow
K Sum by GR= 0
Std Step Tol= 0.01
Critical Tol= 0.01
Num of Std Step Trials= 20
Max Error Tol= 0.3
Flow Tol Ratio= 0.001
Split Flow NTrial= 30
Split Flow Tol= 0.02
Split Flow Ratio= 0.02
Log Output Level= 0
Friction Slope Method= 1
Unsteady Friction Slope Method= 2
Unsteady Bridges Friction Slope Method= 1
Parabolic Critical Depth
Global Vel Dist=  1 , 1 , 1
Global Log Level= 0
CheckData=True
Encroach Param= -1, 0, 0, 0
BEGIN DESCRIPTION:
Multiple Run
END DESCRIPTION:

--- TRIB 12 TO KUY CREEK.f01 (steady flow) ---

Flow Title=Multiple
Number of Profiles=7
Profile Names=10-year,25-year,50-year,1pct_min,100-year,1pct_plu,500-year
River Rch & RM= TRIB 12 TO KUY C,Reach-1,10749
     647     986    1272     790    1576    3145    2396
River Rch & RM= TRIB 12 TO KUY C,Reach-1,7654
     710    1079    1390     862    1719    3430    2602
Boundary for River Rch & Prof#=TRIB 12 TO KUY C,Reach-1,1
Up Type=0
Dn Type=3
Dn Slope=0.005
Boundary for River Rch & Prof#=TRIB 12 TO KUY C,Reach-1,2
Up Type=0
Dn Type=3
Dn Slope=0.005
Boundary for River Rch & Prof#=TRIB 12 TO KUY C,Reach-1,3
Up Type=0
Dn Type=3
Dn Slope=0.005
Boundary for River Rch & Prof#=TRIB 12 TO KUY C,Reach-1,4
Up Type=0
Dn Type=3
Dn Slope=0.005
Boundary for River Rch & Prof#=TRIB 12 TO KUY C,Reach-1,5
Up Type=0
Dn Type=3
Dn Slope=0.005
Boundary for River Rch & Prof#=TRIB 12 TO KUY C,Reach-1,6
Up Type=0
Dn Type=3
Dn Slope=0.005
Boundary for River Rch & Prof#=TRIB 12 TO KUY C,Reach-1,7
Up Type=0
Dn Type=3
Dn Slope=0.005

--- TRIB 12 TO KUY CREEK.g01 (geometry) ---

Geom Title=Existing Conditions
Program Version=4.10

River Reach=TRIB 12 TO KUY C,Reach-1
Reach XY= 30
        2565625.       13411025.      2565476.61     13410781.03
      2565821.55     13410623.81       2565783.1     13410021.71
      2565961.79     13409738.63      2566866.51     13409521.46
      2567576.43     13408678.01      2567895.05     13408875.21
      2568319.88     13408727.32      2568617.39     13408228.33
      2568615.85     13407868.27      2568381.93     13407675.01
       2568838.2     13405811.27      2569568.95     13405726.58
      2570031.67     13406166.05      2570924.98     13404932.08
      2571790.42     13405324.97      2572881.78     13405184.13
      2573064.98     13405964.06      2573318.56     13405726.43
      2573968.34     13406265.69      2574285.32     13406135.82
      2574676.65     13406621.84      2575278.23     13406532.83
        2576065.     13407414.04      2576885.11      13407586.1
      2576826.79     13407968.89      2576980.26     13408270.41
      2577221.39     13408276.47        2577475.       13409625.

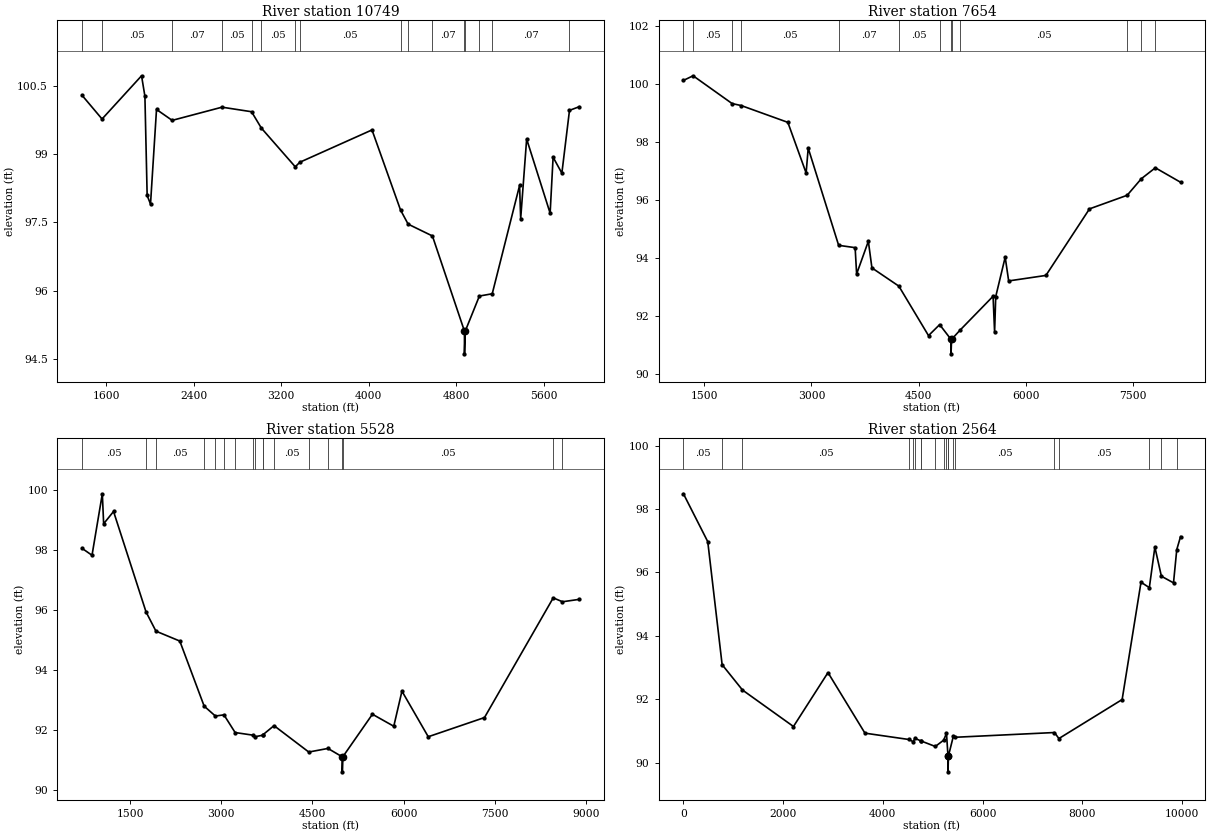
Type RM Length L Ch R = 1 ,10749   ,3095,3095,3095
BEGIN DESCRIPTION:
Mapping XS 24a188cb
END DESCRIPTION:
XS GIS Cut Line= 4
      2570985.89     13408826.66      2571628.34     13405866.45
      2571565.84     13404757.08       2571353.1     13404409.69
#Sta/Elev= 30
  1378.4  100.29    1561   99.77  1922.4  100.72  1953.1  100.27  1973.6   98.09
  2004.3    97.9  2059.2   99.98  2202.5   99.74  2658.4  100.03  2928.6   99.93
  3018.5   99.57  3328.4   98.72  3370.2   98.82  4030.4   99.53  4291.5   97.77
  4360.9   97.46  4583.2    97.2    4876   95.11  4876.5   94.61  4883.5   95.11
  5012.7   95.88  5130.3   95.93  5380.5   98.31  5390.5   97.58  5445.1   99.33
  5659.9    97.7  5687.1   98.93  5767.3   98.58    5837   99.96    5926  100.04
#Mann= 16 ,-1 , 0
  1378.4     .07       0    1561     .05       0  2202.5     .07       0
  2658.4     .05       0  2928.6     .07       0  3018.5     .05       0
  3328.4     .07       0  3370.2     .05       0  4291.5     .07       0
  4360.9     .05       0  4583.2     .07       0    4876     .05       0
  4883.5     .07       0  5012.7     .05       0  5130.3     .07       0
    5837     .05       0
Bank Sta=4876,4883.5
XS Rating Curve= 0 ,0
Exp/Cntr=0.3,0.1

Type RM Length L Ch R = 1 ,7654    ,2126,2126,2126
BEGIN DESCRIPTION:
Mapping XS 0546b4c0
END DESCRIPTION:
XS GIS Cut Line= 4
      2571211.58     13408868.94      2573485.91      13405882.8
      2573850.49     13404841.13      2573867.85     13402740.44
#Sta/Elev= 30
  1209.2  100.13  1344.5  100.29  1890.5   99.33  2019.3   99.26  2670.7   98.68
  2926.5   96.93  2955.6   97.79  3381.7   94.43  3612.5   94.35  3633.3   93.44
  3797.5   94.57  3847.4   93.65  4224.2   93.02  4639.5   91.31  4795.3   91.69
  4954.2   91.18  4954.7   90.68  4962.4   91.18  5077.6   91.49  5543.2   92.67
  5564.4   91.43  5580.4   92.66  5712.7   94.02  5761.3    93.2  6282.6   93.39
  6892.6   95.69  7419.9   96.16  7617.2   96.73  7814.5   97.11  8167.2   96.61
#Mann= 13 ,-1 , 0
  1209.2     .07       0  1344.5     .05       0  1890.5     .07       0
  2019.3     .05       0  3381.7     .07       0  4224.2     .05       0
  4795.3     .07       0  4954.2     .05       0  4962.4     .07       0
  5077.6     .05       0  7419.9    .035       0  7617.2     .05       0
  7814.5     .07       0
Bank Sta=4954.2,4962.4
XS Rating Curve= 0 ,0
Exp/Cntr=0.3,0.1

Type RM Length L Ch R = 1 ,5528    ,2964,2964,2964
BEGIN DESCRIPTION:
Mapping XS b8ef36db
END DESCRIPTION:
XS GIS Cut Line= 4
      2572049.75     13409840.49       2574820.6     13406777.97
      2575716.43     13404132.14      2575591.43     13402882.12
#Sta/Elev= 30
     709   98.04   872.4   97.81    1042   99.86  1063.7   98.86  1226.6   99.27
  1761.5   95.92  1924.3   95.28  2316.8   94.95  2717.6   92.78  2902.4   92.45
    3043   92.49  3227.1    91.9  3529.3   91.81  3551.3   91.76  3680.4   91.81
    3681   91.82  3867.1   92.13  4438.8   91.25  4754.6   91.37    4990   91.09
  4990.5   90.59  4998.3   91.09  5486.1   92.51  5837.4   92.11  5971.8   93.28
  6404.6   91.76    7330    92.4  8461.1   96.39  8613.3   96.26  8888.6   96.34
#Mann= 18 ,-1 , 0
     709     .05       0  1761.5     .07       0  1924.3     .05       0
  2717.6     .07       0  2902.4     .05       0    3043     .07       0
  3227.1      .1       0  3529.3     .05       0  3551.3      .1       0
  3680.4     .05       0    3681     .07       0  3867.1     .05       0
  4438.8     .07       0  4754.6     .05       0    4990     .05       0
  4998.3     .05       0  8461.1     .07       0  8613.3     .05       0
Bank Sta=4990,4998.3
XS Rating Curve= 0 ,0
Exp/Cntr=0.3,0.1

Type RM Length L Ch R = 1 ,2564    ,0,0,0
BEGIN DESCRIPTION:
TRIB 12 TO KUY CREEK 1.0
END DESCRIPTION:
XS GIS Cut Line= 4
      2572617.86     13409927.94      2576003.27     13408660.58
       2577374.8     13407184.88       2576258.6     13402988.18
#Sta/Elev= 30
     -.6   98.48   487.5   96.97   775.7   93.09  1184.3   92.29  2206.6   91.14
  2899.1   92.84  3640.6   90.93  4522.7   90.73  4610.4   90.66  4641.5   90.77
  4769.1   90.68  4772.2   90.68  5052.3   90.51  5220.1   90.71  5276.2   90.93
  5306.3   90.21  5306.8   89.71    5315   90.21  5416.7   90.85    5447    90.8
  7442.4   90.95  7530.9   90.76  8799.6   91.99    9178   95.69  9345.2   95.52
  9456.3    96.8  9586.8   95.88  9829.9   95.67  9895.4   96.72  9971.5   97.13
#Mann= 20 ,-1 , 0
     -.6     .05       0   775.7     .07       0  1184.3     .05       0
  4522.7     .07       0  4610.4     .05       0  4641.5     .07       0
  4769.1     .05       0  4772.2     .07       0  5052.3     .05       0
  5220.1     .07       0  5276.2     .05       0  5306.3     .05       0
    5315     .05       0  5416.7     .07       0    5447     .05       0
  7442.4     .07       0  7530.9     .05       0  9345.2     .07       0
  9586.8     .05       0  9895.4      .1       0
Bank Sta=5306.3,5315
XS Rating Curve= 0 ,0
Exp/Cntr=0.3,0.1

Chan Stop Cuts=-1
Use User Specified Reach Order=0
Composite Channel Slope=5