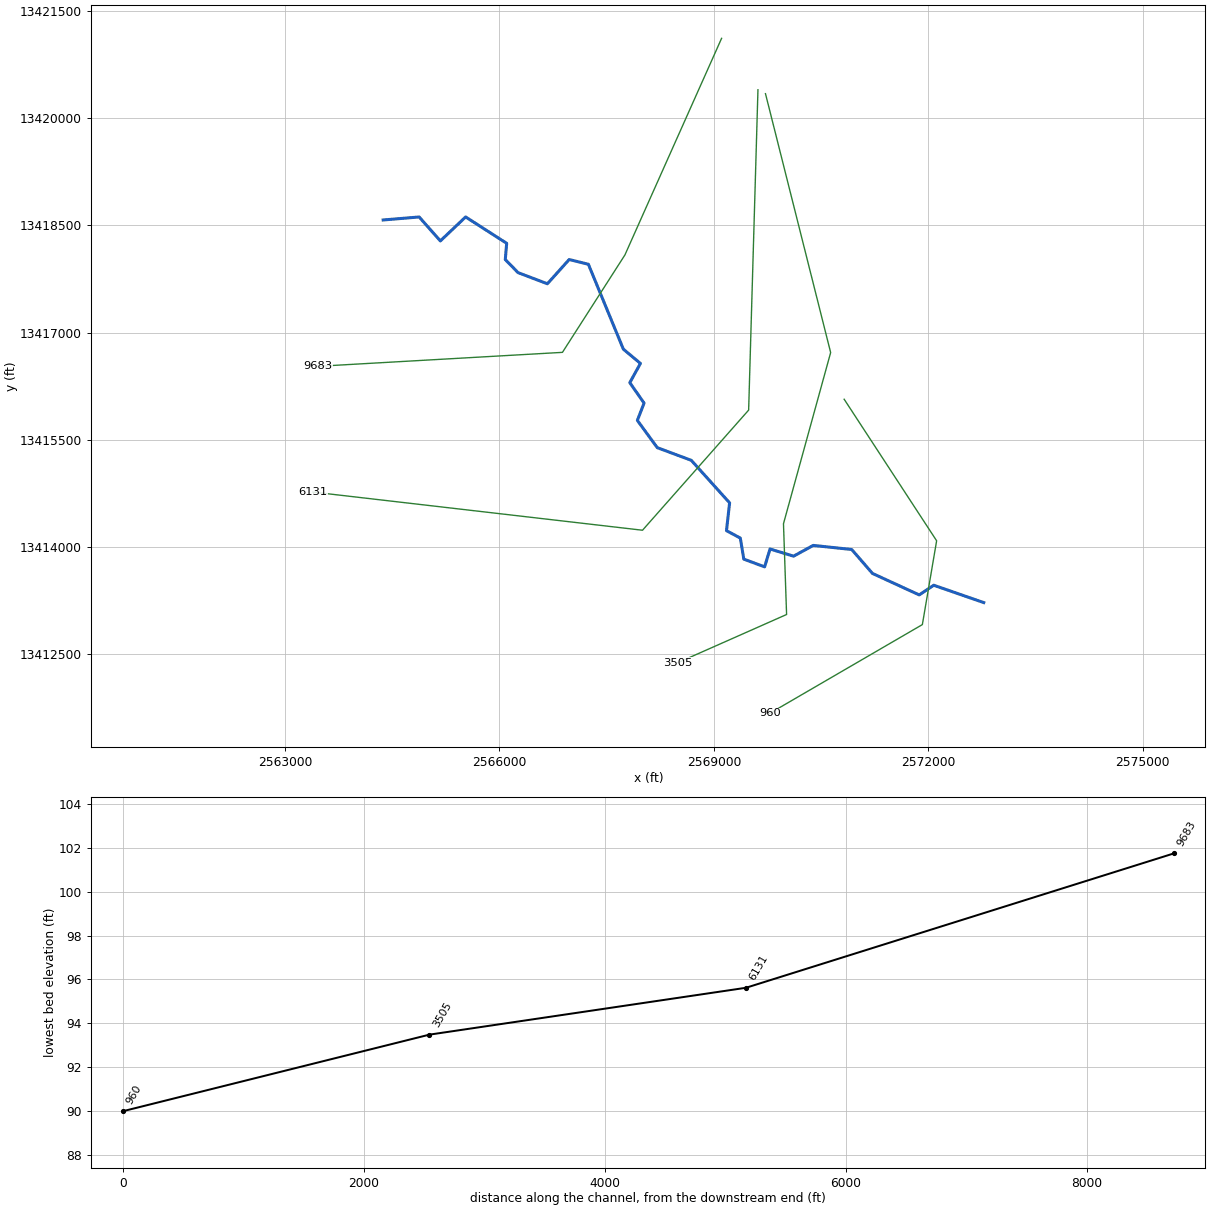
--- TRIB 14 TO KUY CREEK.prj (project) ---

Proj Title=TRIB 14 TO KUY CREEK Base Level Engineering
Current Plan=p01
Default Exp/Contr=0.3,0.1
English Units
Geom File=g01
Flow File=f01
Plan File=p01
Y Axis Title=Elevation
X Axis Title(PF)=Main Channel Distance
X Axis Title(XS)=Station
BEGIN DESCRIPTION:
TRIB 14 TO KUY CREEK
END DESCRIPTION:
DSS Export Rating Curves= 0
DSS Export Rating Curve Sorted= 0
DSS Export Volume Flow Curves= 0
DXF OffsetX= 0
DXF OffsetY= 0
DXF ScaleX= 1
DXF ScaleY= 10

--- TRIB 14 TO KUY CREEK.p01 (plan) ---

Plan Title=Multiple Run
Short Identifier=Multiple
Geom File=g01
Flow File=f01
Subcritical Flow
K Sum by GR= 0
Std Step Tol= 0.01
Critical Tol= 0.01
Num of Std Step Trials= 20
Max Error Tol= 0.3
Flow Tol Ratio= 0.001
Split Flow NTrial= 30
Split Flow Tol= 0.02
Split Flow Ratio= 0.02
Log Output Level= 0
Friction Slope Method= 1
Unsteady Friction Slope Method= 2
Unsteady Bridges Friction Slope Method= 1
Parabolic Critical Depth
Global Vel Dist=  1 , 1 , 1
Global Log Level= 0
CheckData=True
Encroach Param= -1, 0, 0, 0
BEGIN DESCRIPTION:
Multiple Run
END DESCRIPTION:

--- TRIB 14 TO KUY CREEK.f01 (steady flow) ---

Flow Title=Multiple
Number of Profiles=7
Profile Names=10-year,25-year,50-year,1pct_min,100-year,1pct_plu,500-year
River Rch & RM= TRIB 14 TO KUY C,Reach-1,9683
     490     736     941     580    1158    2310    1732
River Rch & RM= TRIB 14 TO KUY C,Reach-1,3505
     663    1015    1313     818    1633    3257    2498
River Rch & RM= TRIB 14 TO KUY C,Reach-1,960
     828    1278    1663    1042    2079    4149    3217
Boundary for River Rch & Prof#=TRIB 14 TO KUY C,Reach-1,1
Up Type=0
Dn Type=3
Dn Slope=0.005
Boundary for River Rch & Prof#=TRIB 14 TO KUY C,Reach-1,2
Up Type=0
Dn Type=3
Dn Slope=0.005
Boundary for River Rch & Prof#=TRIB 14 TO KUY C,Reach-1,3
Up Type=0
Dn Type=3
Dn Slope=0.005
Boundary for River Rch & Prof#=TRIB 14 TO KUY C,Reach-1,4
Up Type=0
Dn Type=3
Dn Slope=0.005
Boundary for River Rch & Prof#=TRIB 14 TO KUY C,Reach-1,5
Up Type=0
Dn Type=3
Dn Slope=0.005
Boundary for River Rch & Prof#=TRIB 14 TO KUY C,Reach-1,6
Up Type=0
Dn Type=3
Dn Slope=0.005
Boundary for River Rch & Prof#=TRIB 14 TO KUY C,Reach-1,7
Up Type=0
Dn Type=3
Dn Slope=0.005

--- TRIB 14 TO KUY CREEK.g01 (geometry) ---

Geom Title=Existing Conditions
Program Version=4.10

River Reach=TRIB 14 TO KUY C,Reach-1
Reach XY= 30
        2564375.       13418575.      2564878.32     13418616.96
       2565174.8     13418281.98      2565528.41     13418617.23
      2566102.51     13418248.39      2566082.82     13418021.59
      2566261.67     13417838.65      2566671.78     13417682.87
      2566976.42     13418021.96      2567245.16     13417955.39
       2567734.3     13416768.32      2567973.04     13416569.12
      2567824.47     13416300.12      2568024.07     13416014.52
      2567930.06      13415772.7      2568208.32     13415391.64
      2568684.68     13415214.22      2569220.27     13414619.71
      2569176.53     13414230.83      2569369.72     13414127.71
      2569418.67       13413833.       2569709.8     13413724.84
      2569785.43     13413974.47      2570114.83      13413874.5
      2570390.22     13414024.76      2570928.34      13413967.4
       2571218.5     13413632.73      2571871.59     13413332.77
        2572075.     13413467.92        2572775.       13413225.

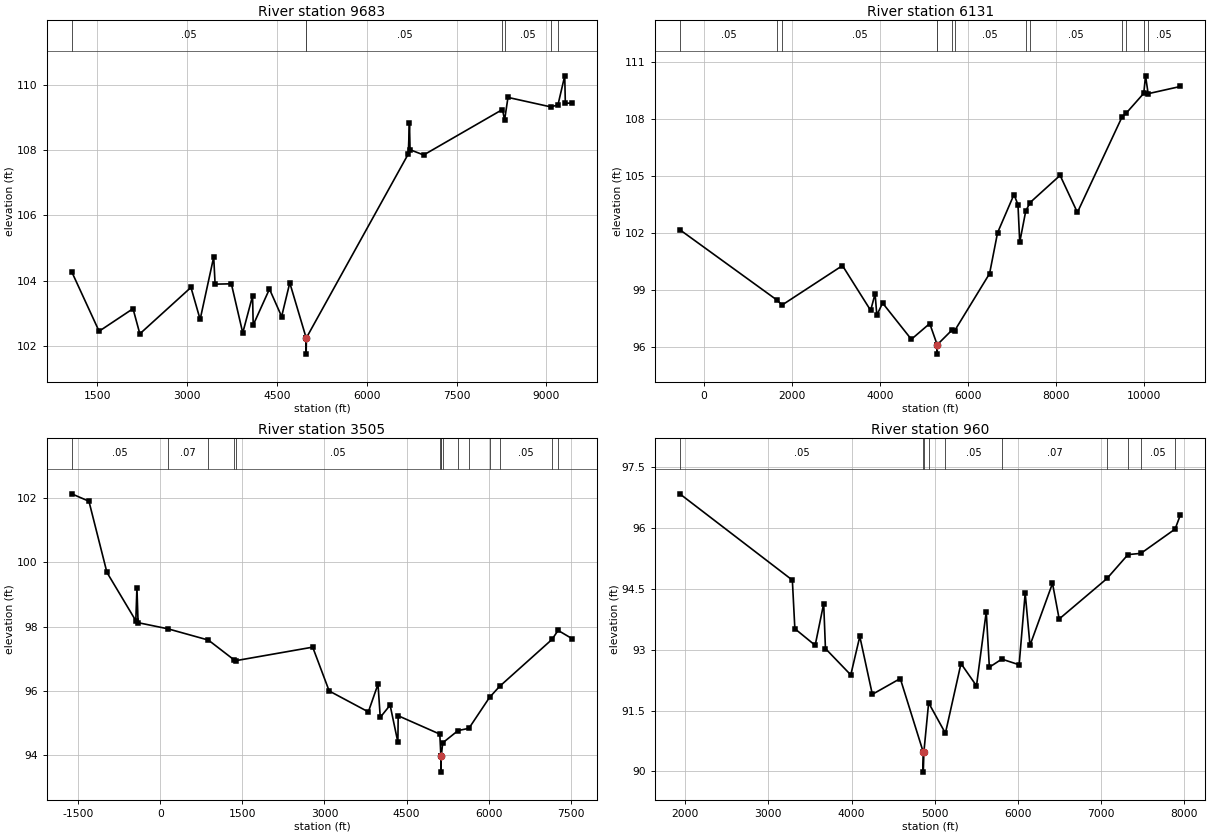
Type RM Length L Ch R = 1 ,9683    ,3552,3552,3552
BEGIN DESCRIPTION:
Mapping XS 3e9e8b30
END DESCRIPTION:
XS GIS Cut Line= 4
      2569108.16     13421114.61      2567755.79     13418085.45
      2566882.32     13416723.97       2563458.9     13416528.72
#Sta/Elev= 30
    1070  104.28  1527.8  102.46  2094.6  103.15  2208.5  102.38  3062.7   103.8
    3216  102.82  3442.7  104.73  3465.9   103.9  3737.7  103.91  3927.9  102.41
  4092.1  103.54  4102.4  102.65  4374.2  103.75  4577.6  102.91  4713.7  103.94
  4986.7  102.26  4987.1  101.76  4991.9  102.26  6693.4  107.88  6713.4  108.82
  6723.4  108.01  6950.8  107.85  8267.1  109.24  8302.8  108.92  8359.4  109.61
    9075  109.32  9194.3  109.38  9307.6  110.27  9317.6  109.43  9433.9  109.44
#Mann= 7 ,-1 , 0
    1070     .05       0  4986.7     .05       0  4991.9     .05       0
  8267.1    .035       0  8302.8     .05       0    9075     .07       0
  9194.3     .05       0
Bank Sta=4986.7,4991.9
XS Rating Curve= 0 ,0
Exp/Cntr=0.3,0.1

Type RM Length L Ch R = 1 ,6131    ,2626,2626,2626
BEGIN DESCRIPTION:
Mapping XS 2f070cde
END DESCRIPTION:
XS GIS Cut Line= 4
       2569616.7      13420395.9      2569486.49     13415916.68
      2568002.11     13414236.99      2563392.72     13414770.85
#Sta/Elev= 30
  -545.7  102.17  1669.4   98.45  1773.5    98.2  3146.8  100.28    3787   97.92
  3887.1    98.8  3927.1   97.67  4057.8   98.31  4710.2    96.4  5127.6   97.23
  5295.6   96.12    5296   95.62    5301   96.12  5629.6   96.88  5692.6   96.85
  6486.2   99.86  6667.4  102.01  7039.8  104.02  7130.4  103.49  7170.7  101.51
  7306.8  103.15    7406   103.6  8086.8  105.03  8479.4  103.08    9490  108.09
  9589.2  108.31  9986.1  109.35 10026.1  110.27 10085.4  109.33 10817.2  109.71
#Mann= 13 ,-1 , 0
  -545.7     .05       0  1669.4     .07       0  1773.5     .05       0
  5295.6     .05       0    5301     .05       0  5629.6     .07       0
  5692.6     .05       0  7306.8    .035       0    7406     .05       0
    9490    .035       0  9589.2     .05       0  9986.1    .035       0
 10085.4     .05       0
Bank Sta=5295.6,5301
XS Rating Curve= 0 ,0
Exp/Cntr=0.3,0.1

Type RM Length L Ch R = 1 ,3505    ,2545,2545,2545
BEGIN DESCRIPTION:
Mapping XS cdd0eca4
END DESCRIPTION:
XS GIS Cut Line= 5
      2569721.99     13420340.95      2570633.46     13416721.13
      2569973.73     13414328.13      2570017.14     13413058.59
      2568499.01     13412386.28
#Sta/Elev= 30
 -1618.1  102.12 -1303.2  101.89  -974.4   99.68  -446.7   98.18  -426.1   99.21
  -405.4   98.12   137.7   97.93   878.6   97.58  1352.6   96.96  1378.8   96.94
  2784.9   97.36  3085.8      96  3801.5   95.35  3977.8   96.21  4019.3   95.18
    4199   95.56  4340.9   94.41  4346.9   95.23  5107.1   94.66  5126.8   93.98
  5127.3   93.48    5134   93.98  5160.5   94.39  5440.8   94.77    5639   94.84
  6015.9    95.8  6198.2   96.14  7156.9    97.6  7268.4   97.88  7527.6   97.62
#Mann= 15 ,-1 , 0
 -1618.1     .05       0   137.7     .07       0   878.6     .05       0
  1352.6     .07       0  1378.8     .05       0  5107.1     .07       0
  5126.8     .05       0    5134     .07       0  5160.5     .05       0
  5440.8     .07       0    5639     .05       0  6015.9     .07       0
  6198.2     .05       0  7156.9     .07       0  7268.4     .05       0
Bank Sta=5126.8,5134
XS Rating Curve= 0 ,0
Exp/Cntr=0.3,0.1

Type RM Length L Ch R = 1 ,960     ,0,0,0
BEGIN DESCRIPTION:
TRIB 14 TO KUY CREEK 1.0
END DESCRIPTION:
XS GIS Cut Line= 4
      2570822.28     13416068.54      2572115.66     13414089.41
      2571916.01     13412917.53      2569780.62     13411676.23
#Sta/Elev= 30
  1933.8   96.85  3288.1   94.72  3318.3   93.52  3562.7   93.11  3665.2   94.14
  3686.3   93.03    3991   92.38  4099.6   93.33  4250.4    91.9  4586.6   92.29
  4862.2   90.48  4862.7   89.98  4870.9   90.48  4927.7   91.69  5129.6   90.94
    5317   92.66  5503.6   92.11  5621.1   93.94  5658.4   92.57  5808.4   92.77
  6016.7   92.63  6089.5    94.4  6147.3   93.11  6418.1   94.64  6498.4   93.76
  7073.9   94.76  7326.2   95.35  7481.4   95.38  7893.2   95.98  7956.8   96.33
#Mann= 10 ,-1 , 0
  1933.8     .05       0  4862.2     .05       0  4870.9     .05       0
  4927.7     .07       0  5129.6     .05       0  5808.4     .07       0
  7073.9     .05       0  7326.2     .07       0  7481.4     .05       0
  7893.2     .07       0
Bank Sta=4862.2,4870.9
XS Rating Curve= 0 ,0
Exp/Cntr=0.3,0.1

Chan Stop Cuts=-1
Use User Specified Reach Order=0
Composite Channel Slope=5