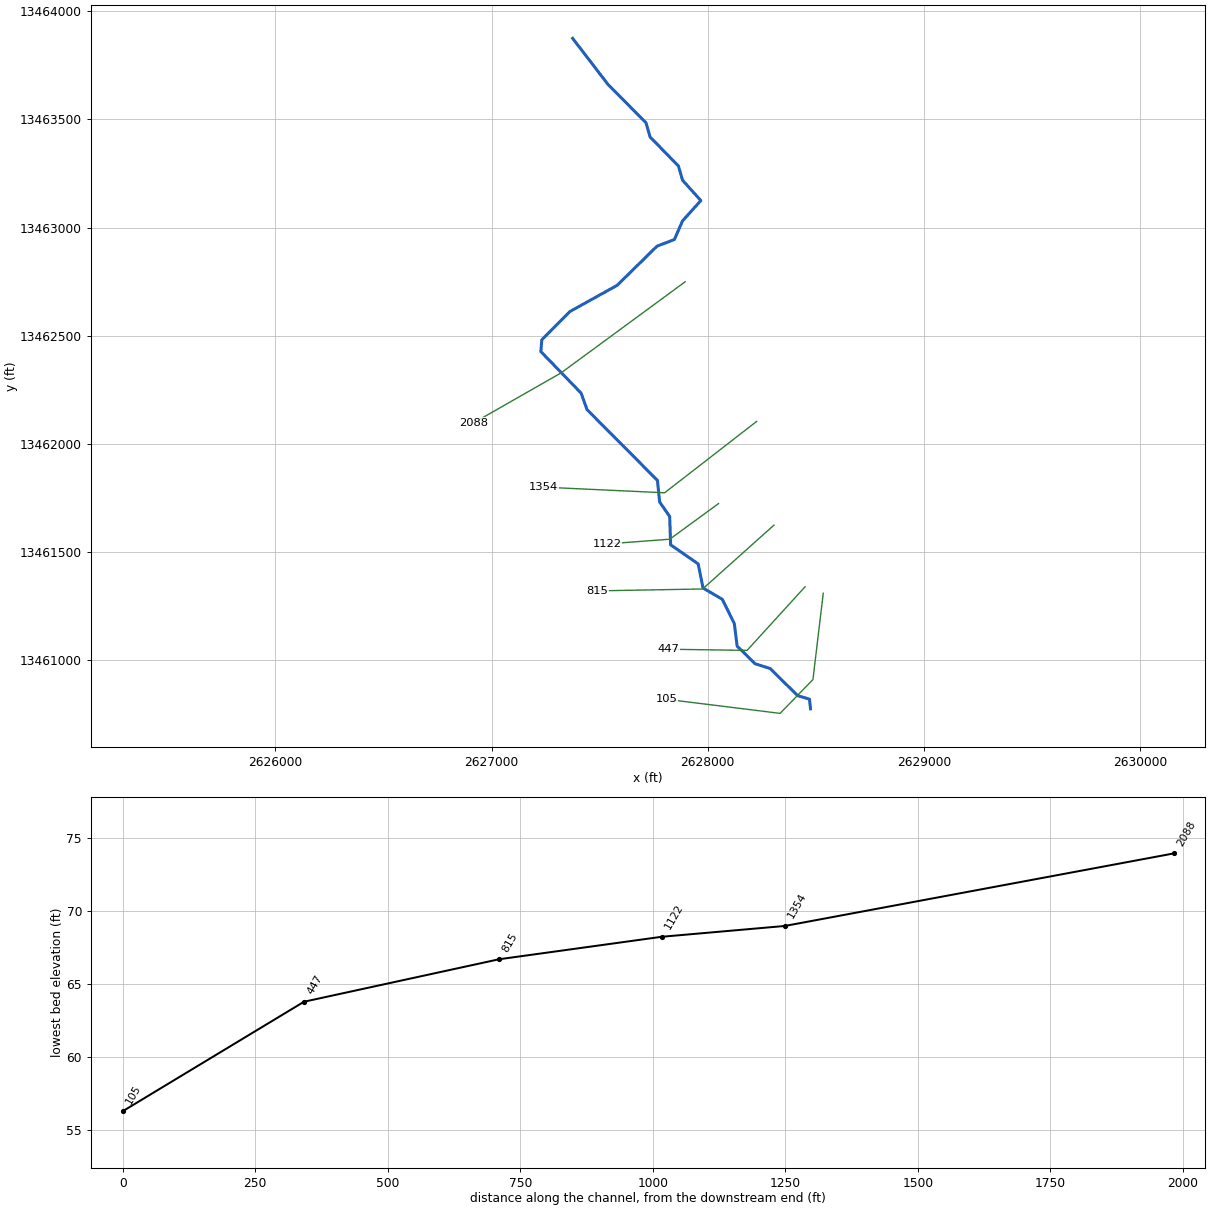
--- TRIB 2 TO CRESCENT VALLEY CREEK.prj (project) ---

Proj Title=TRIB 2 TO CRESCENT VALLEY CREEK Base Level Engineering
Current Plan=p01
Default Exp/Contr=0.3,0.1
English Units
Geom File=g01
Flow File=f01
Plan File=p01
Y Axis Title=Elevation
X Axis Title(PF)=Main Channel Distance
X Axis Title(XS)=Station
BEGIN DESCRIPTION:
TRIB 2 TO CRESCENT VALLEY CREEK
END DESCRIPTION:
DSS Export Rating Curves= 0
DSS Export Rating Curve Sorted= 0
DSS Export Volume Flow Curves= 0
DXF OffsetX= 0
DXF OffsetY= 0
DXF ScaleX= 1
DXF ScaleY= 10

--- TRIB 2 TO CRESCENT VALLEY CREEK.p01 (plan) ---

Plan Title=Multiple Run
Program Version=4.10
Short Identifier=Multiple
Geom File=g01
Flow File=f01
Subcritical Flow
K Sum by GR= 0
Std Step Tol= 0.01
Critical Tol= 0.01
Num of Std Step Trials= 20
Max Error Tol= 0.3
Flow Tol Ratio= 0.001
Split Flow NTrial= 30
Split Flow Tol= 0.02
Split Flow Ratio= 0.02
Log Output Level= 0
Friction Slope Method= 1
Unsteady Friction Slope Method= 2
Unsteady Bridges Friction Slope Method= 1
Parabolic Critical Depth
Global Vel Dist= 1 , 1 , 1
Global Log Level= 0
CheckData=True
Encroach Param=-1 ,0,0, 0
BEGIN DESCRIPTION:
Multiple Run
END DESCRIPTION:
Computation Interval=1HOUR
Output Interval=1HOUR
Run HTab= 0
Run UNet= 0
Run PostProcess= 0
Run WQNet= 0
UNET Theta= 1
UNET Theta Warmup= 1
UNET ZTol= 0.02
UNET ZSATol= 0.05
UNET MxIter= 20
UNET MaxInSteps= 0
UNET DtIC= 0
UNET DtMin= 0
UNET MaxCRTS= 20
UNET WFStab= 2
UNET SFStab= 1
UNET WFX= 1
UNET SFX= 1
UNET DSS MLevel= 4
UNET DZMax Abort= 100
UNET Convert EG Bridges= 0
UNET Use Existing IB Tables=-1
UNET Froude Reduction=False
UNET Froude Limit= 1
UNET Froude Power= 10
UNET Time Slicing=0,0, 5
UNET Junction Losses=0
Instantaneous Interval=1HOUR
Write IC File= 0
Write IC File at Sim End=0
Echo Input=False
Echo Parameters=False
Echo Output=False
Write Detailed= 0
WQ AD Non Conservative
WQ ULTIMATE=-1
WQ Max Comp Step=1HOUR
WQ Output Interval=15MIN
WQ Output Selected Increments= 0
WQ Output face flow=0
WQ Output face velocity=0
WQ Output face area=0
WQ Output face dispersion=0
WQ Output cell volume=0
WQ Output cell surface area=0
WQ Output cell continuity=0
WQ Output cumulative cell continuity=0
WQ Output face conc=0
WQ Output face dconc_dx=0
WQ Output face courant=0
WQ Output face peclet=0
WQ Output face adv mass=0
WQ Output face disp mass=0
WQ Output cell mass=0
WQ Output cell source sink temp=0
WQ Output cell source sink nsm=0
WQ Output MaxMinRange=-1
WQ Daily Max Min Mean=-1
WQ Daily Range=0
WQ Daily Time=0
WQ Create Restart=0
WQ Fixed Restart=0
WQ System Summary=0
WQ Use Fixed Temperature=0
Sorting and Armoring Iterations= 10
XS Update Threshold= 0.02
Hydraulics Update Threshold= 0.02
Energy Slope Method= 1
Volume Change Method= 0
XS Weighting Method= 0
Number of US Weighted Cross Sections= 1
Number of DS Weighted Cross Sections= 1
Upstream XS Weight=0.25
Main XS Weight=0.5
Downstream XS Weight=0.25
Number of DS XS's Weighted with US Boundary= 1
Upstream Boundary Weight= 1
Weight of XSs Associated with US Boundary= 0
Number of US XS's Weighted with DS Boundary= 1
Downstream Boundary Weight= 0.5
Weight of XSs Associated with DS Boundary= 0.5
Sediment Output Level= 4
Mass or Volume Output= 0
Output Increment Type= 1
Profile and TS Output Increment= 10
XS Output Flag= 0
XS Output Increment= 10
Disregard all LS=0
Disregard all Conn=0
Disregard all Breaches=0
Disregard all Pumps=0

--- TRIB 2 TO CRESCENT VALLEY CREEK.f01 (steady flow) ---

Flow Title=Multiple
Number of Profiles=7
Profile Names=10-year,25-year,50-year,1pct_min,100-year,1pct_plu,500-year
River Rch & RM= TRIB 2 TO CRESCE,Reach-1,2088
     570     871    1128     706    1408    2810    2169
Boundary for River Rch & Prof#=TRIB 2 TO CRESCE,Reach-1,1
Up Type=0
Dn Type=3
Dn Slope=0.005
Boundary for River Rch & Prof#=TRIB 2 TO CRESCE,Reach-1,2
Up Type=0
Dn Type=3
Dn Slope=0.005
Boundary for River Rch & Prof#=TRIB 2 TO CRESCE,Reach-1,3
Up Type=0
Dn Type=3
Dn Slope=0.005
Boundary for River Rch & Prof#=TRIB 2 TO CRESCE,Reach-1,4
Up Type=0
Dn Type=3
Dn Slope=0.005
Boundary for River Rch & Prof#=TRIB 2 TO CRESCE,Reach-1,5
Up Type=0
Dn Type=3
Dn Slope=0.005
Boundary for River Rch & Prof#=TRIB 2 TO CRESCE,Reach-1,6
Up Type=0
Dn Type=3
Dn Slope=0.005
Boundary for River Rch & Prof#=TRIB 2 TO CRESCE,Reach-1,7
Up Type=0
Dn Type=3
Dn Slope=0.005

--- TRIB 2 TO CRESCENT VALLEY CREEK.g01 (geometry) ---

Geom Title=Existing Conditions
Program Version=4.10

River Reach=TRIB 2 TO CRESCE,Reach-1
Reach XY= 30
        2627375.       13463875.      2627538.63     13463661.79
      2627714.22     13463484.68      2627733.16     13463418.95
      2627864.22     13463284.68       2627883.2     13463218.95
      2627967.91       13463125.      2627883.21     13463031.03
      2627845.47     13462944.63      2627765.34     13462914.21
      2627581.05     13462733.16      2627361.79     13462611.37
      2627232.46     13462481.05       2627228.1     13462426.65
      2627414.22     13462234.68      2627441.65     13462158.33
      2627767.14     13461831.17      2627777.36     13461730.98
      2627823.76     13461664.48      2627828.08     13461533.31
      2627955.38     13461445.17      2627978.19     13461333.35
      2628066.93     13461281.32      2628122.67     13461169.03
      2628135.51     13461065.19      2628218.93     13460983.15
      2628288.21     13460961.37      2628415.46     13460835.72
      2628470.08     13460819.67        2628475.       13460775.

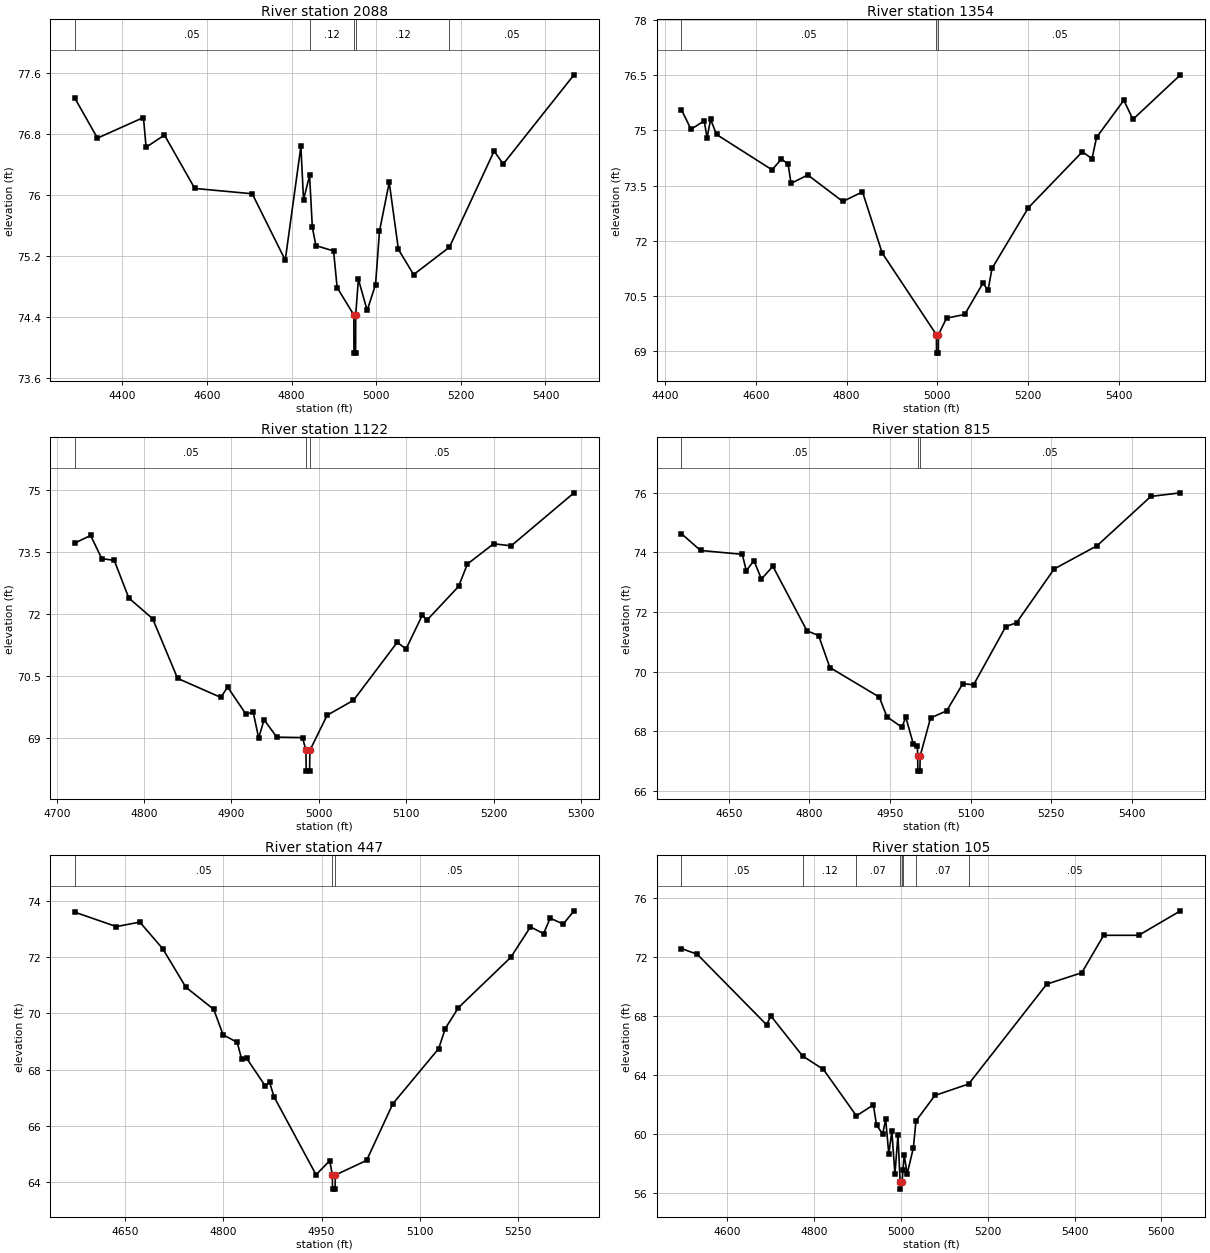
Type RM Length L Ch R = 1 ,2088    ,734,734,734
BEGIN DESCRIPTION:
Mapping XS ff712c2d
END DESCRIPTION:
XS GIS Cut Line= 3
       2627895.4     13462749.47      2627321.76     13462328.21
      2626915.87     13462096.45
#Sta/Elev= 30
  4288.3   77.26  4341.4   76.74  4450.1   77.01  4456.3   76.62  4499.7   76.78
  4571.3   76.08  4707.1   76.01  4785.1   75.14  4822.1   76.63  4828.3   75.93
  4842.6   76.25  4849.1   75.57  4857.6   75.33  4899.3   75.26  4907.7   74.78
  4947.2   74.42  4947.5   73.92  4951.3   73.92  4951.6   74.42  4957.9   74.89
  4978.7   74.48  4998.5   74.82  5007.8   75.52  5030.8   76.16  5052.5   75.28
  5088.4   74.95  5173.1   75.31  5278.6   76.57  5300.2    76.4  5467.4   77.57
#Mann= 5 ,-1 , 0
  4288.3     .05       0  4842.6     .12       0  4947.2     .05       0
  4951.6     .12       0  5173.1     .05       0
Bank Sta=4947.2,4951.6
XS Rating Curve= 0 ,0
Exp/Cntr=0.3,0.1

Type RM Length L Ch R = 1 ,1354    ,232,232,232
BEGIN DESCRIPTION:
Mapping XS 080a831e
END DESCRIPTION:
XS GIS Cut Line= 3
      2628225.71     13462103.68      2627800.36     13461773.82
      2627240.43     13461799.86
#Sta/Elev= 30
  4436.4   75.56  4457.5   75.03  4486.5   75.26  4492.8    74.8  4500.6    75.3
  4513.6   74.89  4635.8   73.93  4656.6   74.22  4671.1   74.09  4677.7   73.56
  4714.6   73.79  4791.6   73.07    4835   73.33  4878.4   71.67  4997.8   69.45
  4998.1   68.95    5002   68.95  5002.3   69.45  5020.1    69.9  5060.1      70
  5100.2   70.85  5111.5   70.66  5120.2   71.25  5200.3    72.9  5319.2   74.42
  5340.4   74.23  5350.4   74.81  5410.5   75.82  5430.5    75.3  5535.2   76.51
#Mann= 3 ,-1 , 0
  4436.4     .05       0  4997.8     .05       0  5002.3     .05       0
Bank Sta=4997.8,5002.3
XS Rating Curve= 0 ,0
Exp/Cntr=0.3,0.1

Type RM Length L Ch R = 1 ,1122    ,307,307,307
BEGIN DESCRIPTION:
Mapping XS f8a3c9b6
END DESCRIPTION:
XS GIS Cut Line= 3
      2628049.75     13461723.97      2627824.08     13461559.06
       2627533.3     13461537.36
#Sta/Elev= 30
  4720.9   73.72  4738.8    73.9  4751.6   73.34  4765.8    73.3  4782.5   72.39
  4809.8   71.89  4838.3   70.45  4887.8   69.99  4895.6   70.24  4916.4   69.59
  4924.9   69.63  4931.1   69.01  4937.3   69.45  4951.9   69.03  4981.3   69.02
  4985.2   68.71  4985.5   68.21  4989.4   68.21  4989.7   68.71  5009.5   69.56
  5039.6   69.92  5089.7   71.32  5099.8   71.16  5118.5   71.98  5123.5   71.85
  5159.9   72.67    5170   73.21    5200    73.7  5220.1   73.65    5292   74.93
#Mann= 3 ,-1 , 0
  4720.9     .05       0  4985.2     .05       0  4989.7     .05       0
Bank Sta=4985.2,4989.7
XS Rating Curve= 0 ,0
Exp/Cntr=0.3,0.1

Type RM Length L Ch R = 1 ,815     ,368,368,368
BEGIN DESCRIPTION:
Mapping XS 0efc13e4
END DESCRIPTION:
XS GIS Cut Line= 3
      2628305.87     13461624.18      2627975.99     13461329.02
      2627489.92     13461320.34
#Sta/Elev= 30
  4561.7   74.62  4597.2   74.06  4674.9   73.93  4682.4   73.38  4696.6   73.72
  4710.5    73.1  4731.8   73.53  4795.3   71.37    4817   71.21  4837.9   70.14
  4929.9   69.15  4944.1   68.49  4972.1   68.14  4979.2   68.48  4993.4   67.57
  5000.9   67.51  5001.3   67.17  5001.7   66.67  5005.6   66.67  5005.9   67.17
  5025.3   68.45  5055.4   68.69  5085.4    69.6  5105.4   69.56  5165.4   71.51
  5185.4   71.64  5255.4   73.44  5335.4   74.22  5435.4   75.87  5490.5   75.99
#Mann= 3 ,-1 , 0
  4561.7     .05       0  5001.3     .05       0  5005.9     .05       0
Bank Sta=5001.3,5005.9
XS Rating Curve= 0 ,0
Exp/Cntr=0.3,0.1

Type RM Length L Ch R = 1 ,447     ,342,342,342
BEGIN DESCRIPTION:
Mapping XS d0f347b5
END DESCRIPTION:
XS GIS Cut Line= 3
      2628449.92     13461339.41      2628181.72     13461045.17
      2627818.59     13461050.36
#Sta/Elev= 30
  4573.8   73.59  4636.9   73.08  4672.7   73.24  4707.8   72.29  4742.9   70.93
  4785.5   70.14  4799.7   69.24  4821.3   68.97  4828.1   68.37  4835.5   68.41
  4863.9   67.43  4870.6   67.56  4877.4   67.04  4941.6   64.27  4962.5   64.77
  4966.4   64.26  4966.7   63.76  4970.6   63.76    4971   64.26  5018.7   64.78
  5058.7   66.79  5128.7   68.75  5138.7   69.46  5158.7    70.2  5238.7   71.99
  5268.7   73.07  5288.7   72.83  5298.7   73.38  5318.7   73.17  5335.1   73.64
#Mann= 3 ,-1 , 0
  4573.8     .05       0  4966.4     .05       0    4971     .05       0
Bank Sta=4966.4,4971
XS Rating Curve= 0 ,0
Exp/Cntr=0.3,0.1

Type RM Length L Ch R = 1 ,105     ,0,0,0
BEGIN DESCRIPTION:
TRIB 2 TO CRESCENT VALLEY CREEK 1.0
END DESCRIPTION:
XS GIS Cut Line= 4
      2628533.86     13461309.37      2628486.12      13460910.1
      2628334.21     13460753.85      2627809.56     13460818.89
#Sta/Elev= 30
  4495.2   72.57  4531.3   72.19    4691   67.41  4701.1      68    4774   65.29
  4821.9   64.38  4897.9   61.23    4937   61.97  4944.2    60.6  4958.4      60
  4965.3   60.99  4972.5   58.64  4979.5    60.2  4986.6   57.27  4993.6   59.93
  4998.5   56.76  4998.8   56.26  5003.1   56.76  5005.1   57.53  5007.8   58.57
  5014.9    57.3  5029.1   59.07    5035   60.88  5078.5   62.61  5156.4   63.39
  5336.1   70.16  5416.7   70.93  5467.1   73.47  5547.7   73.47  5643.9   75.13
#Mann= 8 ,-1 , 0
  4495.2     .05       0    4774     .12       0  4897.9     .07       0
  4998.5     .05       0  5003.1     .07       0  5005.1     .12       0
    5035     .07       0  5156.4     .05       0
Bank Sta=4998.5,5003.1
XS Rating Curve= 0 ,0
Exp/Cntr=0.3,0.1

Chan Stop Cuts=-1
Use User Specified Reach Order=0
Composite Channel Slope=5