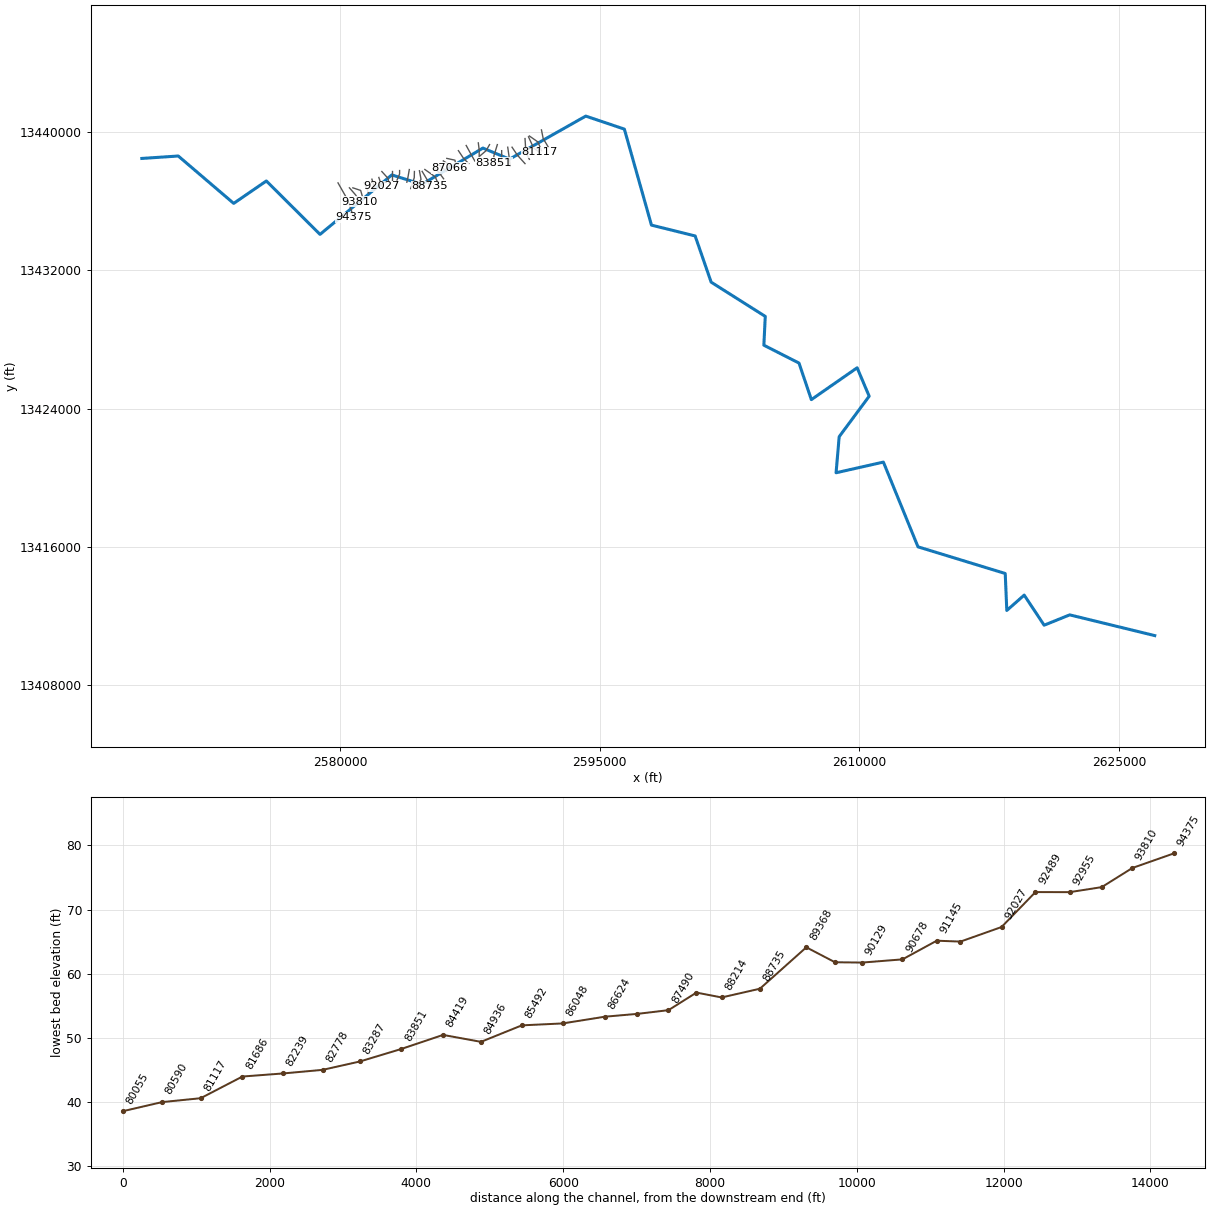
--- TRIB 2 TO GUADALUPE RIVER.prj (project) ---

Proj Title=TRIB 2 TO GUADALUPE RIVER Base Level Engineering
Current Plan=p01
Default Exp/Contr=0.3,0.1
English Units
Geom File=g01
Flow File=f01
Plan File=p01
Y Axis Title=Elevation
X Axis Title(PF)=Main Channel Distance
X Axis Title(XS)=Station
BEGIN DESCRIPTION:
TRIB 2 TO GUADALUPE RIVER
END DESCRIPTION:
DSS Export Rating Curves= 0
DSS Export Rating Curve Sorted= 0
DSS Export Volume Flow Curves= 0
DXF OffsetX= 0
DXF OffsetY= 0
DXF ScaleX= 1
DXF ScaleY= 10

--- TRIB 2 TO GUADALUPE RIVER.p01 (plan) ---

Plan Title=Multiple Run
Short Identifier=Multiple
Geom File=g01
Flow File=f01
Subcritical Flow
K Sum by GR= 0
Std Step Tol= 0.01
Critical Tol= 0.01
Num of Std Step Trials= 20
Max Error Tol= 0.3
Flow Tol Ratio= 0.001
Split Flow NTrial= 30
Split Flow Tol= 0.02
Split Flow Ratio= 0.02
Log Output Level= 0
Friction Slope Method= 1
Unsteady Friction Slope Method= 2
Unsteady Bridges Friction Slope Method= 1
Parabolic Critical Depth
Global Vel Dist=  1 , 1 , 1
Global Log Level= 0
CheckData=True
Encroach Param= -1, 0, 0, 0
BEGIN DESCRIPTION:
Multiple Run
END DESCRIPTION:

--- TRIB 2 TO GUADALUPE RIVER.f01 (steady flow) ---

Flow Title=Multiple
Program Version=4.10
Number of Profiles= 7
Profile Names=10-year,25-year,50-year,1pct_min,100-year,1pct_plu,500-year
River Rch & RM=TRIB 2 TO GUADAL,Reach-1         ,94375
    1761    2827    3778    2427    4843    9664    7875
River Rch & RM=TRIB 2 TO GUADAL,Reach-1         ,93392
    1976    3205    4314    2792    5570   11114    9189
River Rch & RM=TRIB 2 TO GUADAL,Reach-1         ,90129
    2105    3429    4630    3006    5998   11967    9958
River Rch & RM=TRIB 2 TO GUADAL,Reach-1         ,86048
    2656    4367    5934    3876    7734   15432   12995
River Rch & RM=TRIB 2 TO GUADAL,Reach-1         ,78951
    2794    4604    6267    4100    8181   16324   13790
River Rch & RM=TRIB 2 TO GUADAL,Reach-1         ,76788
    2860    4718    6426    4207    8394   16749   14166
River Rch & RM=TRIB 2 TO GUADAL,Reach-1         ,73674
    3029    5007    6829    4477    8932   17822   15113
River Rch & RM=TRIB 2 TO GUADAL,Reach-1         ,69753
    3266    5403    7373    4834    9644   19243   16320
Boundary for River Rch & Prof#=TRIB 2 TO GUADAL,Reach-1         , 1
Up Type= 0
Dn Type= 3
Dn Slope=0.0007
Boundary for River Rch & Prof#=TRIB 2 TO GUADAL,Reach-1         , 2
Up Type= 0
Dn Type= 3
Dn Slope=0.0007
Boundary for River Rch & Prof#=TRIB 2 TO GUADAL,Reach-1         , 3
Up Type= 0
Dn Type= 3
Dn Slope=0.0007
Boundary for River Rch & Prof#=TRIB 2 TO GUADAL,Reach-1         , 4
Up Type= 0
Dn Type= 3
Dn Slope=0.0007
Boundary for River Rch & Prof#=TRIB 2 TO GUADAL,Reach-1         , 5
Up Type= 0
Dn Type= 3
Dn Slope=0.0007
Boundary for River Rch & Prof#=TRIB 2 TO GUADAL,Reach-1         , 6
Up Type= 0
Dn Type= 3
Dn Slope=0.0007
Boundary for River Rch & Prof#=TRIB 2 TO GUADAL,Reach-1         , 7
Up Type= 0
Dn Type= 3
Dn Slope=0.0007
DSS Import GetInterval= 0
DSS Import GetPeak= 0
DSS Import FillOption= 0

--- TRIB 2 TO GUADALUPE RIVER.g01 (geometry) ---

Geom Title=Existing Conditions
Program Version=4.10

River Reach=TRIB 2 TO GUADAL,Reach-1
Reach XY= 30
        2568525.       13438475.      2570631.67     13438616.05
      2573835.64     13435875.55      2575723.64     13437171.73
      2578825.09     13434082.28      2582976.46     13437521.46
      2584718.87     13436976.78      2588240.28     13439074.64
      2589778.41     13438432.81      2594185.29     13440924.03
      2596416.72     13440171.95      2597983.14     13434618.94
      2600508.54     13433991.75      2601433.14     13431318.94
      2604561.37     13429338.21      2604480.34     13427672.26
      2606511.69     13426638.34        2607225.       13424525.
      2609871.85     13426366.69       2610567.5     13424721.87
      2608833.83       13422382.      2608654.52     13420294.26
      2611388.65     13420911.81      2613388.23     13416011.27
      2618431.19     13414467.19      2618522.25     13412330.29
      2619528.33      13413217.4      2620680.89     13411476.96
      2622159.61     13412074.92        2627075.       13410875.

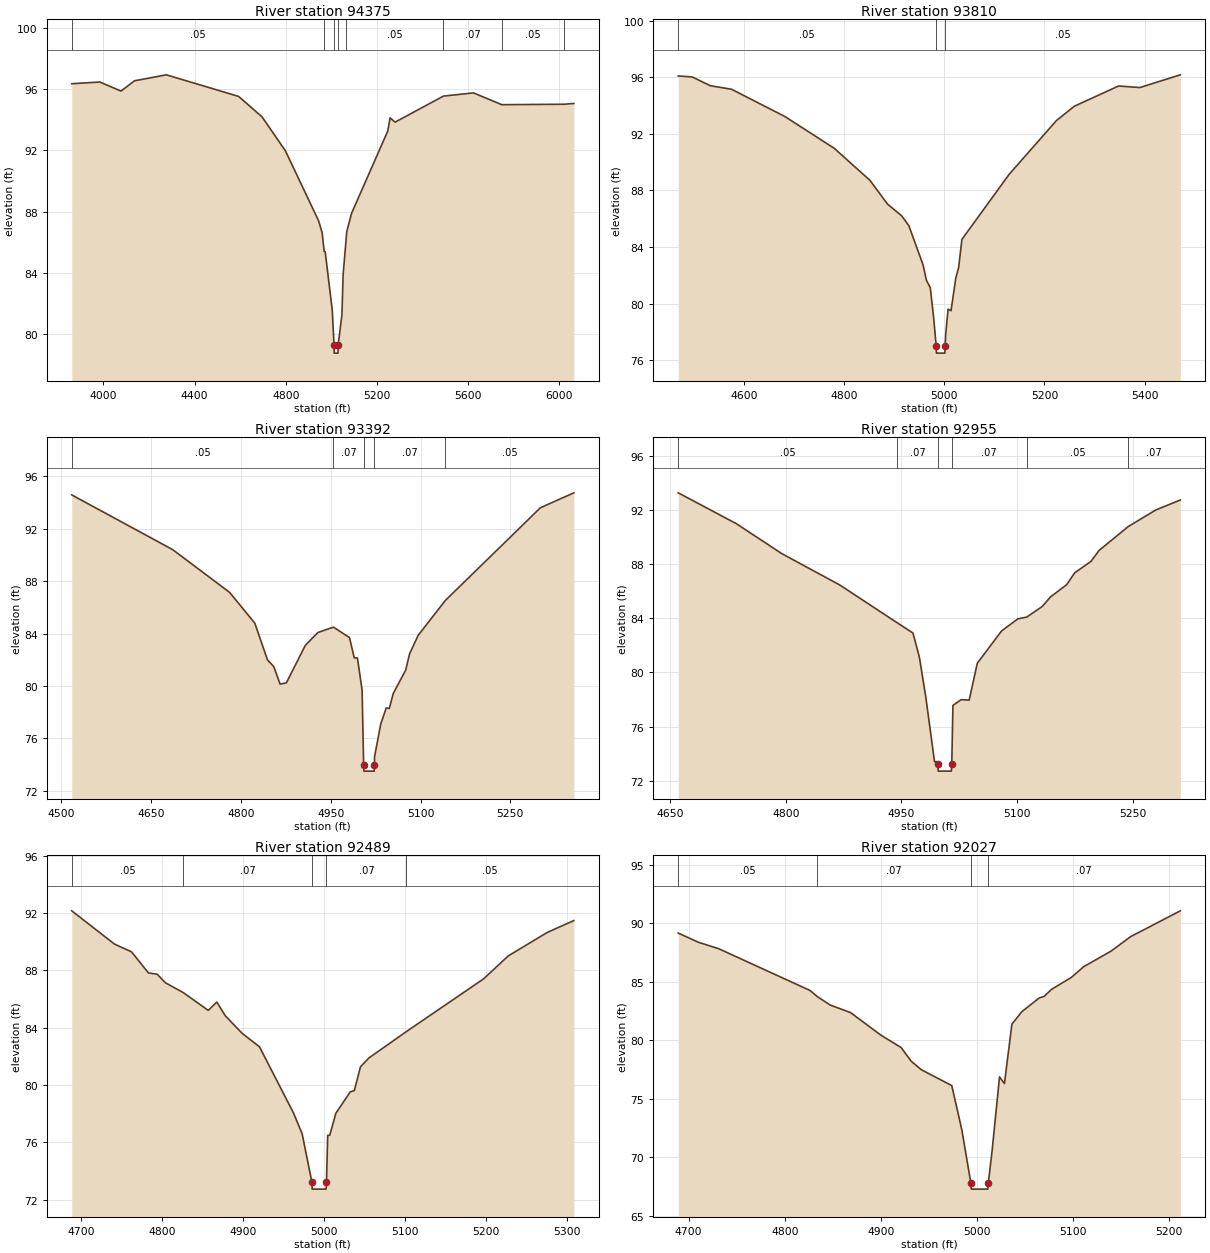
Type RM Length L Ch R = 1 ,94375   ,565,565,565
BEGIN DESCRIPTION:
Mapping XS 3917173d
END DESCRIPTION:
XS GIS Cut Line= 3
      2579865.49     13437061.78      2580412.38     13436098.22
      2580776.97     13435065.22
#Sta/Elev= 30
  3860.9   96.35  3983.7   96.46    4077   95.87  4136.2   96.54  4276.1   96.93
  4593.1   95.52  4695.7   94.19  4798.1   91.98  4943.8   87.41  4959.7   86.62
  4968.6    85.4  4973.2   85.37  5004.1   81.56    5012   79.26  5012.5   78.76
  5029.3   78.76  5029.8   79.26  5046.5   81.26  5051.8   83.89    5064   86.04
  5067.7   86.69  5088.9   87.89    5248   93.27  5257.7   94.12  5279.8   93.84
  5491.9   95.54  5623.6   95.75  5748.4   94.98  6022.4   95.01  6064.3   95.06
#Mann= 8 ,-1 , 0
  3860.9     .05       0  4968.6     .07       0    5012     .05       0
  5029.8     .07       0    5064     .05       0  5491.9     .07       0
  5748.4     .05       0  6022.4     .07       0
Bank Sta=5012,5029.8
XS Rating Curve= 0 ,0
Exp/Cntr=0.3,0.1

Type RM Length L Ch R = 1 ,93810   ,418,418,418
BEGIN DESCRIPTION:
TRIB 2 TO GUADALUPE RIVER 85.0
END DESCRIPTION:
XS GIS Cut Line= 3
      2580524.97     13436775.04        2580875.       13436375.
      2581125.02     13435974.96
#Sta/Elev= 30
  4468.2    96.1  4496.2   96.03  4532.3   95.41  4574.6   95.16  4680.9   93.24
    4780   90.98  4851.2   88.72  4886.3   87.04  4914.8    86.2    4929   85.51
  4957.5   82.73  4964.2   81.64  4971.8   81.13  4978.4   79.06  4983.7   76.99
  4984.2   76.49    5001   76.49  5001.5   76.99  5002.7   77.84  5007.4    79.6
  5013.3   79.49  5022.8   81.79  5028.6   82.56  5035.1   84.54  5129.5   89.14
  5223.8   92.94  5259.8   93.96  5348.2   95.39  5390.7   95.28  5471.5   96.18
#Mann= 3 ,-1 , 0
  4468.2     .05       0  4983.7     .05       0  5001.5     .05       0
Bank Sta=4983.7,5001.5
XS Rating Curve= 0 ,0
Exp/Cntr=0.3,0.1

Type RM Length L Ch R = 1 ,93392   ,437,437,437
BEGIN DESCRIPTION:
TRIB 2 TO GUADALUPE RIVER 84.0
END DESCRIPTION:
XS GIS Cut Line= 3
      2580724.97     13436775.01        2581175.       13436625.
      2581275.01     13436274.98
#Sta/Elev= 30
  4517.6   94.58  4686.3    90.4  4781.2   87.14  4823.3   84.79  4844.4   81.99
  4854.9   81.48  4865.5   80.14    4876   80.24  4907.6    83.1  4928.7   84.08
  4954.6   84.49  4981.4   83.69  4989.3   82.14  4994.6   82.14  5002.4   79.69
    5005      74  5005.5    73.5  5022.6    73.5  5023.1      74  5023.2    74.6
  5033.6    77.1  5042.7   78.32  5047.9   78.29  5054.4   79.42  5075.2   81.21
  5081.7   82.45    5096   83.86  5141.3   86.52  5300.1    93.6    5356   94.74
#Mann= 5 ,-1 , 0
  4517.6     .05       0  4954.6     .07       0    5005     .05       0
  5023.1     .07       0  5141.3     .05       0
Bank Sta=5005,5023.1
XS Rating Curve= 0 ,0
Exp/Cntr=0.3,0.1

Type RM Length L Ch R = 1 ,92955   ,466,466,466
BEGIN DESCRIPTION:
TRIB 2 TO GUADALUPE RIVER 83.0
END DESCRIPTION:
XS GIS Cut Line= 3
        2581375.     13437074.99        2581525.       13436775.
      2581624.99     13436475.03
#Sta/Elev= 30
  4660.3   93.26  4735.8   90.98  4794.5   88.78  4869.9   86.46  4944.2   83.68
    4965   82.91  4973.3   81.12  4981.7   78.15  4992.9   73.42  4995.7   73.42
  4997.2   73.22  4997.7   72.72  5014.8   72.72  5015.3   73.22  5016.8   77.57
  5027.3   77.99  5037.9   77.96  5048.4   80.68    5080   83.07  5101.1   83.96
  5112.6   84.09  5132.7   84.87  5143.3   85.57  5164.4   86.48  5174.9   87.36
    5196    88.2  5206.5   89.01  5244.3   90.77  5280.3      92  5311.9   92.73
#Mann= 6 ,-1 , 0
  4660.3     .05       0  4944.2     .07       0  4997.2     .05       0
  5015.3     .07       0  5112.6     .05       0  5244.3     .07       0
Bank Sta=4997.2,5015.3
XS Rating Curve= 0 ,0
Exp/Cntr=0.3,0.1

Type RM Length L Ch R = 1 ,92489   ,462,462,462
BEGIN DESCRIPTION:
TRIB 2 TO GUADALUPE RIVER 82.0
END DESCRIPTION:
XS GIS Cut Line= 3
      2581825.01     13437274.97        2581925.       13436975.
      2581974.99     13436675.03
#Sta/Elev= 30
  4688.4   92.16  4741.1   89.84  4762.2    89.3  4783.2   87.82  4793.8   87.74
  4804.3   87.13  4826.2   86.45    4857   85.21  4867.6   85.79  4878.1   84.83
  4899.2   83.59  4920.3   82.67  4962.4   78.04    4973    76.6    4985   73.23
  4985.5   72.73  5002.6   72.73  5003.1   73.23  5004.6   76.49  5007.1   76.49
  5014.7   78.03  5032.5   79.52  5037.5   79.61  5045.1   81.27  5055.3   81.88
  5101.8   83.73  5197.2   87.41  5227.6   89.01  5275.8   90.65  5308.7   91.48
#Mann= 5 ,-1 , 0
  4688.4     .05       0  4826.2     .07       0    4985     .05       0
  5003.1     .07       0  5101.8     .05       0
Bank Sta=4985,5003.1
XS Rating Curve= 0 ,0
Exp/Cntr=0.3,0.1

Type RM Length L Ch R = 1 ,92027   ,559,559,559
BEGIN DESCRIPTION:
TRIB 2 TO GUADALUPE RIVER 81.0
END DESCRIPTION:
XS GIS Cut Line= 3
        2582225.       13437375.        2582325.       13437075.
        2582375.     13436874.99
#Sta/Elev= 30
  4689.2   89.16  4710.3   88.37  4731.4   87.82  4826.2   84.26  4834.1   83.72
  4847.3   83.01  4868.4   82.37    4900   80.44  4921.1   79.38  4931.6   78.21
  4942.2   77.48  4973.8   76.13  4984.3   72.34  4993.7   67.78  4994.2   67.28
  5011.3   67.28  5011.8   67.78  5015.7    70.5  5023.5   76.87  5028.6    76.3
  5036.4   81.38  5046.7   82.44  5064.7   83.61  5069.9   83.75  5077.6   84.35
  5098.2   85.37  5111.1   86.29  5139.4   87.61    5160   88.86  5211.6   91.06
#Mann= 4 ,-1 , 0
  4689.2     .05       0  4834.1     .07       0  4993.7     .05       0
  5011.8     .07       0
Bank Sta=4993.7,5011.8
XS Rating Curve= 0 ,0
Exp/Cntr=0.3,0.1

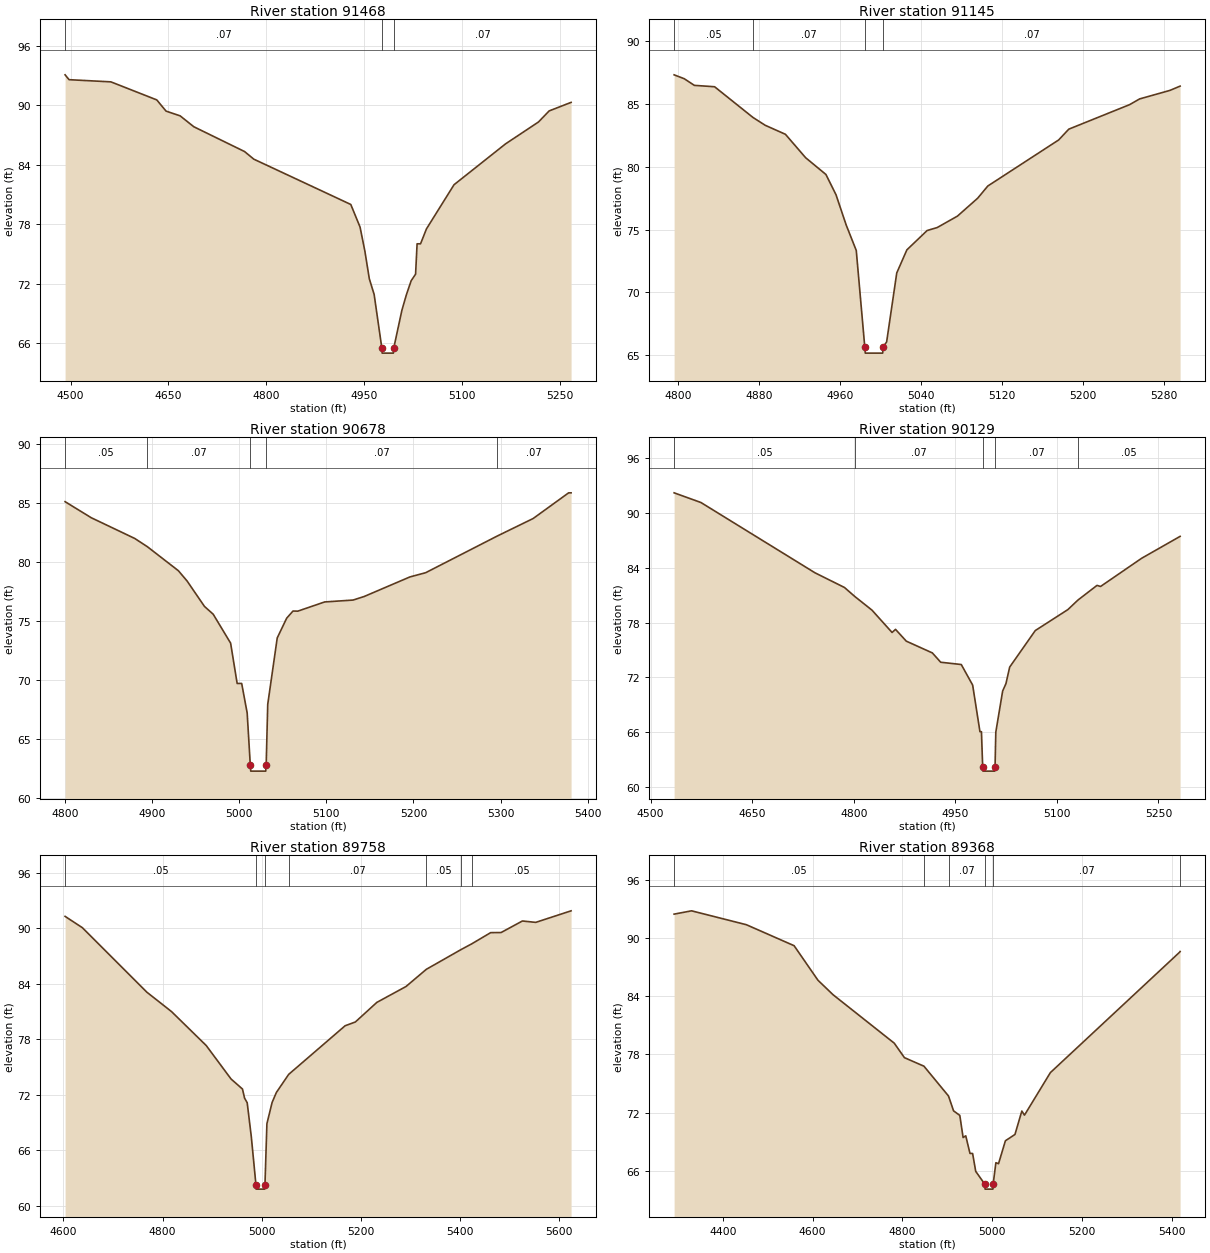
Type RM Length L Ch R = 1 ,91468   ,323,323,323
BEGIN DESCRIPTION:
Mapping XS e2342df0
END DESCRIPTION:
XS GIS Cut Line= 3
      2582398.47     13437717.31      2582763.06     13437318.01
       2582794.3     13437085.41
#Sta/Elev= 30
  4491.7   93.09  4497.8    92.6  4561.9   92.38  4632.2   90.56  4646.4   89.43
    4668   88.95    4689   87.85  4766.7   85.35  4780.9   84.58  4929.5   80.01
  4943.7   77.73  4951.1    75.3  4957.9   72.51  4965.3   70.93  4977.1   65.51
  4977.6   65.01  4994.8   65.01  4995.3   65.51  5007.8   69.33  5014.6   70.88
    5022   72.31  5028.8   72.98  5031.1   76.04  5036.4   76.04  5045.5   77.55
  5087.7      82  5166.6   86.12  5217.1   88.33  5233.5   89.45  5267.1   90.31
#Mann= 3 ,-1 , 0
  4491.7     .07       0  4977.1     .05       0  4995.3     .07       0
Bank Sta=4977.1,4995.3
XS Rating Curve= 0 ,0
Exp/Cntr=0.3,0.1

Type RM Length L Ch R = 1 ,91145   ,467,467,467
BEGIN DESCRIPTION:
TRIB 2 TO GUADALUPE RIVER 79.0
END DESCRIPTION:
XS GIS Cut Line= 3
        2582975.     13437725.05        2582975.       13437525.
        2582975.     13437225.05
#Sta/Elev= 30
  4795.7   87.33  4805.7   87.02  4815.7   86.49  4835.7   86.38  4873.5   83.94
  4885.7   83.31  4905.7   82.59  4925.7   80.72  4945.7   79.39  4955.7   77.77
  4965.7   75.37  4975.7   73.33  4984.1   65.65  4984.6   65.15  5001.8   65.15
  5002.3   65.65  5005.7   66.04  5015.7   71.54  5025.7   73.38  5045.7   74.92
  5055.7   75.16  5075.7   76.07  5095.7    77.5  5105.7   78.47  5175.7   82.14
  5185.7      83  5245.7   84.95  5255.7   85.41  5285.7   86.09  5295.7   86.43
#Mann= 4 ,-1 , 0
  4795.7     .05       0  4873.5     .07       0  4984.1     .05       0
  5002.3     .07       0
Bank Sta=4984.1,5002.3
XS Rating Curve= 0 ,0
Exp/Cntr=0.3,0.1

Type RM Length L Ch R = 1 ,90678   ,549,549,549
BEGIN DESCRIPTION:
TRIB 2 TO GUADALUPE RIVER 78.0
END DESCRIPTION:
XS GIS Cut Line= 3
        2583425.     13437774.98        2583425.       13437575.
      2583274.99     13437224.97
#Sta/Elev= 30
  4800.1   85.08  4830.1   83.72  4880.1   81.96  4894.6   81.26  4930.1   79.23
  4940.1   78.36  4960.1    76.2  4970.1   75.54  4990.1   73.09  4997.6   69.67
  5002.8   69.67  5009.1   67.17  5012.7   62.74  5013.2   62.24  5030.4   62.24
  5030.9   62.74  5032.7    67.9  5043.6   73.53  5054.5   75.21  5061.7   75.81
  5067.2    75.8    5098   76.58  5130.6   76.74  5143.3   77.04  5195.9    78.7
    5214   79.06  5296.2   82.17  5337.3   83.65  5378.1   85.83  5380.9   85.83
#Mann= 5 ,-1 , 0
  4800.1     .05       0  4894.6     .07       0  5012.7     .05       0
  5030.9     .07       0  5296.2     .07       0
Bank Sta=5012.7,5030.9
XS Rating Curve= 0 ,0
Exp/Cntr=0.3,0.1

Type RM Length L Ch R = 1 ,90129   ,371,371,371
BEGIN DESCRIPTION:
Mapping XS 92796b20
END DESCRIPTION:
XS GIS Cut Line= 3
      2583986.16     13437832.81      2583908.02     13437385.72
      2583842.99     13437099.58
#Sta/Elev= 30
  4534.7   92.23  4574.3   91.17  4742.7   83.47  4786.3   81.86  4801.6   80.87
  4826.9   79.38  4856.6   76.93  4861.7   77.27  4877.6   75.98  4916.1   74.69
  4928.4   73.67  4958.8   73.42  4975.6   71.17  4986.4   66.06  4988.6   66.06
  4990.4   62.24  4990.9   61.74  5008.2   61.74  5008.7   62.24  5009.8   66.01
  5019.9   70.51  5024.8   71.33  5030.3   73.14  5068.1   77.14  5116.3   79.44
  5131.1   80.48  5159.3   82.09  5164.5   81.97  5225.2   85.06    5282   87.46
#Mann= 5 ,-1 , 0
  4534.7     .05       0  4801.6     .07       0  4990.4     .05       0
  5008.7     .07       0  5131.1     .05       0
Bank Sta=4990.4,5008.7
XS Rating Curve= 0 ,0
Exp/Cntr=0.3,0.1

Type RM Length L Ch R = 1 ,89758   ,390,390,390
BEGIN DESCRIPTION:
Mapping XS 92534efb
END DESCRIPTION:
XS GIS Cut Line= 3
      2584281.29     13437719.95      2584272.61     13437364.02
      2584068.63     13436730.38
#Sta/Elev= 30
  4603.3   91.31  4638.3   90.08  4768.3   83.11  4818.3      81  4888.3   77.33
  4938.4   73.71  4961.5   72.62  4965.7   71.64    4971   71.14  4979.3   67.47
  4988.6   62.29  4989.1   61.79  5006.4   61.79  5006.9   62.29  5010.8   68.87
  5021.3   71.17  5029.9   72.25  5054.8   74.21  5168.7   79.47  5189.4   79.88
  5232.8      82  5291.7   83.72  5332.7   85.58  5403.6   87.74  5424.5   88.34
  5462.6   89.55  5483.6   89.56  5526.7   90.81  5553.6   90.66    5625   91.91
#Mann= 7 ,-1 , 0
  4603.3     .05       0  4988.6     .05       0  5006.9     .05       0
  5054.8     .07       0  5332.7     .05       0  5403.6     .07       0
  5424.5     .05       0
Bank Sta=4988.6,5006.9
XS Rating Curve= 0 ,0
Exp/Cntr=0.3,0.1

Type RM Length L Ch R = 1 ,89368   ,633,633,633
BEGIN DESCRIPTION:
Mapping XS 19c613bf
END DESCRIPTION:
XS GIS Cut Line= 3
      2584572.09     13437763.28      2584663.23     13437264.19
       2584333.7     13436739.54
#Sta/Elev= 30
  4291.4   92.44  4330.3   92.78  4452.3   91.35  4558.6   89.19  4611.8   85.63
  4645.4   84.14  4781.7   79.15  4804.3   77.66  4847.8   76.78  4902.5   73.71
  4913.8   72.18  4927.7   71.71    4935   69.43  4940.9   69.61  4950.3    67.8
  4956.2   67.79  4963.1   65.95  4983.5   64.62    4984   64.12  5001.4   64.12
  5001.9   64.62    5008   66.84  5013.9   66.74  5029.2    69.1  5050.5   69.75
  5065.8   72.16  5071.7   71.74  5129.4   76.12  5417.2   88.52  5418.3   88.59
#Mann= 6 ,-1 , 0
  4291.4     .05       0  4847.8     .12       0  4902.5     .07       0
  4983.5     .05       0  5001.9     .07       0  5417.2     .05       0
Bank Sta=4983.5,5001.9
XS Rating Curve= 0 ,0
Exp/Cntr=0.3,0.1

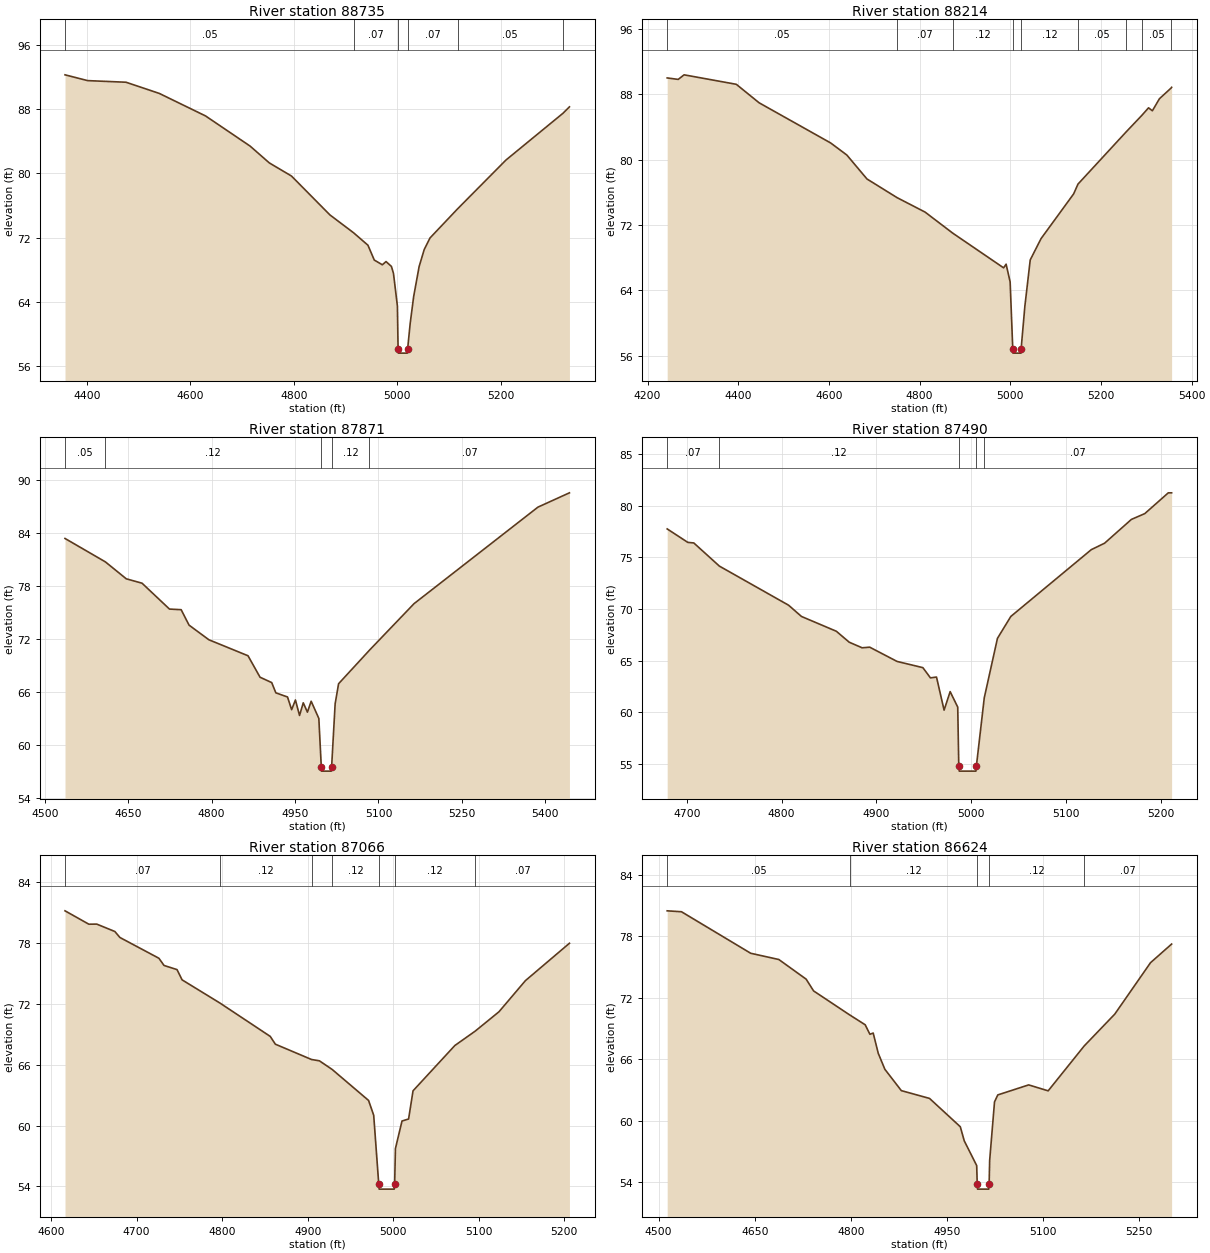
Type RM Length L Ch R = 1 ,88735   ,521,521,521
BEGIN DESCRIPTION:
Mapping XS d128460d
END DESCRIPTION:
XS GIS Cut Line= 3
      2584728.34     13437728.59      2585049.52     13437186.06
      2585153.08      13436858.1
#Sta/Elev= 30
  4358.1   92.25  4401.8   91.53  4475.9   91.33  4540.2   89.94  4629.6   87.14
  4715.7   83.39  4752.8    81.3  4795.6   79.67  4869.8   74.84  4915.7   72.61
  4943.3   71.07  4955.5   69.23  4971.1   68.64  4978.2   69.04  4988.6   68.44
  4992.6   67.57  5000.2    63.5  5001.5   58.16    5002   57.66  5019.4   57.66
  5019.9   58.16  5024.9   61.36  5031.6    64.7  5042.1   68.41    5052   70.54
  5063.1   71.97  5116.4   75.59  5209.9   81.66    5320   87.47  5332.5   88.27
#Mann= 6 ,-1 , 0
  4358.1     .05       0  4915.7     .07       0  5001.5     .05       0
  5019.9     .07       0  5116.4     .05       0    5320     .07       0
Bank Sta=5001.5,5019.9
XS Rating Curve= 0 ,0
Exp/Cntr=0.3,0.1

Type RM Length L Ch R = 1 ,88214   ,343,343,343
BEGIN DESCRIPTION:
Mapping XS fc836512
END DESCRIPTION:
XS GIS Cut Line= 3
      2584884.54     13437837.14      2585487.88     13437411.76
      2585630.57     13437065.85
#Sta/Elev= 30
  4243.4   89.99  4267.7   89.81  4280.7   90.37  4395.8   89.21  4446.3   86.94
  4603.9   82.03  4639.6   80.55    4684   77.62  4750.5   75.33    4812   73.57
  4873.1   70.99  4985.3   66.74  4990.8   67.19  4999.7   65.02  5005.5    56.8
    5006    56.3  5023.4    56.3  5023.9    56.8  5032.2   62.05    5044   67.71
  5067.9   70.32  5139.7   75.79  5149.3   76.99  5254.8   83.34  5289.7   85.38
  5304.9   86.33  5313.4   85.97  5328.9   87.44    5355   88.77  5355.8   88.84
#Mann= 9 ,-1 , 0
  4243.4     .05       0  4750.5     .07       0  4873.1     .12       0
  5005.5     .05       0  5023.9     .12       0  5149.3     .05       0
  5254.8     .07       0  5289.7     .05       0    5355     .07       0
Bank Sta=5005.5,5023.9
XS Rating Curve= 0 ,0
Exp/Cntr=0.3,0.1

Type RM Length L Ch R = 1 ,87871   ,381,381,381
BEGIN DESCRIPTION:
Mapping XS eda4aec3
END DESCRIPTION:
XS GIS Cut Line= 3
      2585392.43     13437997.67      2585709.24     13437650.47
      2585969.23     13437299.49
#Sta/Elev= 30
  4536.5   83.42    4609   80.77  4646.6   78.85    4675   78.35  4724.3   75.42
  4745.3   75.35  4759.5    73.6  4795.2   71.94  4865.5   70.13  4887.1    67.7
  4908.1   67.09  4915.5   65.93  4936.5   65.46  4943.9   64.02  4950.7   65.12
  4958.1   63.37  4964.8    64.8  4972.3   63.74    4979   64.98  4992.8   63.03
  4997.2   57.56  4997.7   57.06  5015.3   57.06  5015.8   57.56  5022.1   64.68
  5028.3   66.96  5083.8   70.76  5163.9   76.03  5386.7   86.97  5443.3   88.59
#Mann= 5 ,-1 , 0
  4536.5     .05       0    4609     .12       0  4997.2     .05       0
  5015.8     .12       0  5083.8     .07       0
Bank Sta=4997.2,5015.8
XS Rating Curve= 0 ,0
Exp/Cntr=0.3,0.1

Type RM Length L Ch R = 1 ,87490   ,424,424,424
BEGIN DESCRIPTION:
TRIB 2 TO GUADALUPE RIVER 71.0
END DESCRIPTION:
XS GIS Cut Line= 3
      2585724.97     13438075.03        2585975.       13437875.
      2586124.98     13437725.02
#Sta/Elev= 30
  4679.3   77.75    4701   76.45  4707.4   76.39  4734.4   74.15  4807.4   70.37
    4821   69.28  4857.8   67.85  4871.4   66.79    4885   66.25    4893   66.31
  4921.9   64.93  4949.1   64.33  4957.1   63.34  4963.5   63.42  4971.5   60.22
  4977.9   62.01  4985.9   60.51    4987   54.82  4987.5   54.32  5005.1   54.32
  5005.6   54.82  5013.9   61.41  5027.8   67.16  5041.9   69.28  5126.8   75.74
  5140.9   76.37  5169.2   78.67  5183.3   79.23  5208.1   81.24  5211.6   81.24
#Mann= 5 ,-1 , 0
  4679.3     .07       0  4734.4     .12       0    4987     .05       0
  5005.6     .12       0  5013.9     .07       0
Bank Sta=4987,5005.6
XS Rating Curve= 0 ,0
Exp/Cntr=0.3,0.1

Type RM Length L Ch R = 1 ,87066   ,442,442,442
BEGIN DESCRIPTION:
TRIB 2 TO GUADALUPE RIVER 70.0
END DESCRIPTION:
XS GIS Cut Line= 3
      2585951.83     13438332.01        2586275.       13438125.
      2586324.99     13437925.04
#Sta/Elev= 30
  4616.2    81.2  4644.1   79.88  4653.3   79.89  4674.5   79.16  4680.4   78.57
    4726   76.52    4732   75.81  4747.2    75.4  4753.1   74.39  4797.4    72.1
  4856.2   68.81  4862.2   68.04  4904.5   66.53  4913.7    66.4  4928.6   65.55
  4971.2   62.49  4977.2   61.03  4983.1   54.24  4983.6   53.74  5001.2   53.74
  5001.7   54.24  5002.6   57.74  5010.3   60.46    5018   60.66  5023.2   63.44
  5072.1   67.91  5095.9   69.33  5123.7   71.24  5154.6   74.31  5206.1      78
#Mann= 7 ,-1 , 0
  4616.2     .07       0  4797.4     .12       0  4904.5     .05       0
  4928.6     .12       0  4983.1     .05       0  5001.7     .12       0
  5095.9     .07       0
Bank Sta=4983.1,5001.7
XS Rating Curve= 0 ,0
Exp/Cntr=0.3,0.1

Type RM Length L Ch R = 1 ,86624   ,576,576,576
BEGIN DESCRIPTION:
TRIB 2 TO GUADALUPE RIVER 69.0
END DESCRIPTION:
XS GIS Cut Line= 3
      2586153.21     13438477.85        2586625.       13438375.
        2586675.       13438075.
#Sta/Elev= 30
  4513.4   80.51  4535.7   80.42  4643.7   76.36  4687.6   75.75  4730.2   73.83
  4741.8   72.68  4798.2   70.33  4822.3   69.37  4829.7   68.44  4834.8   68.56
  4842.7   66.58    4853   65.02  4878.7   62.93  4922.7   62.17  4970.7    59.4
  4976.9   58.02  4996.3    55.6  4997.1    53.8  4997.6    53.3  5015.2    53.3
  5015.7    53.8  5016.5   56.09  5024.1   61.83  5029.2   62.51  5077.4   63.49
  5107.8   62.91  5163.9   67.29  5211.7   70.41  5267.5   75.44  5300.4   77.26
#Mann= 5 ,-1 , 0
  4513.4     .05       0  4798.2     .12       0  4997.1     .05       0
  5015.7     .12       0  5163.9     .07       0
Bank Sta=4997.1,5015.7
XS Rating Curve= 0 ,0
Exp/Cntr=0.3,0.1

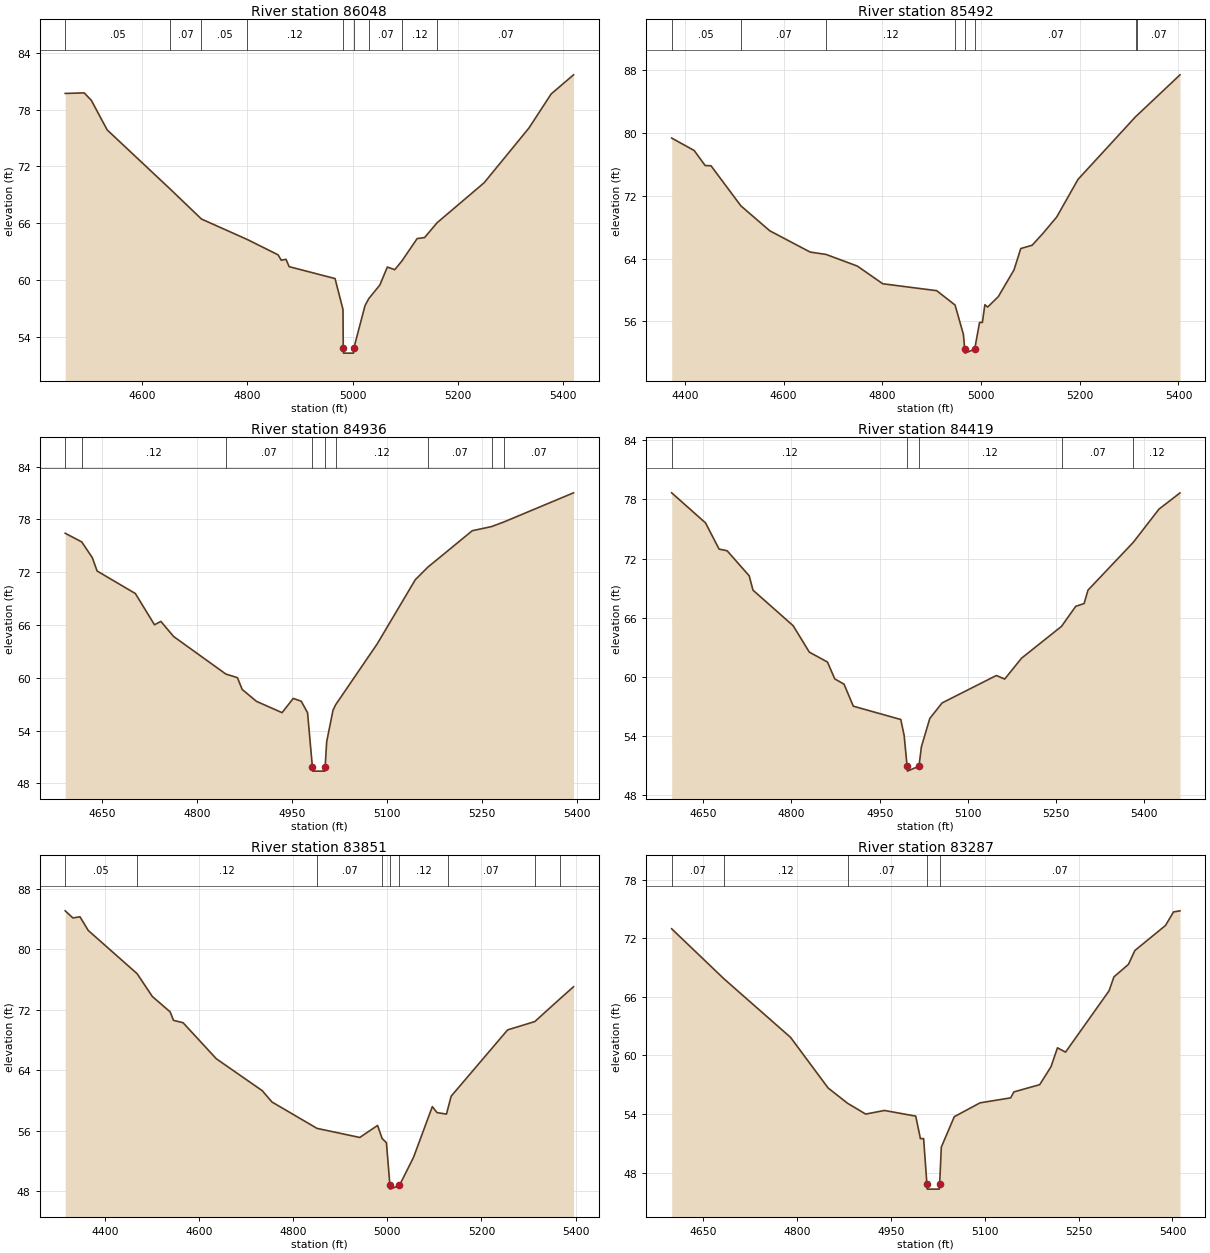
Type RM Length L Ch R = 1 ,86048   ,556,556,556
BEGIN DESCRIPTION:
TRIB 2 TO GUADALUPE RIVER 68.0
END DESCRIPTION:
XS GIS Cut Line= 3
      2586824.98     13438925.04        2587125.       13438475.
      2587424.97     13438175.03
#Sta/Elev= 30
  4454.3   79.73  4490.4   79.79  4503.9      79    4534   75.87  4653.3   69.63
    4713   66.44  4800.2   64.27  4858.5   62.65  4864.5   62.08  4873.5   62.18
  4879.5    61.4  4966.6   60.14  4981.7   56.87  4982.2   52.75  4982.7   52.25
  5001.7   52.25  5002.2   52.75  5023.5   57.28  5030.7   58.02  5051.7   59.46
  5065.9   61.36    5080   61.08  5093.5      62  5122.5   64.37  5136.6   64.48
  5160.4   66.05  5249.7   70.28  5334.6   76.06    5377   79.68  5419.4    81.7
#Mann= 9 ,-1 , 0
  4454.3     .05       0  4653.3     .07       0    4713     .05       0
  4800.2     .12       0  4982.2     .05       0  5002.2     .12       0
  5030.7     .07       0  5093.5     .12       0  5160.4     .07       0
Bank Sta=4982.2,5002.2
XS Rating Curve= 0 ,0
Exp/Cntr=0.3,0.1

Type RM Length L Ch R = 1 ,85492   ,556,556,556
BEGIN DESCRIPTION:
TRIB 2 TO GUADALUPE RIVER 67.0
END DESCRIPTION:
XS GIS Cut Line= 3
      2587275.02     13439224.97        2587575.       13438675.
      2587775.01     13438324.98
#Sta/Elev= 30
  4373.5   79.36    4419   77.78  4441.3   75.86  4453.2   75.83  4513.7   70.72
  4572.3   67.54    4654   64.83  4686.1   64.53  4749.4   63.05  4801.1   60.79
  4910.3   59.91  4947.5   58.08  4964.4   54.34  4967.1   52.45  4967.6   51.95
  4987.2   52.45  4997.1   55.86  5002.8   55.86  5007.9   58.12  5013.6   57.82
  5035.2   59.16  5066.9   62.56  5080.6   65.28  5103.6    65.7  5125.9   67.24
  5153.3   69.29  5196.5   74.09  5314.3   82.16  5315.9   82.24  5403.1   87.42
#Mann= 8 ,-1 , 0
  4373.5     .05       0  4513.7     .07       0  4686.1     .12       0
  4947.5     .07       0  4967.1     .05       0  4987.2     .07       0
  5314.3     .05       0  5315.9     .07       0
Bank Sta=4967.1,4987.2
XS Rating Curve= 0 ,0
Exp/Cntr=0.3,0.1

Type RM Length L Ch R = 1 ,84936   ,517,517,517
BEGIN DESCRIPTION:
TRIB 2 TO GUADALUPE RIVER 66.0
END DESCRIPTION:
XS GIS Cut Line= 3
        2587975.     13439374.98        2588025.       13438975.
        2588025.     13438574.99
#Sta/Elev= 30
  4591.9   76.43    4618   75.45  4634.7   73.66  4642.3   72.14  4702.7   69.58
    4733   66.02    4743   66.41  4763.2   64.69  4845.7   60.42    4864   60.01
  4871.5   58.67  4894.2   57.31  4934.5   56.03  4952.2   57.65  4964.8   57.33
  4974.8   56.02  4982.4   49.88  4982.9   49.38  5002.1   49.38  5002.6   49.88
    5005   52.72    5015   56.31  5019.1   56.92    5085   63.87    5145   71.15
  5164.9   72.58    5235   76.72  5265.4   77.19  5285.1   77.72    5395   81.03
#Mann= 9 ,-1 , 0
  4591.9     .05       0    4618     .12       0  4845.7     .07       0
  4982.4     .05       0  5002.6     .07       0  5019.1     .12       0
  5164.9     .07       0  5265.4     .12       0  5285.1     .07       0
Bank Sta=4982.4,5002.6
XS Rating Curve= 0 ,0
Exp/Cntr=0.3,0.1

Type RM Length L Ch R = 1 ,84419   ,568,568,568
BEGIN DESCRIPTION:
TRIB 2 TO GUADALUPE RIVER 65.0
END DESCRIPTION:
XS GIS Cut Line= 3
      2588625.01     13439275.02        2588425.       13438925.
      2588075.01     13438625.01
#Sta/Elev= 30
  4596.4   78.66    4654   75.61    4677   72.96  4690.7   72.79  4728.2   70.25
  4734.6    68.8    4803   65.19  4830.4   62.52  4861.3   61.51  4873.6   59.81
  4889.4   59.27  4905.2   57.04  4985.9   55.69  4991.6   54.07  4996.6   50.96
  4997.1   50.46  5016.8   50.96  5020.9   52.92  5035.2    55.8  5056.1   57.37
  5148.3   60.15  5162.5   59.79  5191.1    61.9  5259.1   65.13  5283.3   67.16
  5297.5   67.44  5304.1    68.8  5380.9   73.63  5424.8   77.01  5460.5   78.65
#Mann= 5 ,-1 , 0
  4596.4     .12       0  4996.6     .05       0  5016.8     .12       0
  5259.1     .07       0  5380.9     .12       0
Bank Sta=4996.6,5016.8
XS Rating Curve= 0 ,0
Exp/Cntr=0.3,0.1

Type RM Length L Ch R = 1 ,83851   ,564,564,564
BEGIN DESCRIPTION:
TRIB 2 TO GUADALUPE RIVER 64.0
END DESCRIPTION:
XS GIS Cut Line= 3
      2589074.99     13439274.97        2588875.       13438625.
        2588875.     13438225.04
#Sta/Elev= 30
  4315.6   85.11  4331.9   84.17    4347   84.32  4364.6   82.51  4468.4   76.79
  4500.6   73.78  4538.6   71.73  4545.7   70.61    4566    70.3  4636.6   65.53
  4734.1   61.31    4755    59.8  4850.7   56.31  4941.4   55.11  4979.3    56.7
  4988.8   54.99  4998.1    54.4  5005.5   48.77    5006   48.27  5025.8   48.77
  5055.6   52.47  5095.6   59.19  5105.6    58.4  5125.6    58.2    5128   58.77
  5135.6   60.57  5255.6   69.35  5313.3   70.45  5366.7   73.46  5395.6   75.06
#Mann= 9 ,-1 , 0
  4315.6     .05       0  4468.4     .12       0  4850.7     .07       0
  4988.8     .12       0  5005.5     .05       0  5025.8     .12       0
    5128     .07       0  5313.3     .05       0  5366.7     .07       0
Bank Sta=5005.5,5025.8
XS Rating Curve= 0 ,0
Exp/Cntr=0.3,0.1

Type RM Length L Ch R = 1 ,83287   ,509,509,509
BEGIN DESCRIPTION:
TRIB 2 TO GUADALUPE RIVER 63.0
END DESCRIPTION:
XS GIS Cut Line= 3
        2589325.     13438925.02        2589325.       13438525.
      2589225.01     13438125.03
#Sta/Elev= 30
  4599.7   72.96  4683.5   67.83  4789.7   61.85  4849.7   56.67  4880.7   55.11
  4909.7      54  4939.7   54.37  4989.7   53.79  4997.2   51.49  5002.3   51.49
  5007.6   46.82  5008.1   46.32  5027.4   46.32  5027.9   46.82  5030.6   50.62
  5051.3   53.73  5092.5   55.15  5141.4   55.66  5146.6   56.27  5187.8   57.01
  5205.9   58.85  5216.2   60.78  5229.1   60.34  5298.6   66.61  5306.4   68.04
  5329.6   69.32  5339.9   70.74  5388.8    73.3  5401.7   74.69    5412    74.8
#Mann= 5 ,-1 , 0
  4599.7     .07       0  4683.5     .12       0  4880.7     .07       0
  5007.6     .05       0  5027.9     .07       0
Bank Sta=5007.6,5027.9
XS Rating Curve= 0 ,0
Exp/Cntr=0.3,0.1

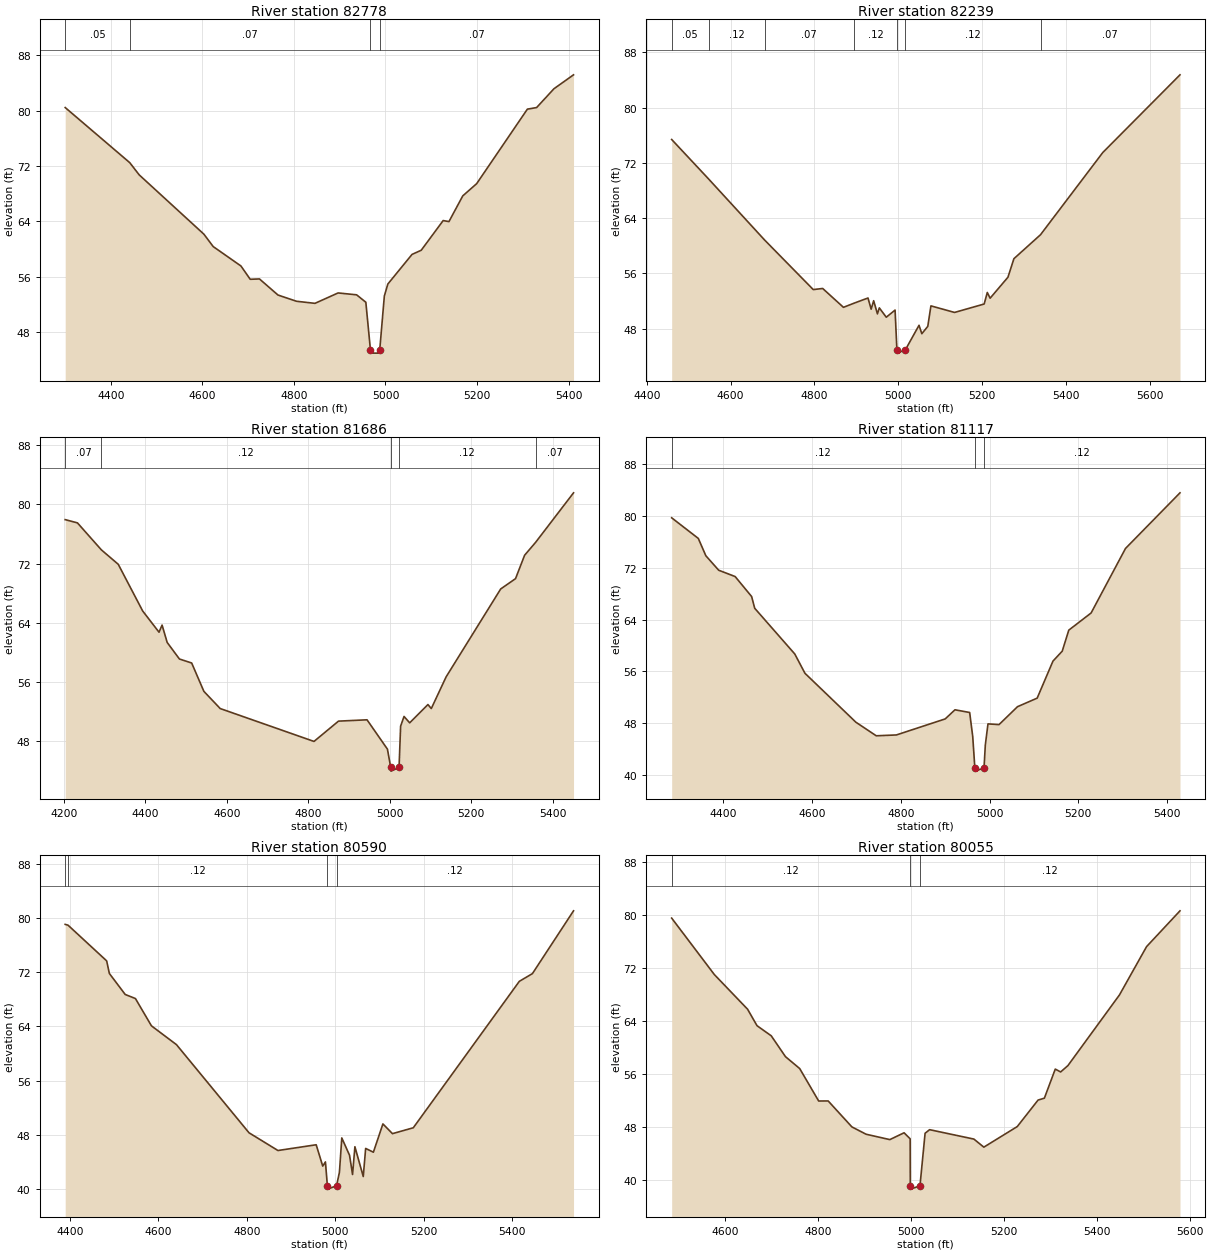
Type RM Length L Ch R = 1 ,82778   ,539,539,539
BEGIN DESCRIPTION:
TRIB 2 TO GUADALUPE RIVER 62.0
END DESCRIPTION:
XS GIS Cut Line= 3
        2589675.     13439124.99        2589775.       13438425.
        2589825.     13438025.01
#Sta/Elev= 30
  4300.5   80.43  4441.5   72.48  4462.1   70.72  4603.5   62.16  4623.7   60.38
  4684.3   57.58  4704.6   55.66  4724.8   55.71  4765.2   53.39  4805.6   52.49
    4846   52.19  4896.5   53.69  4936.9   53.42  4957.1   52.35  4967.1   45.51
  4967.6   45.01    4987   45.01  4987.5   45.51  4997.5   53.24  5005.1   54.97
    5058   59.25  5078.1   59.85    5126   64.13  5138.6   63.98  5168.8   67.69
  5199.1   69.45  5309.9    80.2  5330.1   80.43  5367.9   83.14  5410.7   85.15
#Mann= 4 ,-1 , 0
  4300.5     .05       0  4441.5     .07       0  4967.1     .05       0
  4987.5     .07       0
Bank Sta=4967.1,4987.5
XS Rating Curve= 0 ,0
Exp/Cntr=0.3,0.1

Type RM Length L Ch R = 1 ,82239   ,553,553,553
BEGIN DESCRIPTION:
TRIB 2 TO GUADALUPE RIVER 61.0
END DESCRIPTION:
XS GIS Cut Line= 3
      2589925.01     13439124.98        2590225.       13438675.
        2590675.     13438174.99
#Sta/Elev= 30
  4459.3   75.38  4548.1   69.62  4681.4   60.81  4797.3   53.65  4819.8   53.81
  4869.4   51.08  4894.2   51.67    4928   52.43  4935.5   50.81  4941.5   52.04
  4950.5   50.13    4955      51  4971.6   49.65  4992.6   50.68    4997   44.95
  4997.5   44.45  5017.4   44.95  5049.8   48.48  5056.5   47.26  5070.7   48.32
  5078.2   51.29  5134.6   50.34  5205.3   51.56  5212.8   53.23  5219.5    52.4
  5262.1   55.44  5276.3   58.12  5339.8   61.59  5488.6    73.5  5672.8   84.74
#Mann= 7 ,-1 , 0
  4459.3     .05       0  4548.1     .12       0  4681.4     .07       0
  4894.2     .12       0    4997     .05       0  5017.4     .12       0
  5339.8     .07       0
Bank Sta=4997,5017.4
XS Rating Curve= 0 ,0
Exp/Cntr=0.3,0.1

Type RM Length L Ch R = 1 ,81686   ,569,569,569
BEGIN DESCRIPTION:
TRIB 2 TO GUADALUPE RIVER 60.0
END DESCRIPTION:
XS GIS Cut Line= 3
        2590675.     13439625.05        2590725.       13438825.
      2590924.99     13438425.02
#Sta/Elev= 30
  4202.8   77.93  4232.9   77.49  4291.8   73.84  4333.1    71.9  4393.2   65.59
  4433.3   62.73  4440.8   63.69  4453.3   61.35  4483.4   59.11  4513.5   58.57
  4543.5   54.74  4583.6   52.42    4814   47.98  4874.2   50.72  4944.3    50.9
  4994.4   46.94  5002.5   44.47    5003   43.97    5023   44.47  5026.8   50.04
  5035.2   51.35  5049.1   50.49  5093.9   52.96  5102.2   52.42  5138.6    56.7
  5272.7   68.57  5309.1   69.96  5331.4   73.12  5358.4   74.86  5451.6   81.55
#Mann= 5 ,-1 , 0
  4202.8     .07       0  4291.8     .12       0  5002.5     .05       0
    5023     .12       0  5358.4     .07       0
Bank Sta=5002.5,5023
XS Rating Curve= 0 ,0
Exp/Cntr=0.3,0.1

Type RM Length L Ch R = 1 ,81117   ,527,527,527
BEGIN DESCRIPTION:
TRIB 2 TO GUADALUPE RIVER 59.0
END DESCRIPTION:
XS GIS Cut Line= 3
      2590875.02     13439724.96        2591175.       13439075.
      2591525.03     13438824.98
#Sta/Elev= 30
  4283.4   79.74  4343.5   76.55  4360.4   73.88  4389.4   71.64  4426.5   70.66
  4463.7   67.57  4470.6   65.76    4561   58.69  4583.9   55.71  4698.7   48.15
  4744.6   46.05    4790   46.18  4900.1   48.66  4922.1   50.07  4955.2   49.65
  4962.1   45.96  4966.9   41.09  4967.4   40.59  4987.6   41.09  4990.5   44.62
  4996.5   47.89  5021.4   47.78  5063.1   50.55  5107.4   51.87    5143   57.59
  5163.9   59.13  5178.7   62.38    5229   65.03  5306.5      75  5429.4    83.6
#Mann= 3 ,-1 , 0
  4283.4     .12       0  4966.9     .05       0  4987.6     .12       0
Bank Sta=4966.9,4987.6
XS Rating Curve= 0 ,0
Exp/Cntr=0.3,0.1

Type RM Length L Ch R = 1 ,80590   ,535,535,535
BEGIN DESCRIPTION:
TRIB 2 TO GUADALUPE RIVER 58.0
END DESCRIPTION:
XS GIS Cut Line= 3
      2590925.02     13439774.99        2591425.       13439425.
      2591624.99     13438925.02
#Sta/Elev= 30
  4389.7   79.07  4396.1   78.95  4483.4   73.68  4489.5   71.82  4525.3   68.72
  4548.4   68.12  4584.6   64.09  4641.2   61.31  4805.1    48.3  4870.5   45.68
  4956.9   46.53  4971.7   43.38  4977.8      44  4982.2   40.48  4982.7   39.98
  5002.9   40.48  5009.4   42.45  5014.8   47.54  5032.3   44.98  5039.1   42.14
  5044.4   46.24  5063.3   41.84  5068.7   45.99  5086.2   45.43  5107.7   49.61
  5129.3   48.17  5176.4   49.04    5416   70.66  5445.6    71.8  5538.5   81.07
#Mann= 4 ,-1 , 0
  4389.7     .07       0  4396.1     .12       0  4982.2     .05       0
  5002.9     .12       0
Bank Sta=4982.2,5002.9
XS Rating Curve= 0 ,0
Exp/Cntr=0.3,0.1

Type RM Length L Ch R = 1 ,80055   ,558,558,558
BEGIN DESCRIPTION:
TRIB 2 TO GUADALUPE RIVER 57.0
END DESCRIPTION:
XS GIS Cut Line= 3
        2591625.     13440124.98        2591725.       13439625.
      2592025.01     13439124.98
#Sta/Elev= 30
  4485.9    79.5  4577.7   70.97  4649.1   65.74  4669.4   63.25    4700   61.72
  4730.6   58.57  4761.2   56.77    4802   51.87  4822.4   51.88  4873.4   47.96
    4904   46.85    4955   46.04  4985.6   47.07  4998.7   46.16    4999   39.06
  4999.5   38.56  5019.8   39.06  5030.8      47  5040.5   47.54  5135.7   46.12
  5157.1    44.9    5229   48.01  5273.7   52.01  5287.3    52.3  5310.7   56.69
  5322.3   56.26  5337.9   57.22  5448.7   67.89    5507   75.19  5578.9    80.6
#Mann= 3 ,-1 , 0
  4485.9     .12       0    4999     .05       0  5019.8     .12       0
Bank Sta=4999,5019.8
XS Rating Curve= 0 ,0
Exp/Cntr=0.3,0.1