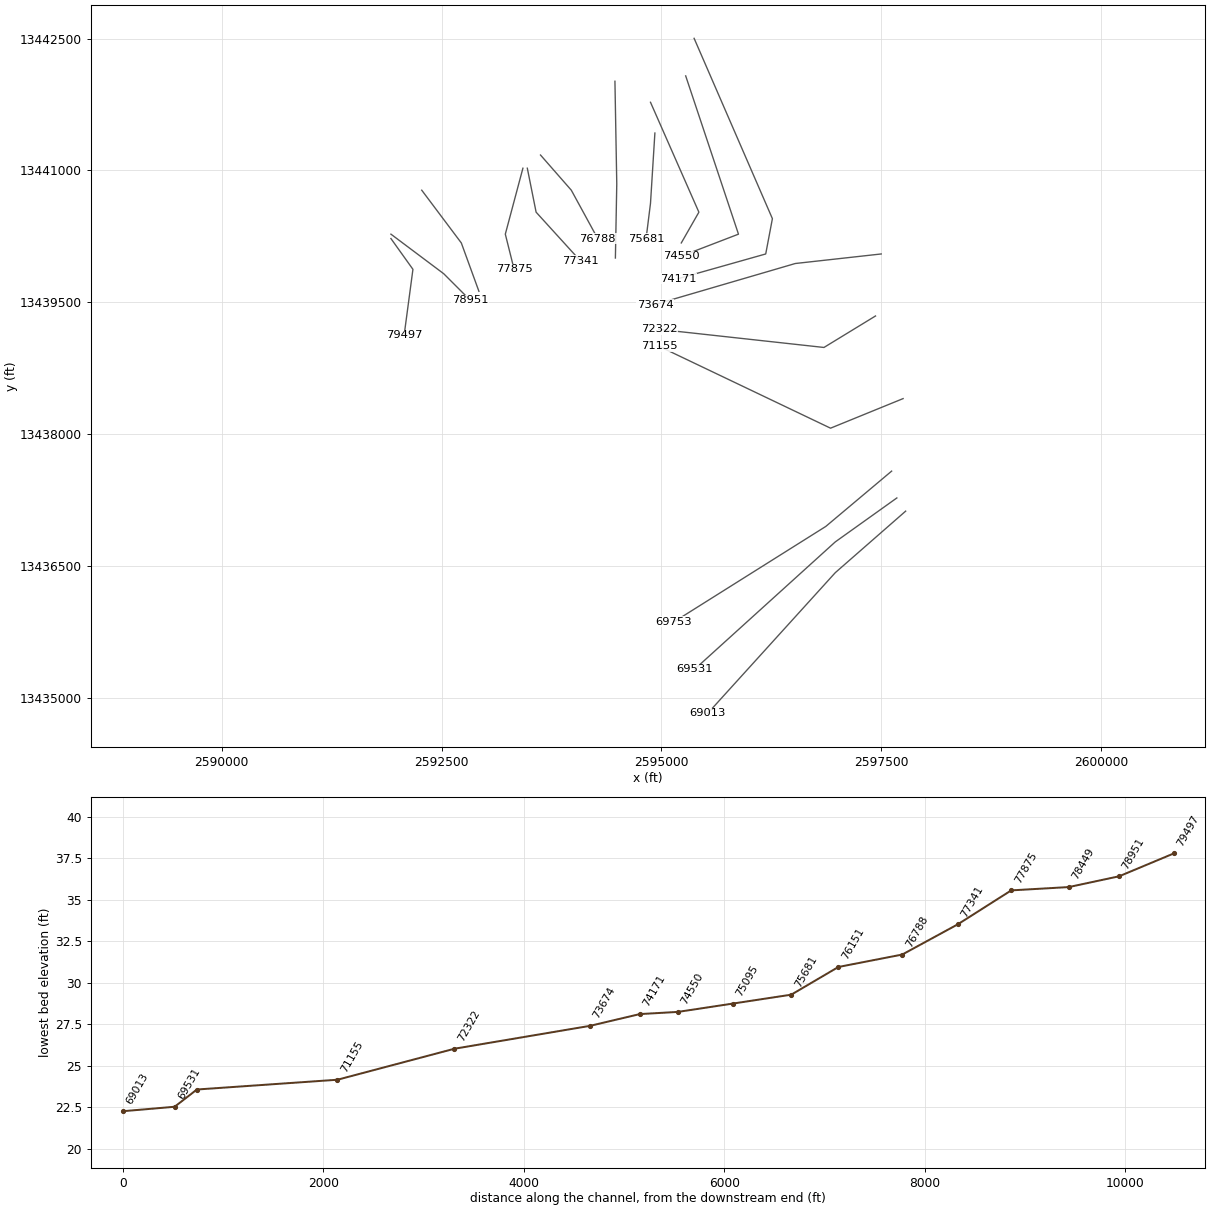
HEC-RAS study TRIB 2 TO GUADALUPE RIVER.prj: TRIB 2 TO GUADALUPE RIVER Base Level Engineering

--- TRIB 2 TO GUADALUPE RIVER.g01 (geometry) --- (continued)

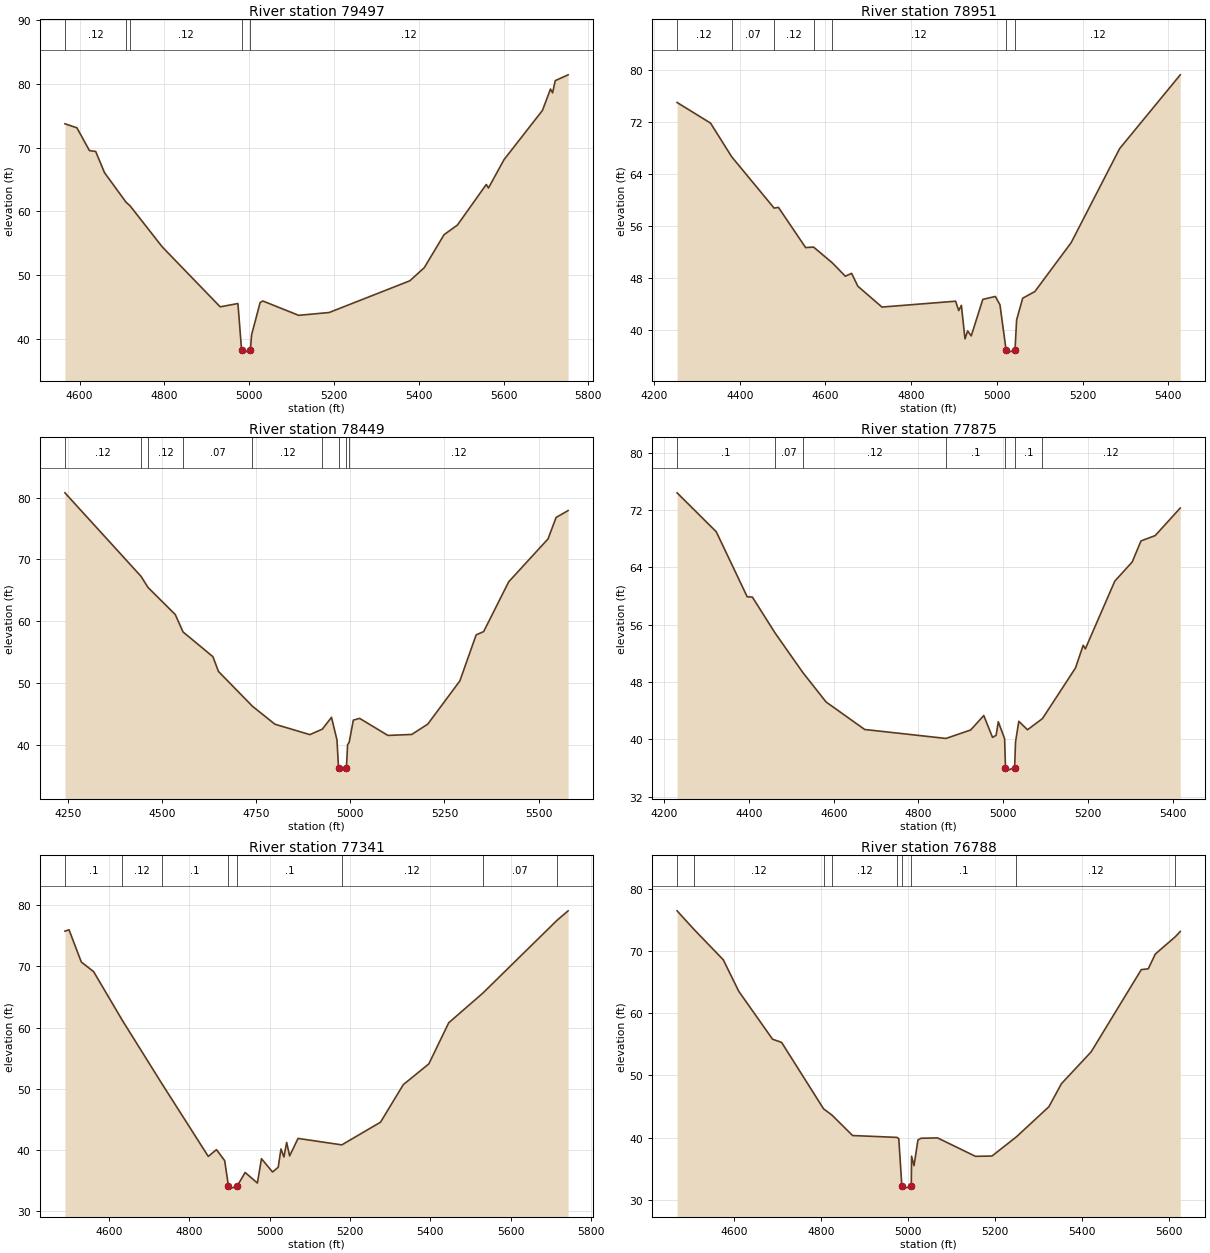
Type RM Length L Ch R = 1 ,79497   ,546,546,546
BEGIN DESCRIPTION:
TRIB 2 TO GUADALUPE RIVER 56.0
END DESCRIPTION:
XS GIS Cut Line= 3
      2591924.98     13440225.02        2592175.       13439875.
        2592075.     13439124.98
#Sta/Elev= 30
  4565.6   73.72  4593.9   73.09  4623.4   69.52  4638.1   69.39    4659   66.06
  4709.6   61.45  4719.7   60.83  4795.4   54.42  4931.8   45.05  4973.6   45.57
  4982.2    38.3  4982.7    37.8  5003.1    38.3  5005.8   40.65    5026   45.73
  5032.3   45.97  5116.8   43.72  5188.7   44.16  5379.1   49.13  5413.2   51.19
  5459.8   56.35  5491.3   57.86  5559.4   64.22  5564.5   63.66  5601.1   68.09
  5691.9   75.82  5710.8   79.16  5715.8   78.57  5722.1   80.48  5752.4   81.39
#Mann= 5 ,-1 , 0
  4565.6     .12       0  4709.6     .07       0  4719.7     .12       0
  4982.2     .05       0  5003.1     .12       0
Bank Sta=4982.2,5003.1
XS Rating Curve= 0 ,0
Exp/Cntr=0.3,0.1

Type RM Length L Ch R = 1 ,78951   ,502,502,502
BEGIN DESCRIPTION:
TRIB 2 TO GUADALUPE RIVER 55.0
END DESCRIPTION:
XS GIS Cut Line= 3
        2591925.       13440275.        2592525.       13439825.
      2592825.02     13439524.98
#Sta/Elev= 30
  4253.7   74.94  4331.8   71.77    4381   66.61  4480.1   58.71  4490.2   58.82
  4553.7   52.64  4572.2   52.72  4615.7   50.31  4646.4   48.24    4661   48.68
  4675.6    46.7  4731.8    43.5  4903.7    44.4    4911   42.96  4917.2   43.77
  4925.6   38.61  4931.8   39.83  4940.2   39.07  4967.2   44.68  4996.4   45.13
  5007.2   43.86  5021.5   36.92    5022   36.42  5042.4   36.92  5046.1   41.53
  5060.3   44.86  5088.6   45.88  5173.4    53.4  5286.5   67.85    5428   79.19
#Mann= 7 ,-1 , 0
  4253.7     .12       0    4381     .07       0  4480.1     .12       0
  4572.2     .07       0  4615.7     .12       0  5021.5     .05       0
  5042.4     .12       0
Bank Sta=5021.5,5042.4
XS Rating Curve= 0 ,0
Exp/Cntr=0.3,0.1

Type RM Length L Ch R = 1 ,78449   ,574,574,574
BEGIN DESCRIPTION:
TRIB 2 TO GUADALUPE RIVER 54.0
END DESCRIPTION:
XS GIS Cut Line= 3
      2592274.99     13440775.01        2592725.       13440175.
      2592924.98     13439625.04
#Sta/Elev= 30
  4242.9   80.76  4444.8   67.26  4463.7   65.44  4535.6   61.09  4556.3   58.27
  4635.6   54.27  4650.2   51.89  4740.3   46.27  4800.2   43.35  4892.9   41.67
    4926   42.56  4950.2   44.47  4964.8    40.8  4968.9   36.27  4969.4   35.77
  4989.8   36.27  4992.9   40.04    4997    40.4  5008.2   44.01  5024.8    44.3
    5100   41.54  5163.2    41.7  5205.7   43.37  5290.8   50.35  5334.1    57.8
    5354   58.33  5420.5   66.38  5524.9   73.32  5546.2   76.78  5578.1   77.89
#Mann= 9 ,-1 , 0
  4242.9     .12       0  4444.8     .07       0  4463.7     .12       0
  4556.3     .07       0  4740.3     .12       0    4926      .1       0
  4968.9     .05       0  4989.8      .1       0    4997     .12       0
Bank Sta=4968.9,4989.8
XS Rating Curve= 0 ,0
Exp/Cntr=0.3,0.1

Type RM Length L Ch R = 1 ,77875   ,534,534,534
BEGIN DESCRIPTION:
TRIB 2 TO GUADALUPE RIVER 53.0
END DESCRIPTION:
XS GIS Cut Line= 3
      2593424.99     13441024.98        2593225.       13440275.
        2593325.       13439875.
#Sta/Elev= 30
  4229.8    74.4  4322.3   68.97  4395.4    59.9  4407.7   59.85  4461.4   54.83
  4526.9   49.32  4581.7   45.22  4672.9   41.38  4864.8   40.13  4923.2   41.31
  4954.2   43.33  4974.9   40.28  4983.3   40.56  4988.5   42.46  5003.4    40.1
  5005.5   36.07    5006   35.57  5027.1   36.07  5029.2   39.63  5036.9   42.52
  5057.5   41.34  5092.8    42.9  5170.9   49.97    5189   53.13  5194.1   52.63
  5263.7   62.08  5304.9   64.76  5325.5   67.69    5359   68.43  5418.3   72.28
#Mann= 7 ,-1 , 0
  4229.8      .1       0  4461.4     .07       0  4526.9     .12       0
  4864.8      .1       0  5005.5     .05       0  5027.1      .1       0
  5092.8     .12       0
Bank Sta=5005.5,5027.1
XS Rating Curve= 0 ,0
Exp/Cntr=0.3,0.1

Type RM Length L Ch R = 1 ,77341   ,553,553,553
BEGIN DESCRIPTION:
TRIB 2 TO GUADALUPE RIVER 52.0
END DESCRIPTION:
XS GIS Cut Line= 3
      2593474.99     13441025.04        2593575.       13440525.
      2594074.97     13439975.03
#Sta/Elev= 30
  4490.1   75.79  4500.3   76.01  4530.9   70.73  4561.5   69.16  4633.4   61.14
  4731.2   50.84  4847.1   38.88  4867.5   39.99  4887.9   38.19  4897.4   34.02
  4897.9   33.52  4919.1   34.02  4938.9   36.25  4969.4   34.52  4979.6   38.51
  5007.1   36.33  5021.3    37.1  5028.1    40.1  5035.5   38.79  5042.3   41.17
  5049.7   38.96  5070.7   41.83  5179.7   40.77  5276.1   44.49  5332.8   50.64
  5396.4   54.04    5446   60.78  5530.8   65.63  5716.2    77.6  5743.3   79.12
#Mann= 8 ,-1 , 0
  4490.1      .1       0  4633.4     .12       0  4731.2      .1       0
  4897.4     .05       0  4919.1      .1       0  5179.7     .12       0
  5530.8     .07       0  5716.2     .05       0
Bank Sta=4897.4,4919.1
XS Rating Curve= 0 ,0
Exp/Cntr=0.3,0.1

Type RM Length L Ch R = 1 ,76788   ,637,637,637
BEGIN DESCRIPTION:
TRIB 2 TO GUADALUPE RIVER 51.0
END DESCRIPTION:
XS GIS Cut Line= 3
        2593625.       13441175.        2593975.       13440775.
        2594275.     13440225.01
#Sta/Elev= 30
  4468.4   76.51  4507.3   73.52  4574.7   68.63  4610.3   63.56  4688.1   55.84
    4709   55.32  4805.5   44.63  4824.7   43.63  4872.3   40.33  4974.2   40.03
  4978.6   39.83  4985.7    32.2  4986.2    31.7  5007.4    32.2    5008      37
  5013.7   35.48  5022.7   39.61  5029.8   39.89  5067.8   39.95  5155.1   36.98
  5193.1   37.03    5249    40.1  5324.1   44.97    5353   48.68  5421.4   53.81
  5536.7   67.04  5552.8   67.18    5569   69.55  5615.2   72.35  5626.4   73.19
#Mann= 9 ,-1 , 0
  4468.4     .07       0  4507.3     .12       0  4805.5     .07       0
  4824.7     .12       0  4974.2      .1       0  4985.7     .05       0
  5007.4      .1       0    5249     .12       0  5615.2     .07       0
Bank Sta=4985.7,5007.4
XS Rating Curve= 0 ,0
Exp/Cntr=0.3,0.1

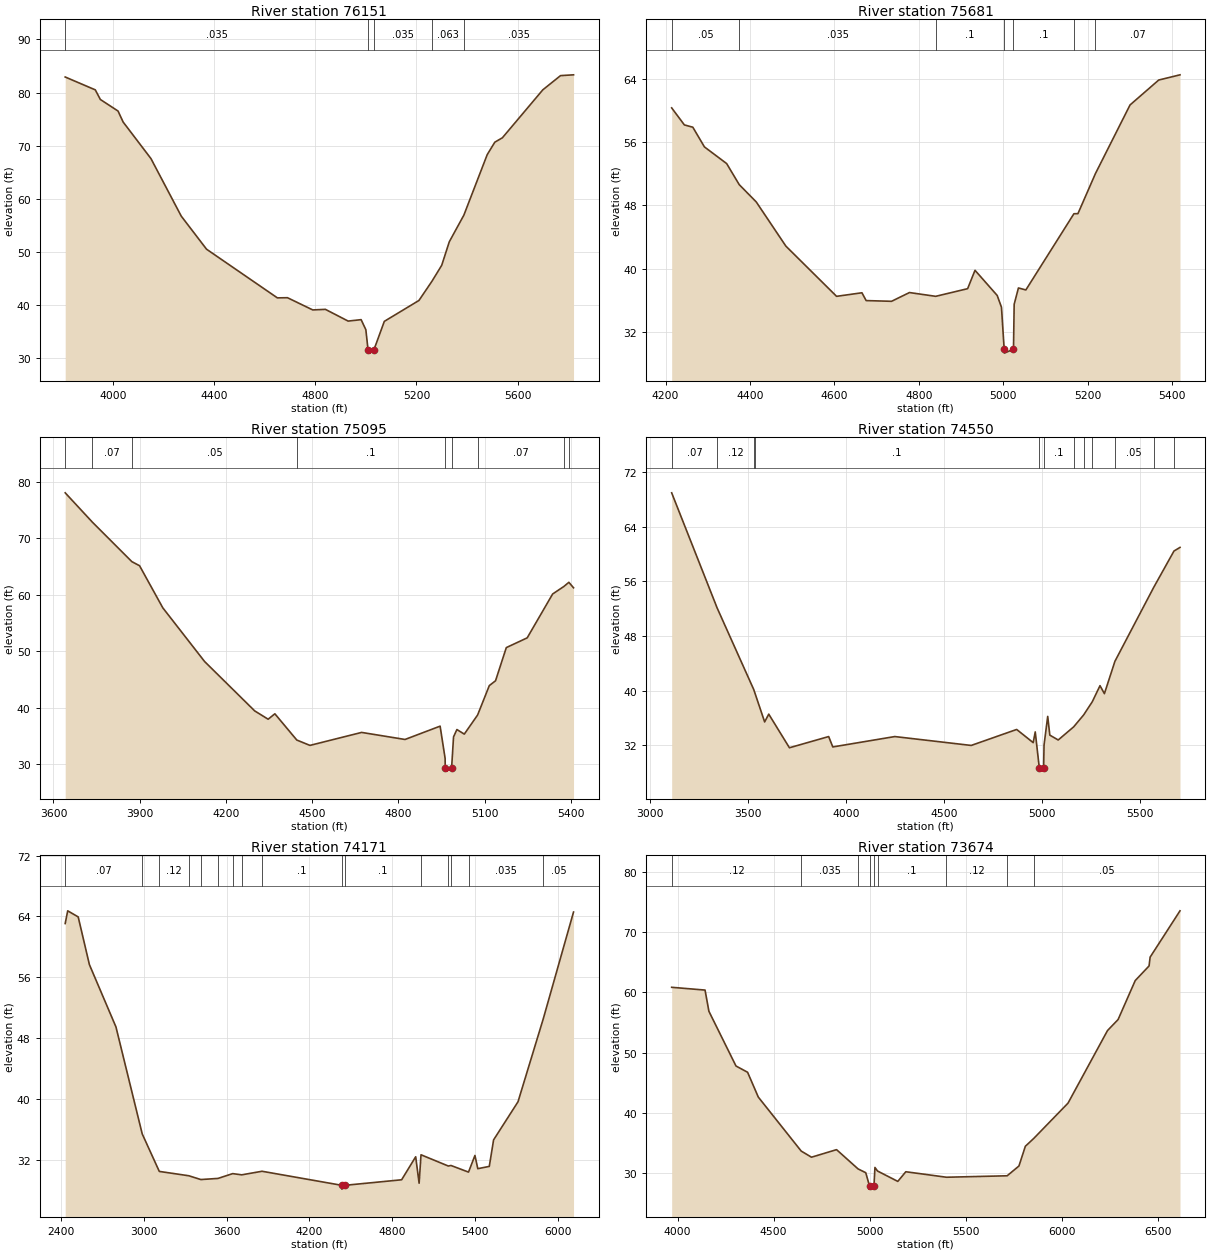
Type RM Length L Ch R = 1 ,76151   ,470,470,470
BEGIN DESCRIPTION:
Mapping XS 3fc625e3
END DESCRIPTION:
XS GIS Cut Line= 3
       2594470.9     13442014.02      2594491.73     13440847.37
      2594476.11     13440003.65
#Sta/Elev= 30
  3810.5   82.92  3929.5    80.5  3949.5   78.69  4019.6   76.51  4039.6   74.45
  4149.6   67.57  4269.6   56.73  4369.6   50.51  4649.7   41.35  4689.7   41.38
  4789.7   39.08  4839.7   39.19  4929.7   36.98    4981   37.25  4999.7   35.36
  5008.7   31.45  5009.2   30.95  5030.7   31.45  5072.8   36.93  5209.7   40.86
  5261.9   44.53  5299.8   47.48  5329.8   51.91  5387.4   56.92  5479.8   68.31
  5509.8   70.65  5539.8   71.48  5699.8   80.51  5769.8   83.18  5821.2   83.33
#Mann= 5 ,-1 , 0
  3810.5    .035       0  5008.7    .035       0  5030.7    .035       0
  5261.9    .063       0  5387.4    .035       0
Bank Sta=5008.7,5030.7
XS Rating Curve= 0 ,0
Exp/Cntr=0.3,0.1

Type RM Length L Ch R = 1 ,75681   ,586,586,586
BEGIN DESCRIPTION:
TRIB 2 TO GUADALUPE RIVER 49.0
END DESCRIPTION:
XS GIS Cut Line= 3
        2594925.     13441425.04        2594875.       13440625.
        2594825.     13440225.01
#Sta/Elev= 30
  4214.4   60.37  4244.5   58.21  4264.5   57.92  4292.1   55.42  4344.7   53.31
  4374.5   50.64  4414.8   48.45    4485   42.85  4605.2   36.48  4665.3   36.93
  4675.3   35.94  4735.5   35.85    4778   36.96  4840.1   36.48  4915.8   37.45
  4933.3   39.78  4985.9   36.59    4996    35.1  5002.4   29.78  5002.9   29.28
  5024.5   29.78  5026.1   35.47  5036.2   37.54  5053.8   37.29  5167.7   46.95
  5177.2   46.96  5218.7   52.04  5300.7   60.74  5368.7    63.9  5419.1   64.56
#Mann= 7 ,-1 , 0
  4214.4     .05       0  4374.5    .035       0  4840.1      .1       0
  5002.4     .05       0  5024.5      .1       0  5167.7    .035       0
  5218.7     .07       0
Bank Sta=5002.4,5024.5
XS Rating Curve= 0 ,0
Exp/Cntr=0.3,0.1

Type RM Length L Ch R = 1 ,75095   ,545,545,545
BEGIN DESCRIPTION:
TRIB 2 TO GUADALUPE RIVER 48.0
END DESCRIPTION:
XS GIS Cut Line= 3
      2594875.02     13441774.96        2595425.       13440525.
      2595225.01     13440175.02
#Sta/Elev= 30
  3640.8   78.06  3735.4   72.86  3872.8   65.86  3899.5   65.14  3980.4   57.68
  4125.9   48.16  4300.2   39.41  4346.9   37.94  4370.3    38.9  4446.6   34.25
  4492.4    33.3  4672.2    35.6  4823.2   34.35  4945.3   36.71  4962.7   30.99
  4963.1   29.24  4963.6   28.74  4985.2   29.24    4992   34.81  5003.7   36.11
  5029.4    35.3  5075.7   38.68  5116.5    43.9  5138.1   44.75  5175.6   50.63
  5248.3   52.36  5336.8   60.13    5376   61.47  5393.3    62.2  5409.5   61.23
#Mann= 9 ,-1 , 0
  3640.8     .05       0  3735.4     .07       0  3872.8     .05       0
  4446.6      .1       0  4963.1     .05       0  4985.2      .1       0
  5075.7     .07       0    5376    .035       0  5393.3     .05       0
Bank Sta=4963.1,4985.2
XS Rating Curve= 0 ,0
Exp/Cntr=0.3,0.1

Type RM Length L Ch R = 1 ,74550   ,379,379,379
BEGIN DESCRIPTION:
TRIB 2 TO GUADALUPE RIVER 47.0
END DESCRIPTION:
XS GIS Cut Line= 3
      2595274.99     13442075.02        2595875.       13440275.
      2595225.01       13440025.
#Sta/Elev= 30
  3108.6   68.98  3340.7   52.12  3526.8   40.22  3531.8   39.81    3583   35.44
    3604   36.58  3709.5   31.66  3909.7    33.3  3930.8   31.78    4247    33.3
  4637.1      32    4869   34.34  4953.3   32.41  4963.8   33.98  4984.4   28.74
  4984.9   28.24  5006.5   28.74  5008.7   32.07  5027.4   36.25  5038.1   33.51
    5081    32.8  5159.8   34.72  5210.6   36.46  5254.9    38.4  5294.2   40.75
  5316.7   39.58  5370.4   44.32  5567.5    55.1  5671.7   60.46  5702.4   60.99
#Mann= 12 ,-1 , 0
  3108.6     .07       0  3340.7     .12       0  3526.8    .035       0
  3531.8      .1       0  4984.4     .05       0  5006.5      .1       0
  5159.8     .07       0  5210.6      .1       0  5254.9     .07       0
  5370.4     .05       0  5567.5    .035       0  5671.7     .05       0
Bank Sta=4984.4,5006.5
XS Rating Curve= 0 ,0
Exp/Cntr=0.3,0.1

Type RM Length L Ch R = 1 ,74171   ,497,497,497
BEGIN DESCRIPTION:
Mapping XS 733b4b34
END DESCRIPTION:
XS GIS Cut Line= 4
      2595370.81     13442502.05      2596260.56     13440451.28
       2596184.6     13440049.81       2595188.2     13439768.21
#Sta/Elev= 30
    2432   63.06  2450.1   64.73    2526   63.93  2607.2   57.65  2799.4   49.45
  2989.4   35.38  3113.1   30.44  3326.5   29.87  3413.7   29.37  3538.1   29.52
  3644.3   30.15  3709.6   29.99  3856.8   30.46  4434.4   28.61  4434.9   28.11
  4456.5   28.61  4867.2   29.34    4969   32.37  4993.8   28.89  5007.5   32.63
    5205   31.15  5224.6   31.22  5351.4   30.35  5397.8   32.54  5418.6    30.8
  5501.7    31.1  5532.9   34.59  5709.5    39.6  5892.1    50.5  6111.5   64.57
#Mann= 16 ,-1 , 0
    2432     .07       0  2989.4    .035       0  3113.1     .12       0
  3326.5      .1       0  3413.7     .12       0  3538.1     .07       0
  3644.3      .1       0  3709.6     .07       0  3856.8      .1       0
  4434.4     .05       0  4456.5      .1       0  5007.5    .035       0
    5205      .1       0  5224.6     .12       0  5351.4    .035       0
  5892.1     .05       0
Bank Sta=4434.4,4456.5
XS Rating Curve= 0 ,0
Exp/Cntr=0.3,0.1

Type RM Length L Ch R = 1 ,73674   ,1352,1352,1352
BEGIN DESCRIPTION:
Mapping XS 2af3b94e
END DESCRIPTION:
XS GIS Cut Line= 3
      2597497.58     13440049.81      2596520.98      13439941.3
      2594925.93     13439474.72
#Sta/Elev= 30
  3969.5   60.84  4143.1   60.38  4163.3   56.86  4304.1    47.8  4364.5   46.76
  4420.2   42.65  4643.5    33.7  4696.9   32.69  4827.3   33.94  4939.2   30.75
  4979.2   30.12    4999    27.9  4999.5    27.4  5021.9    27.9    5027   30.99
  5040.4    30.4  5145.9   28.68  5187.6   30.28    5399   29.37  5714.8   29.61
  5776.1   31.23  5809.5    34.5  5852.9   35.79  6031.5   41.65  6236.8   53.67
    6292    55.5    6381   61.95  6453.1   64.38  6458.7   65.84    6614   73.51
#Mann= 9 ,-1 , 0
  3969.5     .12       0  4643.5    .035       0  4939.2      .1       0
    4999     .05       0  5021.9      .1       0  5040.4      .1       0
    5399     .12       0  5714.8    .035       0  5852.9     .05       0
Bank Sta=4999,5021.9
XS Rating Curve= 0 ,0
Exp/Cntr=0.3,0.1

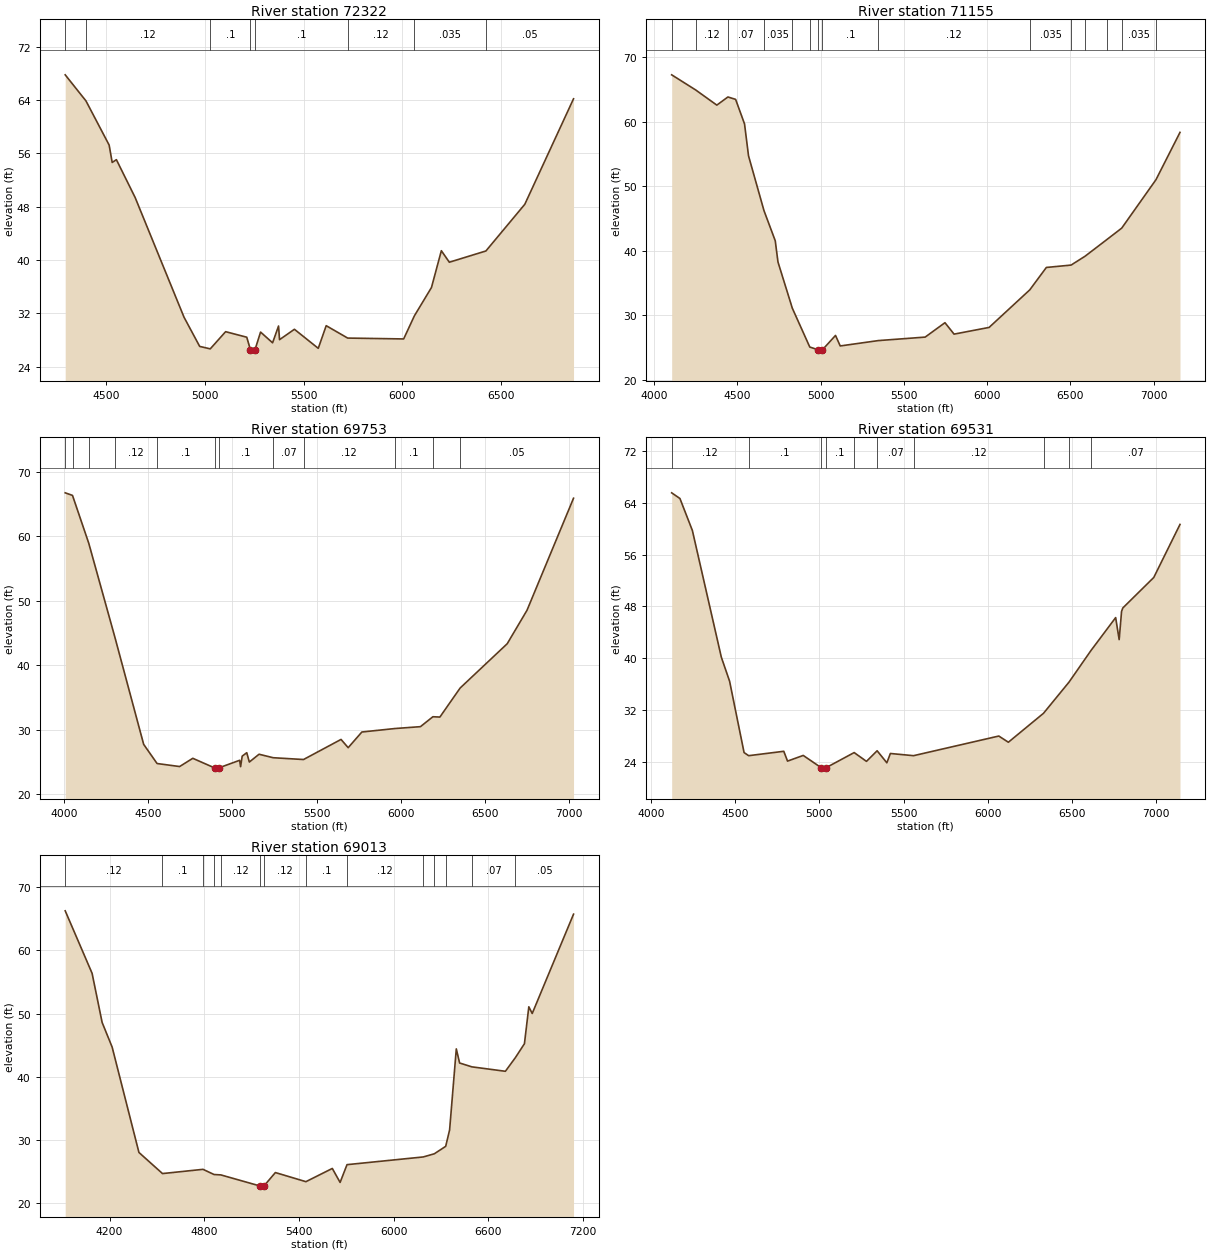
Type RM Length L Ch R = 1 ,72322   ,1167,1167,1167
BEGIN DESCRIPTION:
Mapping XS 2073a367
END DESCRIPTION:
XS GIS Cut Line= 3
      2597432.46     13439344.53       2596846.5     13438986.44
       2594969.7     13439192.56
#Sta/Elev= 30
  4292.7   67.81  4397.9   63.89  4515.3   57.26  4530.7   54.65    4552   55.07
  4646.9   49.39  4894.6   31.41  4973.9   27.03  5027.4   26.66  5105.2   29.24
  5212.3   28.41    5231   26.52  5231.5   26.02    5254   26.52  5282.3   29.18
  5343.1   27.57  5373.3   30.09  5378.4   28.04  5453.7    29.6  5574.5   26.74
  5614.7   30.14  5723.5   28.28  6007.1   28.15  6061.6   31.63  6147.9   35.87
    6198    41.4  6238.4   39.67  6423.7   41.36  6620.7   48.37  6867.5   64.21
#Mann= 8 ,-1 , 0
  4292.7     .07       0  4397.9     .12       0  5027.4      .1       0
    5231     .05       0    5254      .1       0  5723.5     .12       0
  6061.6    .035       0  6423.7     .05       0
Bank Sta=5231,5254
XS Rating Curve= 0 ,0
Exp/Cntr=0.3,0.1

Type RM Length L Ch R = 1 ,71155   ,1402,1402,1402
BEGIN DESCRIPTION:
Mapping XS 2fcd875a
END DESCRIPTION:
XS GIS Cut Line= 3
      2597746.05     13438404.85      2596921.37     13438068.47
      2594970.81      13439000.4
#Sta/Elev= 30
  4105.3   67.23  4249.3   64.89  4376.4   62.54    4443    63.8  4489.3   63.43
  4542.8   59.63  4566.8   54.69  4659.6   46.21  4727.3   41.54  4743.6   38.26
  4829.7   31.11  4934.7   25.09  4986.9   24.65  4987.4   24.15    5010   24.65
  5089.2   26.89  5117.4   25.26    5346   26.09  5627.5   26.63  5746.4   28.86
    5801   27.09  6011.5   28.13  6255.9   33.95  6355.1   37.41  6503.9   37.78
  6587.1   39.14  6720.1   41.76  6807.8    43.5  7013.5      51  7157.7   58.32
#Mann= 15 ,-1 , 0
  4105.3     .07       0  4249.3     .12       0    4443     .07       0
  4659.6    .035       0  4829.7     .12       0  4934.7      .1       0
  4986.9     .05       0    5010      .1       0    5346     .12       0
  6255.9    .035       0  6503.9     .05       0  6587.1    .035       0
  6720.1     .05       0  6807.8    .035       0  7013.5     .05       0
Bank Sta=4986.9,5010
XS Rating Curve= 0 ,0
Exp/Cntr=0.3,0.1

Type RM Length L Ch R = 1 ,69753   ,222,222,222
BEGIN DESCRIPTION:
Mapping XS fb77b644
END DESCRIPTION:
XS GIS Cut Line= 3
      2597615.78     13437580.16      2596867.11     13436950.85
      2595141.89      13435865.8
#Sta/Elev= 30
  4008.5   66.75  4051.8   66.35  4148.2   58.93  4302.7    44.4  4474.1   27.71
  4553.6   24.74  4687.4   24.27  4765.5   25.55  4894.8   24.06  4895.3   23.56
  4919.8   24.06  5043.3   25.24  5049.2   24.25  5058.6   25.88  5085.7   26.42
    5101   24.97  5158.7   26.18  5242.6   25.64  5422.6   25.36  5645.1   28.48
  5687.5    27.2  5768.7   29.63  5964.9   30.17  6116.2   30.46  6190.2      32
  6231.6   31.95  6351.9   36.46  6631.1   43.33  6748.5   48.52  7024.6   65.91
#Mann= 12 ,-1 , 0
  4008.5     .07       0  4051.8     .12       0  4148.2     .07       0
  4302.7     .12       0  4553.6      .1       0  4894.8     .05       0
  4919.8      .1       0  5242.6     .07       0  5422.6     .12       0
  5964.9      .1       0  6190.2     .07       0  6351.9     .05       0
Bank Sta=4894.8,4919.8
XS Rating Curve= 0 ,0
Exp/Cntr=0.3,0.1

Type RM Length L Ch R = 1 ,69531   ,518,518,518
BEGIN DESCRIPTION:
TRIB 2 TO GUADALUPE RIVER 41.0
END DESCRIPTION:
XS GIS Cut Line= 3
      2597674.97     13437274.98        2596975.       13436775.
      2595374.99     13435324.99
#Sta/Elev= 30
  4122.8   65.59  4171.9   64.71  4245.7   59.77  4417.7   40.16  4466.9   36.43
  4552.9   25.39  4580.1   24.91  4788.8   25.59    4811   24.07  4904.3   24.95
  5012.7   23.02  5013.2   22.52  5037.8   23.02  5206.8   25.39    5280   24.03
  5343.2   25.67    5401   23.81    5422   25.25  5559.5   24.91    6066   27.95
  6122.8   26.99  6331.5   31.47  6483.5   36.31  6612.8   41.16  6760.1   46.28
    6781   42.87  6795.2   47.24  6802.7   47.77  6986.5   52.49  7142.3    60.7
#Mann= 10 ,-1 , 0
  4122.8     .12       0  4580.1      .1       0  5012.7     .05       0
  5037.8      .1       0  5206.8     .12       0  5343.2     .07       0
  5559.5     .12       0  6331.5      .1       0  6483.5     .05       0
  6612.8     .07       0
Bank Sta=5012.7,5037.8
XS Rating Curve= 0 ,0
Exp/Cntr=0.3,0.1

Type RM Length L Ch R = 1 ,69013   ,1084,1084,1084
BEGIN DESCRIPTION:
TRIB 2 TO GUADALUPE RIVER 40.0
END DESCRIPTION:
XS GIS Cut Line= 3
        2597775.       13437125.        2596975.       13436425.
        2595525.       13434825.
#Sta/Elev= 30
  3918.8   66.27  4089.2   56.39  4152.8   48.62  4216.4   44.71  4386.2   28.05
  4535.5   24.71  4792.3   25.38  4862.4   24.56  4905.3    24.5  5153.2   22.75
  5153.7   22.25  5178.7   22.75  5251.1   24.87  5444.6   23.43    5612   25.52
  5661.4   23.31  5705.2   26.12  6188.7   27.34  6258.7   27.84  6330.7   29.02
  6355.5    31.6    6398   44.43    6419    42.2  6496.8   41.59  6709.2   40.89
  6772.5   43.05  6829.9   45.25  6857.7   51.09  6879.2   50.03  7141.1   65.74
#Mann= 14 ,-1 , 0
  3918.8     .12       0  4535.5      .1       0  4792.3     .12       0
  4862.4      .1       0  4905.3     .12       0  5153.2     .05       0
  5178.7     .12       0  5444.6      .1       0  5705.2     .12       0
  6188.7      .1       0  6258.7     .12       0  6330.7    .035       0
  6496.8     .07       0  6772.5     .05       0
Bank Sta=5153.2,5178.7
XS Rating Curve= 0 ,0
Exp/Cntr=0.3,0.1