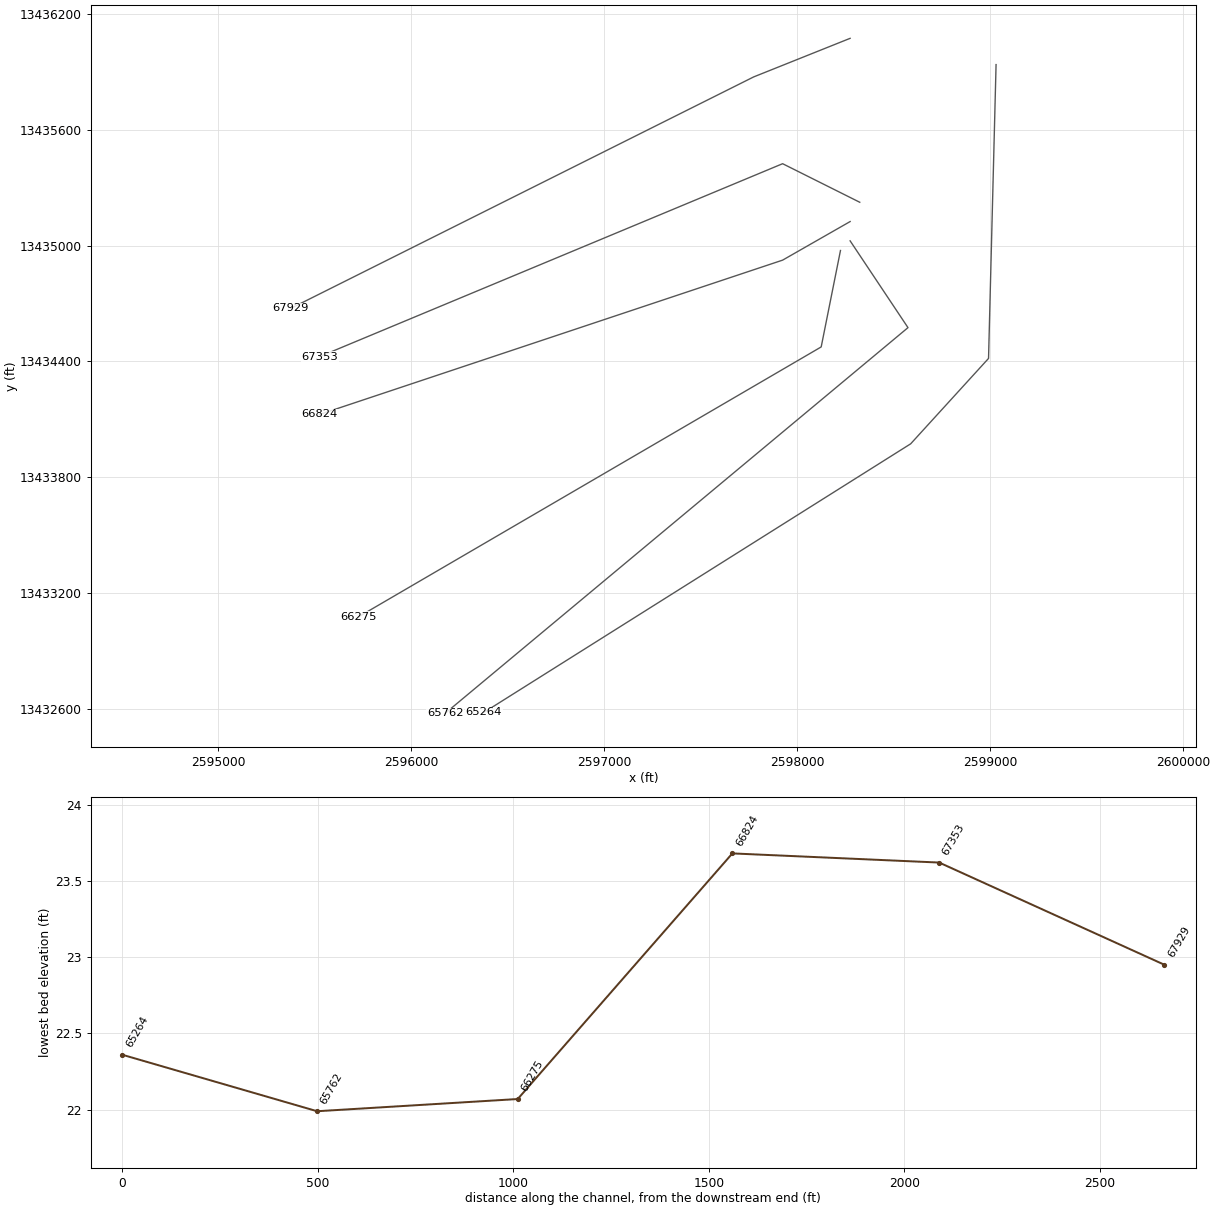
HEC-RAS study TRIB 2 TO GUADALUPE RIVER.prj: TRIB 2 TO GUADALUPE RIVER Base Level Engineering

--- TRIB 2 TO GUADALUPE RIVER.g01 (geometry) --- (continued)

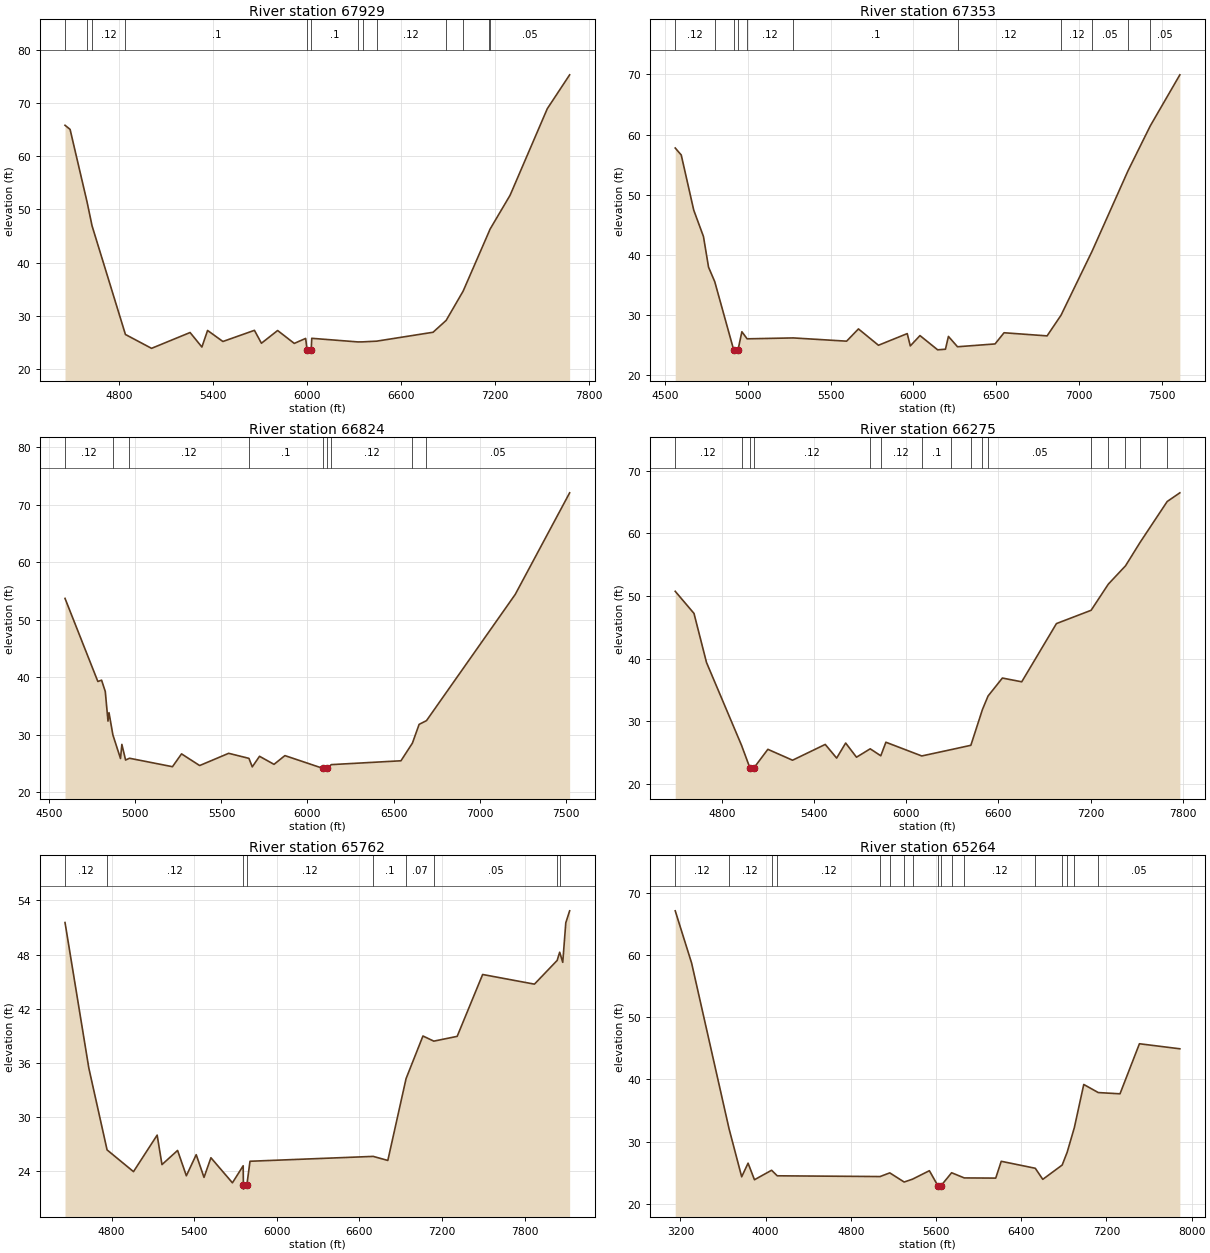
Type RM Length L Ch R = 1 ,67929   ,576,576,576
BEGIN DESCRIPTION:
TRIB 2 TO GUADALUPE RIVER 39.0
END DESCRIPTION:
XS GIS Cut Line= 3
      2598274.96     13436074.98        2597775.       13435875.
      2595374.96     13434674.98
#Sta/Elev= 30
  4455.2   65.85  4487.5   65.08  4595.5   51.47  4627.8   46.92  4840.9   26.46
  5007.6   23.85  5253.6   26.83  5329.1    24.1  5365.4   27.22  5463.2   25.14
  5664.5   27.24  5709.2   24.81  5812.6   27.21  5918.8   24.78  5991.5   25.72
  6001.1   23.45  6001.6   22.95  6026.6   23.45  6030.6   25.74  6325.3   25.06
  6355.2   25.07  6444.2    25.2  6804.9   26.88  6888.5   29.11  6996.9   34.62
  7163.5   45.91    7168   46.25  7296.8   52.68  7534.4   68.98    7677   75.35
#Mann= 13 ,-1 , 0
  4455.2     .12       0  4595.5    .035       0  4627.8     .12       0
  4840.9      .1       0  6001.1     .05       0  6026.6      .1       0
  6325.3     .12       0  6355.2      .1       0  6444.2     .12       0
  6888.5     .12       0  6996.9     .05       0  7163.5     .07       0
    7168     .05       0
Bank Sta=6001.1,6026.6
XS Rating Curve= 0 ,0
Exp/Cntr=0.3,0.1

Type RM Length L Ch R = 1 ,67353   ,529,529,529
BEGIN DESCRIPTION:
TRIB 2 TO GUADALUPE RIVER 38.0
END DESCRIPTION:
XS GIS Cut Line= 3
      2598324.96     13435225.02        2597925.       13435425.
      2595524.97     13434424.99
#Sta/Elev= 30
  4562.3   57.76  4598.6    56.6  4674.1   47.42  4732.8   43.03  4763.5   37.93
  4800.9   35.52  4915.7   24.12  4916.2   23.62  4941.2   24.12  4964.8   27.18
  4996.6      26  5275.7   26.15  5597.2   25.61  5668.7   27.65  5789.5   24.93
  5963.3   26.87  5981.8   24.82  6040.3   26.54    6147   24.17  6194.1   24.27
    6212    26.4  6266.9   24.68  6493.6   25.15  6547.8   27.01  6807.8   26.49
  6891.8   29.92  7080.2   40.62    7297      54    7431   61.45  7609.5   69.94
#Mann= 11 ,-1 , 0
  4562.3     .12       0  4800.9    .035       0  4915.7     .05       0
  4941.2    .035       0  4996.6     .12       0  5275.7      .1       0
  6266.9     .12       0  6891.8     .12       0  7080.2     .05       0
    7297     .07       0    7431     .05       0
Bank Sta=4915.7,4941.2
XS Rating Curve= 0 ,0
Exp/Cntr=0.3,0.1

Type RM Length L Ch R = 1 ,66824   ,549,549,549
BEGIN DESCRIPTION:
TRIB 2 TO GUADALUPE RIVER 37.0
END DESCRIPTION:
XS GIS Cut Line= 3
      2598275.02     13435125.01        2597925.       13434925.
      2595524.96     13434124.99
#Sta/Elev= 30
  4590.8   53.72  4781.6   39.27  4803.2    39.5  4824.8   37.53  4840.6   32.38
  4846.4   33.85    4869   29.98  4913.3   25.87  4921.2   28.33  4942.8   25.61
  4965.4   25.92  5215.3   24.45    5268   26.68  5373.4   24.65  5542.1   26.78
  5659.8    25.9  5679.1   24.42  5721.3   26.26  5805.6   24.86  5868.8   26.38
    6088   24.18  6088.5   23.68  6113.5   24.18  6138.5   24.81  6543.4   25.48
  6609.9   28.55  6648.9   31.81  6691.7   32.46  7207.5   54.41  7523.8   72.08
#Mann= 9 ,-1 , 0
  4590.8     .12       0    4869    .035       0  4965.4     .12       0
  5659.8      .1       0    6088     .05       0  6113.5      .1       0
  6138.5     .12       0  6609.9     .12       0  6691.7     .05       0
Bank Sta=6088,6113.5
XS Rating Curve= 0 ,0
Exp/Cntr=0.3,0.1

Type RM Length L Ch R = 1 ,66275   ,513,513,513
BEGIN DESCRIPTION:
TRIB 2 TO GUADALUPE RIVER 36.0
END DESCRIPTION:
XS GIS Cut Line= 3
      2598224.99     13434974.95        2598125.       13434475.
      2595725.04     13433075.02
#Sta/Elev= 30
  4493.8   50.76  4616.1   47.23  4697.7    39.4  4925.7    26.2  4980.7   22.57
  4981.2   22.07  5006.3   22.57  5097.5   25.55  5258.3   23.81  5471.3   26.33
  5545.7   24.15  5604.4   26.55  5675.1   24.29  5764.4   25.63  5833.3   24.52
  5866.6   26.68  6100.3   24.49  6293.4   25.51  6420.2   26.19  6495.6   31.89
  6532.2   34.05  6625.7   36.92  6751.8   36.32    6978   45.61  7203.9   47.73
  7315.9    51.9  7427.9   54.82  7523.4   58.58  7699.8   65.09  7782.1   66.47
#Mann= 16 ,-1 , 0
  4493.8     .12       0  4925.7     .12       0  4980.7     .05       0
  5006.3     .12       0  5764.4      .1       0  5833.3     .12       0
  6100.3      .1       0  6293.4     .12       0  6420.2     .12       0
  6495.6     .12       0  6532.2     .05       0  7203.9    .035       0
  7315.9     .05       0  7427.9     .07       0  7523.4    .035       0
  7699.8     .07       0
Bank Sta=4980.7,5006.3
XS Rating Curve= 0 ,0
Exp/Cntr=0.3,0.1

Type RM Length L Ch R = 1 ,65762   ,498,498,498
BEGIN DESCRIPTION:
TRIB 2 TO GUADALUPE RIVER 35.0
END DESCRIPTION:
XS GIS Cut Line= 3
      2598274.99     13435025.01        2598575.       13434575.
      2596175.04     13432575.03
#Sta/Elev= 30
  4461.7   51.55  4634.5   35.42  4767.1   26.34    4959   23.93  5130.8   27.98
  5165.9   24.71  5279.2   26.28  5342.9   23.47  5414.5   25.81  5471.2   23.29
  5521.3   25.47  5677.5   22.69  5755.6   24.58  5757.1   22.49  5757.6   21.99
  5782.7   22.49  5805.1   25.08  6699.9   25.62  6806.1   25.17  6938.5   34.24
  7061.2   38.97  7140.1    38.4  7309.8   38.93  7494.7   45.79  7870.9   44.72
  8035.9   47.35  8054.3   48.26  8076.5   47.14  8098.7   51.53  8126.6   52.85
#Mann= 9 ,-1 , 0
  4461.7     .12       0  4767.1     .12       0  5757.1     .05       0
  5782.7     .12       0  6699.9      .1       0  6938.5     .07       0
  7140.1     .05       0  8035.9    .035       0  8054.3     .05       0
Bank Sta=5757.1,5782.7
XS Rating Curve= 0 ,0
Exp/Cntr=0.3,0.1

Type RM Length L Ch R = 1 ,65264   ,0,0,0
BEGIN DESCRIPTION:
Mapping XS bfad795b
END DESCRIPTION:
XS GIS Cut Line= 4
      2599031.72      13435938.8      2598992.66      13434415.4
      2598589.01     13433972.69      2596375.89     13432579.73
#Sta/Elev= 30
  3151.6   67.06  3305.5   58.67  3656.4    32.1  3775.6   24.34  3835.6   26.53
  3895.6   23.87  4056.4   25.39  4109.4    24.5    5075   24.38    5166   24.97
  5301.2    23.5  5379.7   23.96  5537.9   25.32  5619.3   22.86  5619.8   22.36
  5644.9   22.86  5746.6   24.99  5865.5   24.16  6160.8   24.13  6212.6   26.83
  6532.3   25.71  6602.7   23.93  6784.8   26.23  6831.3   28.27    6899   32.24
  6987.4   39.17  7123.4   37.87  7327.7   37.67  7510.1   45.71  7889.6    44.9
#Mann= 17 ,-1 , 0
  3151.6     .12       0  3656.4     .12       0  4056.4      .1       0
  4109.4     .12       0    5075      .1       0    5166     .12       0
  5301.2      .1       0  5379.7     .12       0  5619.3     .05       0
  5644.9     .12       0  5746.6      .1       0  5865.5     .12       0
  6532.3      .1       0  6784.8     .07       0  6831.3     .05       0
    6899     .07       0  7123.4     .05       0
Bank Sta=5619.3,5644.9
XS Rating Curve= 0 ,0
Exp/Cntr=0.3,0.1

Chan Stop Cuts=-1
Use User Specified Reach Order=0
Composite Channel Slope=5