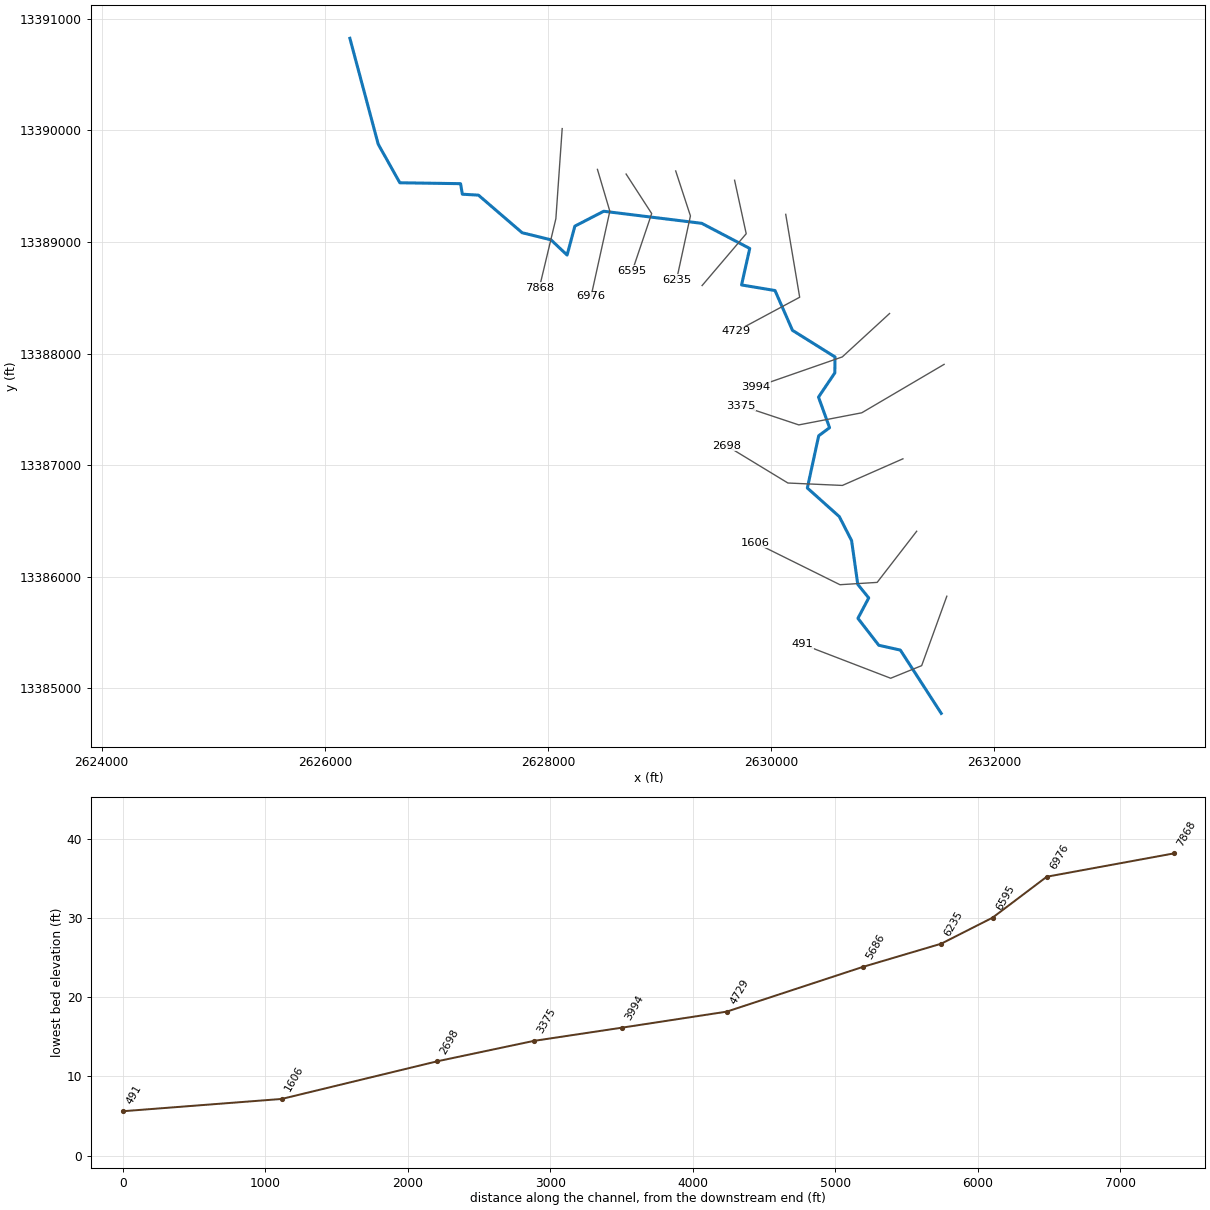
--- TRIB 2 TO KUY CREEK.prj (project) ---

Proj Title=TRIB 2 TO KUY CREEK Base Level Engineering
Current Plan=p01
Default Exp/Contr=0.3,0.1
English Units
Geom File=g01
Flow File=f01
Plan File=p01
Y Axis Title=Elevation
X Axis Title(PF)=Main Channel Distance
X Axis Title(XS)=Station
BEGIN DESCRIPTION:
TRIB 2 TO KUY CREEK
END DESCRIPTION:
DSS Export Rating Curves= 0
DSS Export Rating Curve Sorted= 0
DSS Export Volume Flow Curves= 0
DXF OffsetX= 0
DXF OffsetY= 0
DXF ScaleX= 1
DXF ScaleY= 10

--- TRIB 2 TO KUY CREEK.p01 (plan) ---

Plan Title=Multiple Run
Short Identifier=Multiple
Geom File=g01
Flow File=f01
Subcritical Flow
K Sum by GR= 0
Std Step Tol= 0.01
Critical Tol= 0.01
Num of Std Step Trials= 20
Max Error Tol= 0.3
Flow Tol Ratio= 0.001
Split Flow NTrial= 30
Split Flow Tol= 0.02
Split Flow Ratio= 0.02
Log Output Level= 0
Friction Slope Method= 1
Unsteady Friction Slope Method= 2
Unsteady Bridges Friction Slope Method= 1
Parabolic Critical Depth
Global Vel Dist=  1 , 1 , 1
Global Log Level= 0
CheckData=True
Encroach Param= -1, 0, 0, 0
BEGIN DESCRIPTION:
Multiple Run
END DESCRIPTION:

--- TRIB 2 TO KUY CREEK.f01 (steady flow) ---

Flow Title=Multiple
Number of Profiles=7
Profile Names=10-year,25-year,50-year,1pct_min,100-year,1pct_plu,500-year
River Rch & RM= TRIB 2 TO KUY CR,Reach-1,7868
     730    1136    1490     944    1883    3756    2971
River Rch & RM= TRIB 2 TO KUY CR,Reach-1,3375
     823    1291    1701    1083    2160    4310    3442
Boundary for River Rch & Prof#=TRIB 2 TO KUY CR,Reach-1,1
Up Type=0
Dn Type=3
Dn Slope=0.005
Boundary for River Rch & Prof#=TRIB 2 TO KUY CR,Reach-1,2
Up Type=0
Dn Type=3
Dn Slope=0.005
Boundary for River Rch & Prof#=TRIB 2 TO KUY CR,Reach-1,3
Up Type=0
Dn Type=3
Dn Slope=0.005
Boundary for River Rch & Prof#=TRIB 2 TO KUY CR,Reach-1,4
Up Type=0
Dn Type=3
Dn Slope=0.005
Boundary for River Rch & Prof#=TRIB 2 TO KUY CR,Reach-1,5
Up Type=0
Dn Type=3
Dn Slope=0.005
Boundary for River Rch & Prof#=TRIB 2 TO KUY CR,Reach-1,6
Up Type=0
Dn Type=3
Dn Slope=0.005
Boundary for River Rch & Prof#=TRIB 2 TO KUY CR,Reach-1,7
Up Type=0
Dn Type=3
Dn Slope=0.005

--- TRIB 2 TO KUY CREEK.g01 (geometry) ---

Geom Title=Existing Conditions
Program Version=4.10

River Reach=TRIB 2 TO KUY CR,Reach-1
Reach XY= 30
        2626225.       13390825.      2626478.83     13389876.58
      2626672.54     13389530.46      2627216.82     13389522.44
        2627233.     13389428.01      2627377.44     13389419.53
      2627768.56     13389082.79      2628027.36     13389019.25
      2628171.64     13388882.43      2628241.37      13389141.7
      2628499.92      13389275.2      2629378.33     13389166.99
      2629808.71     13388941.71      2629735.28     13388614.84
      2630035.17     13388564.68      2630191.44     13388208.21
      2630573.03     13387969.33      2630571.26     13387826.56
      2630424.95     13387609.66      2630524.11     13387335.34
      2630426.64     13387263.17      2630324.93     13386794.99
       2630611.6      13386538.3      2630721.45     13386323.53
      2630777.08     13385930.86       2630875.1     13385809.64
      2630778.31     13385626.73       2630965.2     13385385.48
      2631158.55     13385342.14        2631525.       13384775.

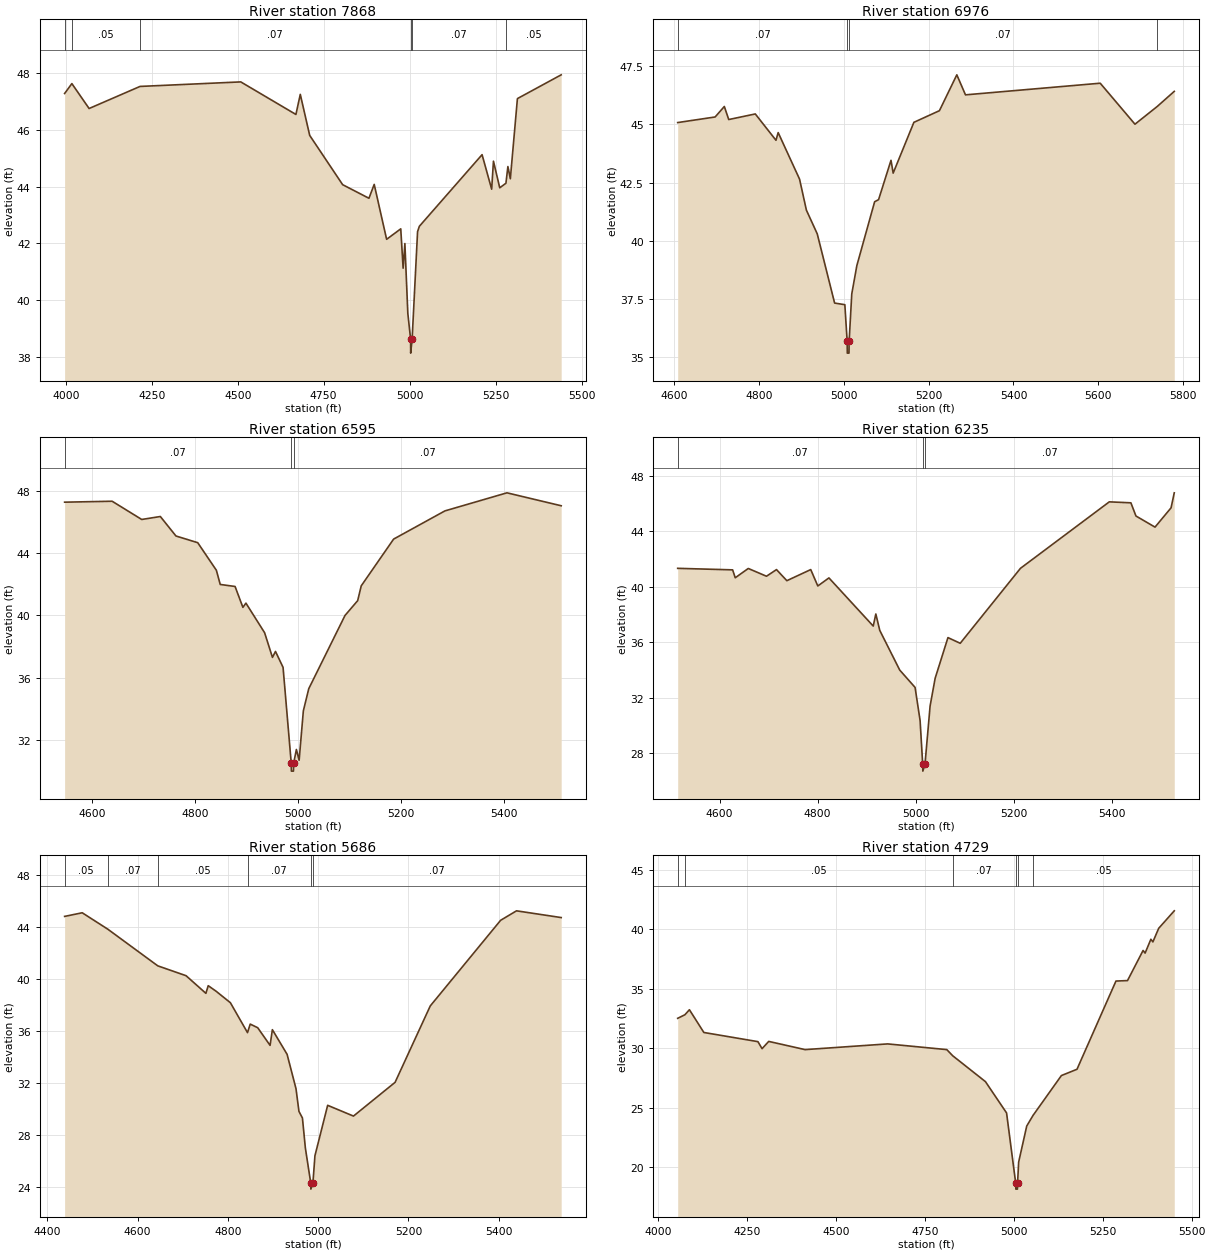
Type RM Length L Ch R = 1 ,7868    ,892,892,892
BEGIN DESCRIPTION:
Mapping XS e3929ec2
END DESCRIPTION:
XS GIS Cut Line= 3
      2628127.82     13390016.01      2628071.18     13389208.88
       2627923.5      13388591.2
#Sta/Elev= 30
  3996.6   47.29  4017.7   47.64  4067.8   46.76  4215.9   47.54  4508.9    47.7
  4669.3   46.55    4682   47.26  4709.4   45.81  4805.2   44.07  4881.7   43.59
    4897   44.08  4933.1   42.14  4974.2   42.51  4981.1   41.12  4986.2   41.99
  4994.8   39.52  5002.8   38.62  5003.1   38.12  5007.3   38.62  5023.1   42.41
  5028.3    42.6  5210.7   45.13  5238.6   43.91  5243.8    44.9  5262.1   43.96
  5280.1   44.12  5285.8   44.71  5292.9   44.28  5313.5   47.11  5440.8   47.95
#Mann= 6 ,-1 , 0
  3996.6    .035       0  4017.7     .05       0  4215.9     .07       0
  5002.8     .05       0  5007.3     .07       0  5280.1     .05       0
Bank Sta=5002.8,5007.3
XS Rating Curve= 0 ,0
Exp/Cntr=0.3,0.1

Type RM Length L Ch R = 1 ,6976    ,381,381,381
BEGIN DESCRIPTION:
Mapping XS 68a15073
END DESCRIPTION:
XS GIS Cut Line= 3
      2628443.71     13389650.38      2628554.83     13389275.36
      2628386.89     13388514.61
#Sta/Elev= 30
  4608.7   45.08  4696.9   45.32  4718.6   45.77    4729   45.21  4791.6   45.45
  4840.3   44.32  4845.5   44.65  4895.9   42.65    4912   41.32  4937.6    40.3
  4978.5   37.33  5002.6   37.26  5008.1   35.68  5008.4   35.18  5012.4   35.18
  5012.7   35.68  5018.9   37.72  5030.9   38.94  5072.8   41.68  5082.1   41.77
  5111.4   43.46  5116.5   42.91  5165.3   45.09  5225.5   45.59  5266.5   47.13
  5286.9   46.27  5604.4   46.77  5686.3   45.01  5738.7   45.77  5778.9   46.42
#Mann= 4 ,-1 , 0
  4608.7     .07       0  5008.1     .05       0  5012.7     .07       0
  5738.7     .05       0
Bank Sta=5008.1,5012.7
XS Rating Curve= 0 ,0
Exp/Cntr=0.3,0.1

Type RM Length L Ch R = 1 ,6595    ,360,360,360
BEGIN DESCRIPTION:
Mapping XS 01051176
END DESCRIPTION:
XS GIS Cut Line= 3
      2628700.67     13389608.69      2628929.83     13389254.53
      2628756.21      13388740.6
#Sta/Elev= 30
    4547   47.27  4639.3   47.33  4696.7   46.16  4732.9   46.35  4763.2    45.1
  4805.5   44.67  4841.7    42.9  4849.2   41.99    4878   41.86  4893.2   40.52
  4899.1   40.79  4935.4   38.89  4950.6   37.31  4956.5   37.69  4971.2   36.67
  4987.1   30.51  4987.4   30.01  4991.4   30.01  4991.7   30.51  4997.1    31.4
  5002.4   30.71  5010.6   33.88  5021.1    35.3  5091.5      40  5116.1   40.95
    5123    41.9  5185.9    44.9  5285.5   46.71    5406   47.87  5511.3   47.04
#Mann= 3 ,-1 , 0
    4547     .07       0  4987.1     .05       0  4991.7     .07       0
Bank Sta=4987.1,4991.7
XS Rating Curve= 0 ,0
Exp/Cntr=0.3,0.1

Type RM Length L Ch R = 1 ,6235    ,549,549,549
BEGIN DESCRIPTION:
Mapping XS 6f312d4b
END DESCRIPTION:
XS GIS Cut Line= 3
      2629145.12     13389636.43      2629277.05      13389233.7
      2629152.35     13388658.65
#Sta/Elev= 30
  4514.7   41.34  4626.7   41.23    4632   40.66  4658.6   41.33  4695.7   40.77
  4716.1   41.25  4737.2   40.45  4785.9   41.25  4800.3   40.07    4823   40.65
  4913.3   37.18  4918.6   38.05  4926.6   36.87  4967.3   34.01  4998.6   32.76
  5008.8   30.38  5014.1   27.23  5014.4   26.73  5018.8   27.23  5029.2   31.42
  5039.5   33.42  5065.6   36.35  5090.6   35.94  5213.4   41.34  5394.5   46.13
  5438.5   46.06  5448.8   45.11  5487.7   44.31  5520.4    45.7  5526.9   46.78
#Mann= 3 ,-1 , 0
  4514.7     .07       0  5014.1     .05       0  5018.8     .07       0
Bank Sta=5014.1,5018.8
XS Rating Curve= 0 ,0
Exp/Cntr=0.3,0.1

Type RM Length L Ch R = 1 ,5686    ,957,957,957
BEGIN DESCRIPTION:
Mapping XS 6002d6bd
END DESCRIPTION:
XS GIS Cut Line= 3
      2629672.89     13389553.14      2629777.05     13389073.97
      2629381.76     13388609.33
#Sta/Elev= 30
  4438.2   44.83  4477.2   45.11  4533.7   43.85  4644.6   41.02  4707.3   40.26
  4751.3    38.9  4756.4   39.49    4774   39.06  4805.5   38.18  4843.5   35.87
  4849.5   36.53  4866.1   36.25  4893.5   34.89  4898.6    36.1  4931.2    34.2
  4950.9   31.56  4957.5    29.8  4965.2   29.29  4971.7   26.98  4983.5   24.31
  4983.9   23.81  4988.5   24.31  4992.9   26.38  5021.1   30.27  5078.3   29.44
  5170.5   32.04  5248.5   37.93  5404.4   44.53  5439.6   45.26  5538.6   44.74
#Mann= 6 ,-1 , 0
  4438.2     .05       0  4533.7     .07       0  4644.6     .05       0
  4843.5     .07       0  4983.5     .05       0  4988.5     .07       0
Bank Sta=4983.5,4988.5
XS Rating Curve= 0 ,0
Exp/Cntr=0.3,0.1

Type RM Length L Ch R = 1 ,4729    ,735,735,735
BEGIN DESCRIPTION:
Mapping XS 5fe9900a
END DESCRIPTION:
XS GIS Cut Line= 3
      2630131.22     13389247.57      2630256.22     13388504.53
      2629689.35     13388200.36
#Sta/Elev= 30
  4054.3   32.51  4074.6   32.81  4087.3   33.23  4127.9   31.32    4280   30.55
  4291.6   29.96  4310.4   30.57  4412.7   29.88  4644.9   30.36  4811.3   29.88
  4827.7   29.37    4920   27.19  4979.4   24.56  5005.1   18.66  5005.5   18.16
  5009.9   18.16  5010.3   18.66  5013.4   20.43  5036.1   23.46  5053.8   24.35
  5133.6    27.7  5177.5   28.23  5287.1   35.64  5319.6   35.68  5363.4   38.21
  5369.1   37.99  5385.3   39.15    5391   38.93  5407.3   40.07  5451.1   41.54
#Mann= 6 ,-1 , 0
  4054.3     .07       0  4074.6     .05       0  4827.7     .07       0
  5005.1     .05       0  5010.3     .07       0  5053.8     .05       0
Bank Sta=5005.1,5010.3
XS Rating Curve= 0 ,0
Exp/Cntr=0.3,0.1

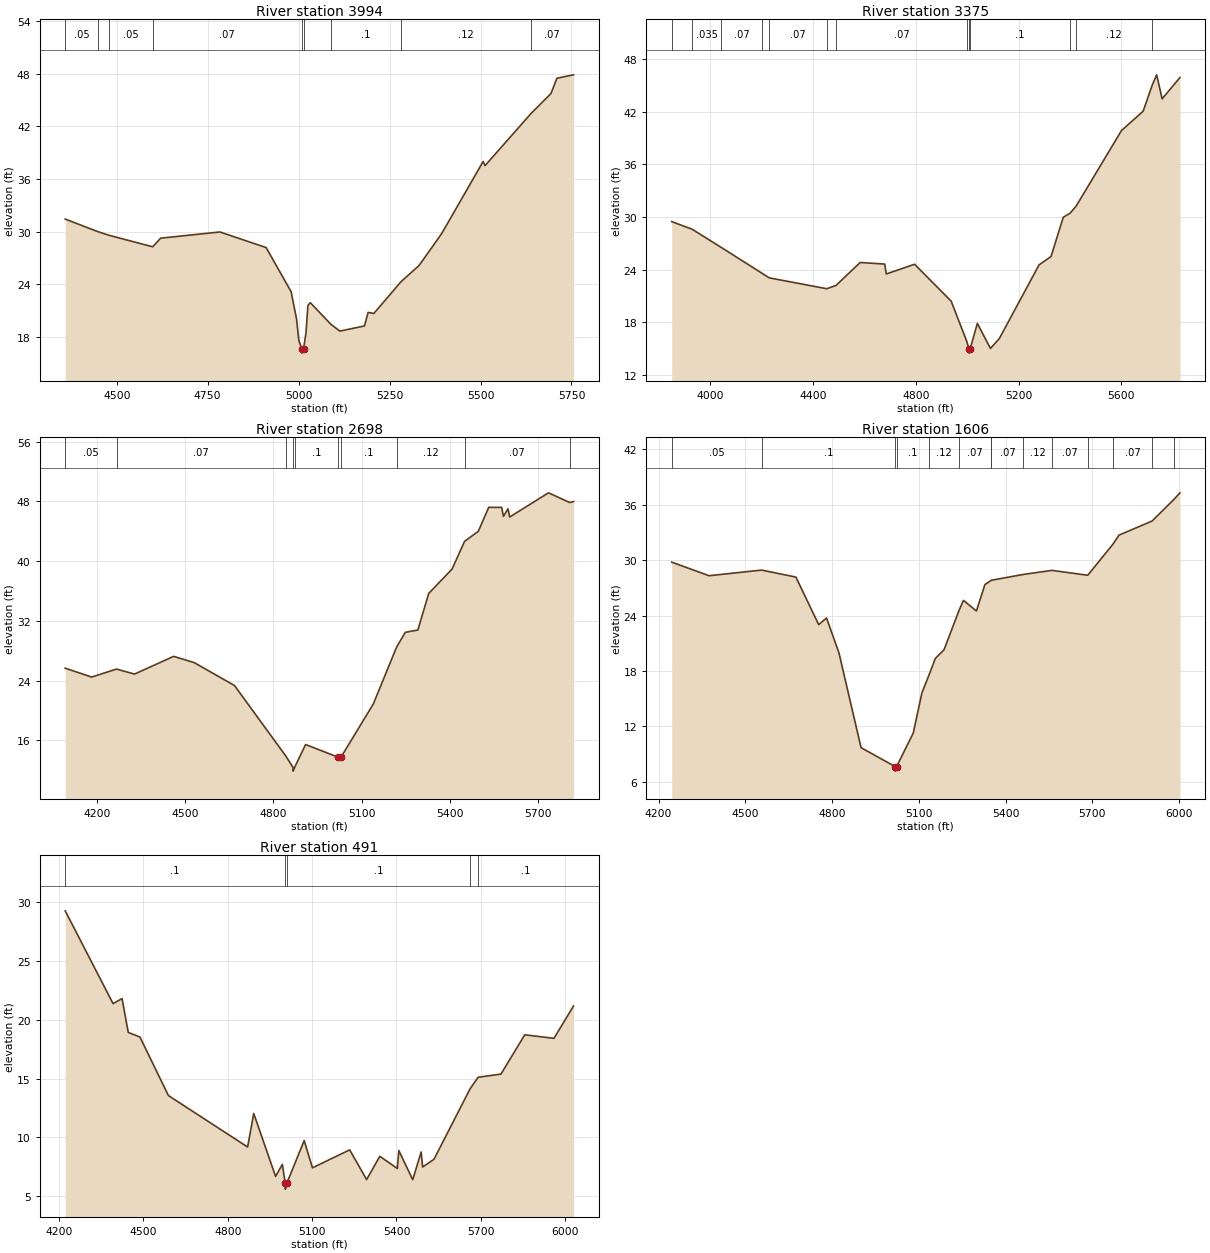
Type RM Length L Ch R = 1 ,3994    ,619,619,619
BEGIN DESCRIPTION:
Mapping XS f21dd8ab
END DESCRIPTION:
XS GIS Cut Line= 3
      2631061.78      13388358.7      2630638.16     13387969.81
      2629861.84     13387699.48
#Sta/Elev= 30
  4358.5   31.42  4448.5   29.98    4480   29.56  4598.9   28.26  4620.8   29.24
  4783.6   29.95  4910.7   28.17  4979.3   23.15  4994.5      20  5000.4   17.65
  5008.4   16.64  5008.8   16.14  5013.6   16.64  5020.3   18.45  5025.6   21.59
  5032.2   21.89  5088.9   19.42  5113.5   18.65    5181   19.24    5191   20.78
  5206.8   20.66  5281.4   24.28  5331.1   26.13  5393.3   29.77  5507.1   37.98
  5512.4   37.51  5638.3   43.43  5693.6   45.73  5709.9   47.47  5755.6   47.86
#Mann= 9 ,-1 , 0
  4358.5     .05       0  4448.5    .035       0    4480     .05       0
  4598.9     .07       0  5008.4     .05       0  5013.6     .07       0
  5088.9      .1       0  5281.4     .12       0  5638.3     .07       0
Bank Sta=5008.4,5013.6
XS Rating Curve= 0 ,0
Exp/Cntr=0.3,0.1

Type RM Length L Ch R = 1 ,3375    ,677,677,677
BEGIN DESCRIPTION:
Mapping XS 7fcdc6fd
END DESCRIPTION:
XS GIS Cut Line= 4
       2631550.6     13387902.98      2630812.73     13387468.94
      2630248.49     13387360.43      2629728.84     13387533.65
#Sta/Elev= 30
    3850   29.46  3929.1    28.6  4043.9    26.5  4200.2    23.6  4229.7   23.05
  4453.5   21.81  4489.4   22.18  4583.6    24.8  4679.3   24.62  4685.1   23.49
  4795.4    24.6    4938   20.39  4998.5   15.81  5006.6   14.97    5007   14.47
  5011.8   14.97  5039.8   17.86  5090.7      15  5125.2   16.13  5279.9   24.53
  5326.5   25.48    5374   29.95  5400.7   30.42  5424.5   31.24  5600.7   39.84
  5684.9   42.04    5720   44.99  5737.6   46.19  5758.8   43.45  5828.4   45.89
#Mann= 13 ,-1 , 0
    3850     .07       0  3929.1    .035       0  4043.9     .07       0
  4200.2     .05       0  4229.7     .07       0  4453.5     .05       0
  4489.4     .07       0  4998.5      .1       0  5006.6     .05       0
  5011.8      .1       0  5400.7     .07       0  5424.5     .12       0
    5720     .07       0
Bank Sta=5006.6,5011.8
XS Rating Curve= 0 ,0
Exp/Cntr=0.3,0.1

Type RM Length L Ch R = 1 ,2698    ,1092,1092,1092
BEGIN DESCRIPTION:
Mapping XS 7c603857
END DESCRIPTION:
XS GIS Cut Line= 4
      2631181.62      13387056.6      2630639.12      13386817.9
      2630150.84      13386839.6       2629598.7     13387175.21
#Sta/Elev= 30
  4092.4   25.68  4182.4   24.49  4266.8   25.56  4327.9   24.89    4461   27.26
    4531   26.42  4667.7   23.36  4842.2   13.92  4866.6    12.4  4867.1    11.9
  4872.1    12.4  4909.4   15.46  5019.5   13.77  5029.6   13.76  5139.7    20.9
  5218.8   28.51  5248.3   30.48    5291   30.79  5327.8   35.68  5407.3   38.95
  5449.7   42.66  5496.4      44  5531.8   47.21  5575.8    47.2  5581.7      46
  5597.2   47.01    5603   45.91  5734.8   49.15  5807.3   47.85    5820   47.99
#Mann= 10 ,-1 , 0
  4092.4     .05       0  4266.8     .07       0  4842.2      .1       0
  4866.6     .07       0  4872.1      .1       0  5019.5     .05       0
  5029.6      .1       0  5218.8     .12       0  5449.7     .07       0
  5807.3     .05       0
Bank Sta=5019.5,5029.6
XS Rating Curve= 0 ,0
Exp/Cntr=0.3,0.1

Type RM Length L Ch R = 1 ,1606    ,1115,1115,1115
BEGIN DESCRIPTION:
Mapping XS 42651bcc
END DESCRIPTION:
XS GIS Cut Line= 4
      2631304.81     13386407.28      2630950.66     13385948.97
      2630617.33     13385928.14      2629860.41     13386303.13
#Sta/Elev= 30
  4245.5   29.79  4374.8   28.32  4556.6   28.93  4675.2   28.17  4753.9   23.02
  4781.1   23.74    4824   19.96  4900.5    9.69  5017.9    7.65  5018.4    7.15
  5023.5    7.65  5080.9   11.27  5110.9   15.63  5134.1   17.45  5157.3   19.36
  5187.3   20.29  5239.8    24.6  5254.6   25.65  5299.4    24.5  5328.7   27.36
  5350.2   27.81    5351   27.83  5462.1   28.46  5560.8    28.9  5684.4   28.37
  5771.4   31.73  5792.7   32.72  5906.7   34.24  5981.9   36.57  6003.4    37.3
#Mann= 14 ,-1 , 0
  4245.5     .05       0  4556.6      .1       0  5017.9     .05       0
  5023.5      .1       0  5134.1     .12       0  5239.8     .07       0
  5350.2     .12       0    5351     .07       0  5462.1     .12       0
  5560.8     .07       0  5684.4     .12       0  5771.4     .07       0
  5906.7     .12       0  5981.9     .07       0
Bank Sta=5017.9,5023.5
XS Rating Curve= 0 ,0
Exp/Cntr=0.3,0.1

Type RM Length L Ch R = 1 ,491     ,0,0,0
BEGIN DESCRIPTION:
TRIB 2 TO KUY CREEK 1.0
END DESCRIPTION:
XS GIS Cut Line= 4
        2631575.     13385824.99      2631349.55     13385202.74
      2631071.78     13385089.88      2630281.85     13385393.71
#Sta/Elev= 30
  4221.7   29.26  4391.9   21.37  4423.8    21.8  4446.1   18.92  4487.6   18.53
  4588.6   13.56  4870.5    9.18  4892.3   12.03    4970    6.68    4994     7.7
  5004.3     6.1  5004.8     5.6    5010     6.1  5071.7    9.73  5101.1    7.41
  5233.5    8.94  5293.8    6.41  5340.6    8.39    5403    7.36  5408.4    8.88
  5457.7     6.4  5487.7    8.76    5493    7.48  5533.5    8.14    5662   14.14
  5690.4   15.11  5771.6   15.38  5856.2   18.72  5960.2   18.42  6029.7   21.17
#Mann= 5 ,-1 , 0
  4221.7      .1       0  5004.3     .05       0    5010      .1       0
    5662     .12       0  5690.4      .1       0
Bank Sta=5004.3,5010
XS Rating Curve= 0 ,0
Exp/Cntr=0.3,0.1

Chan Stop Cuts=-1
Use User Specified Reach Order=0
Composite Channel Slope=5