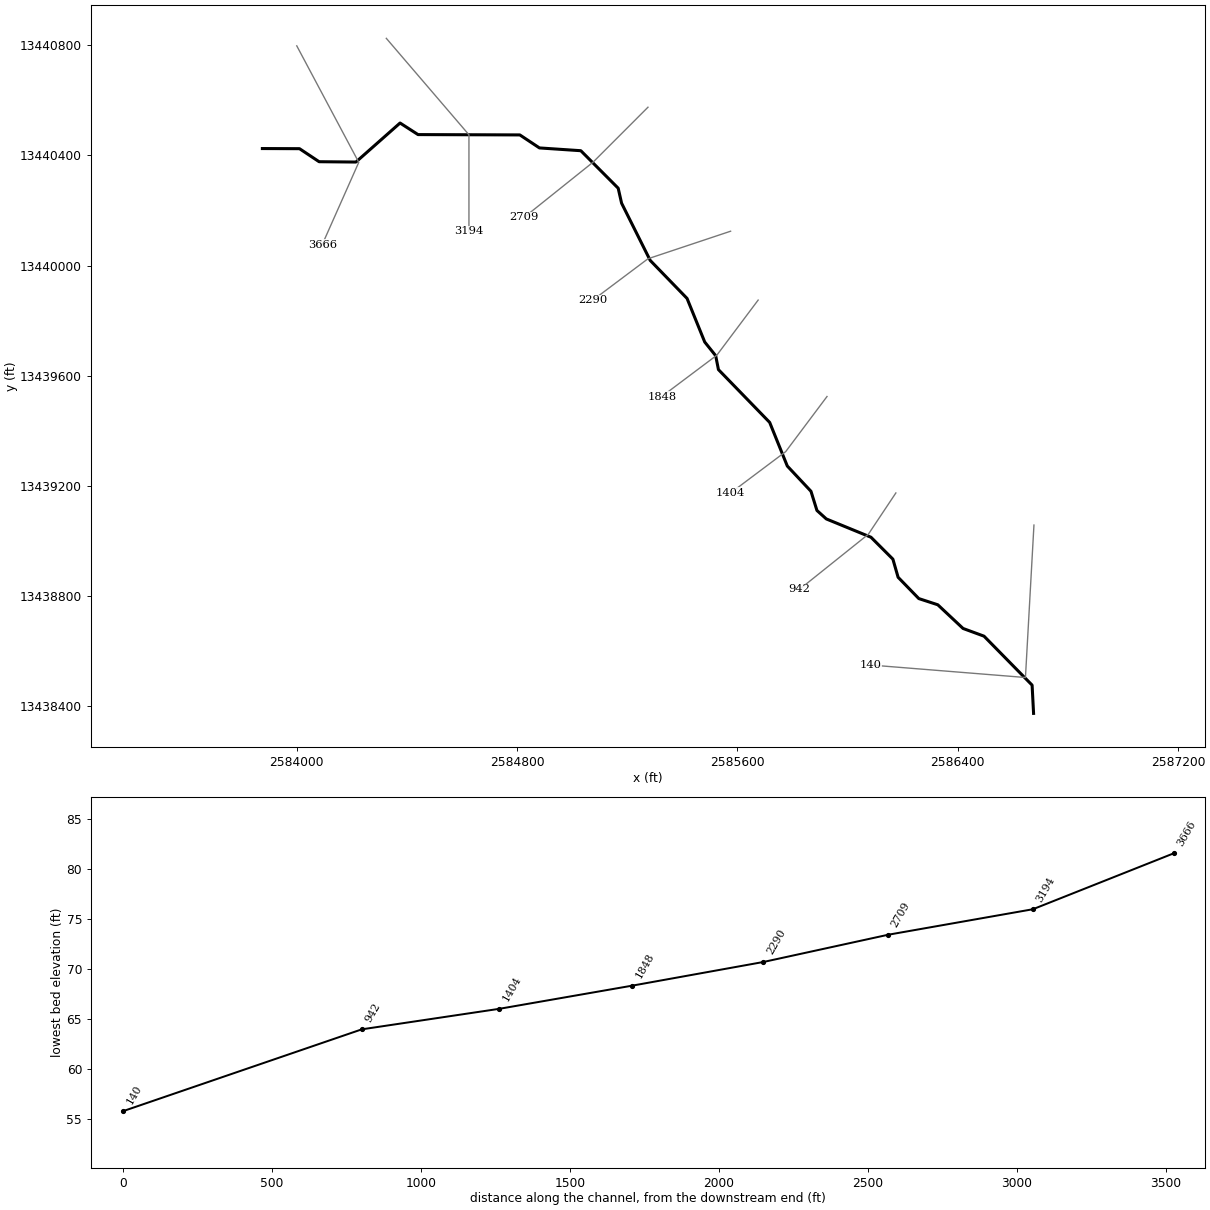
--- TRIB 2_10 TO GUADALUPE RIVER.prj (project) ---

Proj Title=TRIB 2_10 TO GUADALUPE RIVER Base Level Engineering
Current Plan=p01
Default Exp/Contr=0.3,0.1
English Units
Geom File=g01
Flow File=f01
Plan File=p01
Y Axis Title=Elevation
X Axis Title(PF)=Main Channel Distance
X Axis Title(XS)=Station
BEGIN DESCRIPTION:
TRIB 2_10 TO GUADALUPE RIVER
END DESCRIPTION:
DSS Export Rating Curves= 0
DSS Export Rating Curve Sorted= 0
DSS Export Volume Flow Curves= 0
DXF OffsetX= 0
DXF OffsetY= 0
DXF ScaleX= 1
DXF ScaleY= 10

--- TRIB 2_10 TO GUADALUPE RIVER.p01 (plan) ---

Plan Title=Multiple Run
Short Identifier=Multiple
Geom File=g01
Flow File=f01
Subcritical Flow
K Sum by GR= 0
Std Step Tol= 0.01
Critical Tol= 0.01
Num of Std Step Trials= 20
Max Error Tol= 0.3
Flow Tol Ratio= 0.001
Split Flow NTrial= 30
Split Flow Tol= 0.02
Split Flow Ratio= 0.02
Log Output Level= 0
Friction Slope Method= 1
Unsteady Friction Slope Method= 2
Unsteady Bridges Friction Slope Method= 1
Parabolic Critical Depth
Global Vel Dist=  1 , 1 , 1
Global Log Level= 0
CheckData=True
Encroach Param= -1, 0, 0, 0
BEGIN DESCRIPTION:
Multiple Run
END DESCRIPTION:

--- TRIB 2_10 TO GUADALUPE RIVER.f01 (steady flow) ---

Flow Title=Multiple
Number of Profiles=7
Profile Names=10-year,25-year,50-year,1pct_min,100-year,1pct_plu,500-year
River Rch & RM= TRIB 2_10 TO GUA,Reach-1,3666
     456     690     887     551    1099    2194    1669
River Rch & RM= TRIB 2_10 TO GUA,Reach-1,3194
     594     918    1198     755    1506    3005    2353
River Rch & RM= TRIB 2_10 TO GUA,Reach-1,2290
     729    1148    1517     968    1932    3855    3098
Boundary for River Rch & Prof#=TRIB 2_10 TO GUA,Reach-1,1
Up Type=0
Dn Type=3
Dn Slope=0.005
Boundary for River Rch & Prof#=TRIB 2_10 TO GUA,Reach-1,2
Up Type=0
Dn Type=3
Dn Slope=0.005
Boundary for River Rch & Prof#=TRIB 2_10 TO GUA,Reach-1,3
Up Type=0
Dn Type=3
Dn Slope=0.005
Boundary for River Rch & Prof#=TRIB 2_10 TO GUA,Reach-1,4
Up Type=0
Dn Type=3
Dn Slope=0.005
Boundary for River Rch & Prof#=TRIB 2_10 TO GUA,Reach-1,5
Up Type=0
Dn Type=3
Dn Slope=0.005
Boundary for River Rch & Prof#=TRIB 2_10 TO GUA,Reach-1,6
Up Type=0
Dn Type=3
Dn Slope=0.005
Boundary for River Rch & Prof#=TRIB 2_10 TO GUA,Reach-1,7
Up Type=0
Dn Type=3
Dn Slope=0.005

--- TRIB 2_10 TO GUADALUPE RIVER.g01 (geometry) ---

Geom Title=Existing Conditions
Program Version=4.10

River Reach=TRIB 2_10 TO GUA,Reach-1
Reach XY= 30
        2583875.       13440425.      2584009.81     13440424.54
      2584080.94     13440377.25      2584214.56     13440376.04
       2584374.9     13440517.68      2584440.16     13440475.66
      2584809.78     13440474.48      2584880.94     13440427.27
      2585031.19     13440417.18      2585166.86     13440281.06
      2585179.19     13440226.74      2585283.14     13440018.94
      2585416.86     13439881.06      2585481.08      13439722.8
      2585520.81     13439673.26      2585530.83      13439622.7
      2585716.86     13439431.06      2585780.85     13439272.71
      2585866.82     13439181.02      2585888.48     13439111.44
      2585922.45     13439080.73       2586084.7     13439014.24
      2586164.23      13438934.7      2586183.15     13438868.94
      2586258.29     13438791.64      2586327.28     13438769.13
      2586418.96     13438683.18      2586495.09     13438655.21
      2586669.65      13438477.5        2586675.       13438375.

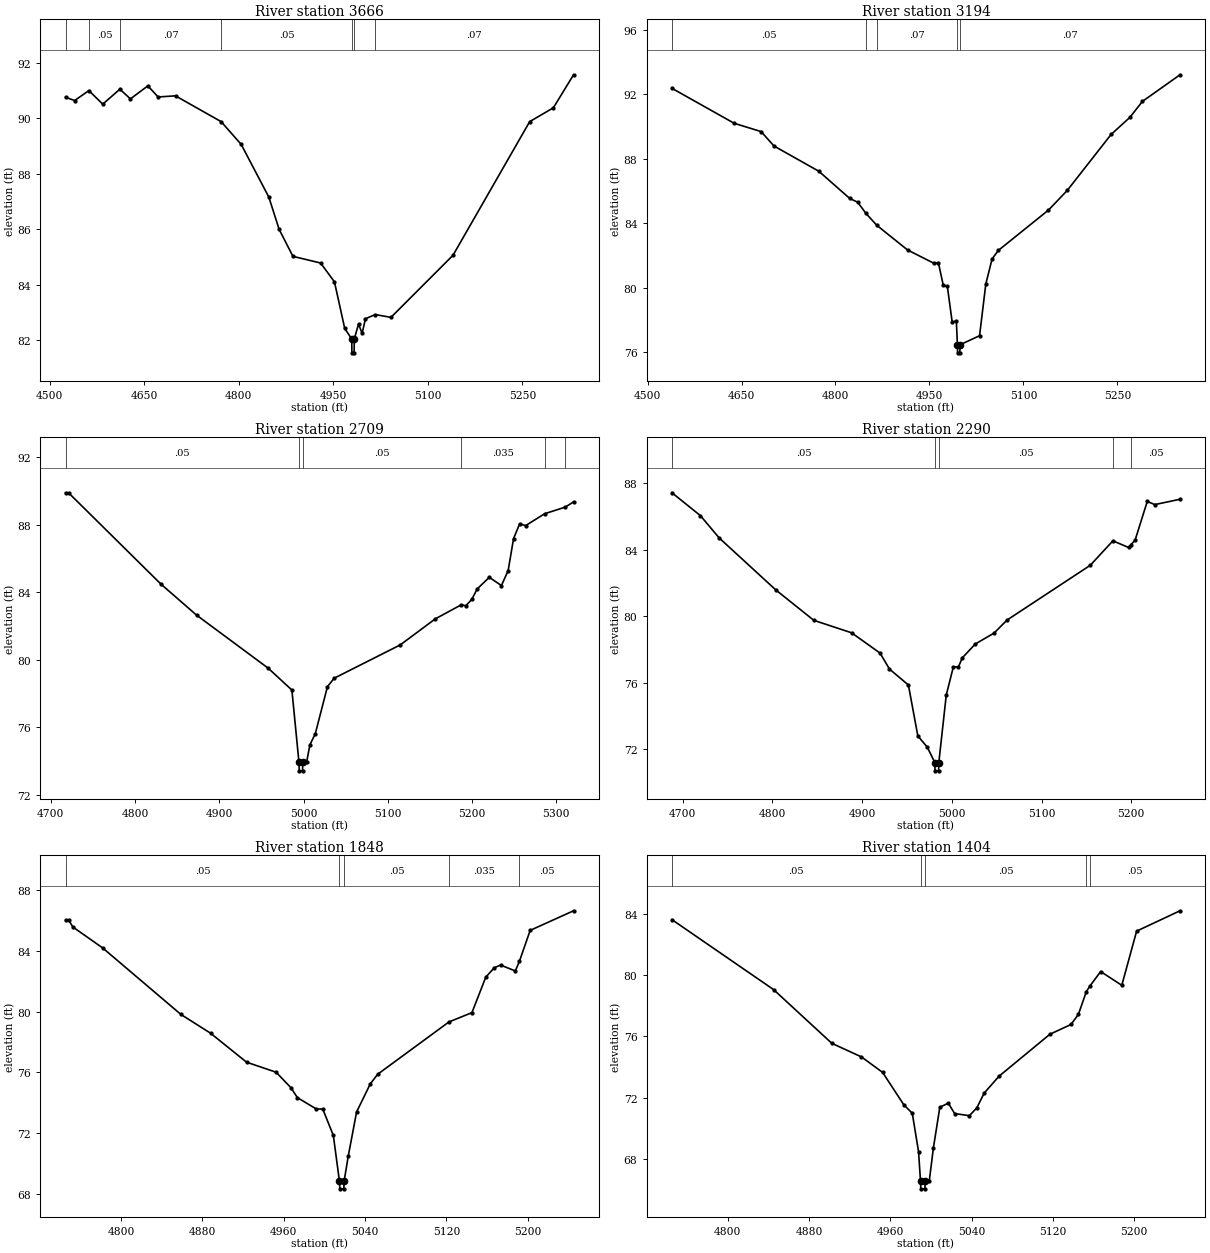
Type RM Length L Ch R = 1 ,3666    ,472,472,472
BEGIN DESCRIPTION:
TRIB 2-10 TO GUADALUPE RIVER 8.0
END DESCRIPTION:
XS GIS Cut Line= 3
      2583999.88     13440797.76        2584225.       13440375.
      2584092.02     13440075.79
#Sta/Elev= 30
  4524.9   90.76  4539.4   90.64    4562      91    4584   90.51  4611.2   91.05
  4627.9    90.7  4655.6   91.17  4671.9   90.77  4699.5   90.81  4771.9   89.88
  4803.7   89.06  4847.6   87.16  4863.9      86  4885.9   85.02  4929.8   84.78
  4951.8    84.1  4968.1   82.42  4979.2   82.04  4979.5   81.54    4983   81.54
  4983.3   82.04    4990   82.58  4995.7   82.24    5001   82.77  5016.4   82.92
  5041.5   82.82    5140   85.06  5261.7   89.88  5299.3   90.38  5331.3   91.57
#Mann= 7 ,-1 , 0
  4524.9    .035       0    4562     .05       0  4611.2     .07       0
  4771.9     .05       0  4979.2     .05       0  4983.3     .05       0
  5016.4     .07       0
Bank Sta=4979.2,4983.3
XS Rating Curve= 0 ,0
Exp/Cntr=0.3,0.1

Type RM Length L Ch R = 1 ,3194    ,485,485,485
BEGIN DESCRIPTION:
TRIB 2-10 TO GUADALUPE RIVER 7.0
END DESCRIPTION:
XS GIS Cut Line= 3
      2584324.98     13440825.03        2584625.       13440475.
        2584625.     13440125.01
#Sta/Elev= 30
    4539   92.37  4638.4    90.2  4681.2   89.69    4702   88.79  4773.4   87.23
  4822.8   85.54  4835.4   85.31  4848.8   84.61  4865.9   83.88    4915   82.35
  4957.8   81.51  4964.3   81.56    4972   80.17  4978.6   80.09  4986.3   77.88
  4992.9   77.95  4994.7   76.47  4994.9   75.97  4998.5   75.97  4998.8   76.47
    5030   77.03    5040   80.24    5050   81.79    5060   82.32    5140   84.82
    5170   86.04    5240   89.51    5270   90.57    5290   91.56    5350   93.21
#Mann= 5 ,-1 , 0
    4539     .05       0  4848.8    .035       0  4865.9     .07       0
  4994.7     .05       0  4998.8     .07       0
Bank Sta=4994.7,4998.8
XS Rating Curve= 0 ,0
Exp/Cntr=0.3,0.1

Type RM Length L Ch R = 1 ,2709    ,419,419,419
BEGIN DESCRIPTION:
TRIB 2-10 TO GUADALUPE RIVER 6.0
END DESCRIPTION:
XS GIS Cut Line= 3
      2585275.02     13440575.02        2585075.       13440375.
      2584825.02     13440175.01
#Sta/Elev= 30
  4717.4   89.88    4721   89.88  4830.6   84.48    4873   82.64  4957.8   79.51
  4986.1   78.21  4994.5   73.93  4994.8   73.43  4998.7   73.43    4999   73.93
  5003.5   73.93  5007.5   74.97  5013.9   75.63  5028.3   78.41  5036.3   78.91
  5114.7   80.88  5156.3   82.42  5187.4   83.26  5192.4   83.19  5199.6   83.57
    5206   84.19  5220.4   84.88  5234.8   84.39  5242.8   85.28  5249.2   87.17
  5256.4   88.04  5263.6   87.94  5286.1   88.64  5310.5   89.03  5320.4   89.34
#Mann= 6 ,-1 , 0
  4717.4     .05       0  4994.5     .05       0    4999     .05       0
  5187.4    .035       0  5286.1     .05       0  5310.5     .07       0
Bank Sta=4994.5,4999
XS Rating Curve= 0 ,0
Exp/Cntr=0.3,0.1

Type RM Length L Ch R = 1 ,2290    ,442,442,442
BEGIN DESCRIPTION:
TRIB 2-10 TO GUADALUPE RIVER 5.0
END DESCRIPTION:
XS GIS Cut Line= 3
      2585574.97     13440124.99        2585275.       13440025.
        2585075.       13439875.
#Sta/Elev= 30
  4688.1   87.43  4719.7   86.06  4740.8   84.71    4804   81.58  4846.2   79.76
  4888.3   79.01    4920   77.79  4930.5   76.83  4951.6   75.87  4962.1   72.81
  4972.7   72.13    4981   71.21  4981.3   70.71  4985.2   70.71  4985.5   71.21
  4993.8   75.27  5001.7   76.96  5007.4   76.96  5011.6    77.5  5026.2   78.34
    5047   78.99  5061.6   79.78  5154.3   83.07  5179.5   84.54    5197   84.14
  5199.4   84.29  5204.3   84.59  5217.8   86.91  5226.2   86.72  5254.3   87.04
#Mann= 5 ,-1 , 0
  4688.1     .05       0    4981     .05       0  4985.5     .05       0
  5179.5    .035       0  5199.4     .05       0
Bank Sta=4981,4985.5
XS Rating Curve= 0 ,0
Exp/Cntr=0.3,0.1

Type RM Length L Ch R = 1 ,1848    ,444,444,444
BEGIN DESCRIPTION:
TRIB 2-10 TO GUADALUPE RIVER 4.0
END DESCRIPTION:
XS GIS Cut Line= 3
      2585675.02     13439875.03        2585525.       13439675.
      2585325.03     13439525.02
#Sta/Elev= 30
  4745.2      86  4748.4      86  4752.5   85.56  4781.7   84.19  4858.8   79.81
  4887.9   78.58  4923.4   76.67  4952.5   76.01  4967.1   74.99  4973.4   74.34
  4992.1   73.59  4998.4   73.59  5008.8   71.85  5014.8   68.84  5015.2   68.34
  5019.1   68.34  5019.4   68.84  5023.4   70.47  5031.7    73.4  5045.2   75.25
  5052.5   75.88  5122.6   79.32  5145.2   79.93  5158.8   82.26  5167.1   82.88
  5173.4   83.06  5187.9   82.67    5192   83.32  5202.5   85.34  5245.2   86.63
#Mann= 5 ,-1 , 0
  4745.2     .05       0  5014.8     .05       0  5019.4     .05       0
  5122.6    .035       0    5192     .05       0
Bank Sta=5014.8,5019.4
XS Rating Curve= 0 ,0
Exp/Cntr=0.3,0.1

Type RM Length L Ch R = 1 ,1404    ,462,462,462
BEGIN DESCRIPTION:
TRIB 2-10 TO GUADALUPE RIVER 3.0
END DESCRIPTION:
XS GIS Cut Line= 3
      2585925.02     13439525.03        2585775.       13439325.
      2585575.03     13439175.02
#Sta/Elev= 30
  4745.2   83.63  4845.2   79.06  4902.5   75.55  4931.7   74.66  4952.5   73.65
  4973.4   71.53  4981.7   70.98  4987.9   68.46  4989.8   66.54  4990.1   66.04
  4994.1   66.04  4994.4   66.54  4998.4   66.54  5002.5   68.72  5008.8   71.37
  5017.1   71.64  5023.4   70.96  5037.9   70.82  5045.2   71.33  5052.5    72.3
  5067.1    73.4  5117.1   76.14  5137.9   76.78  5145.2   77.44  5152.9   78.91
  5156.3   79.27  5167.1   80.24  5187.9   79.34  5202.5   82.88  5245.2   84.21
#Mann= 5 ,-1 , 0
  4745.2     .05       0  4989.8     .05       0  4994.4     .05       0
  5152.9    .035       0  5156.3     .05       0
Bank Sta=4989.8,4994.4
XS Rating Curve= 0 ,0
Exp/Cntr=0.3,0.1

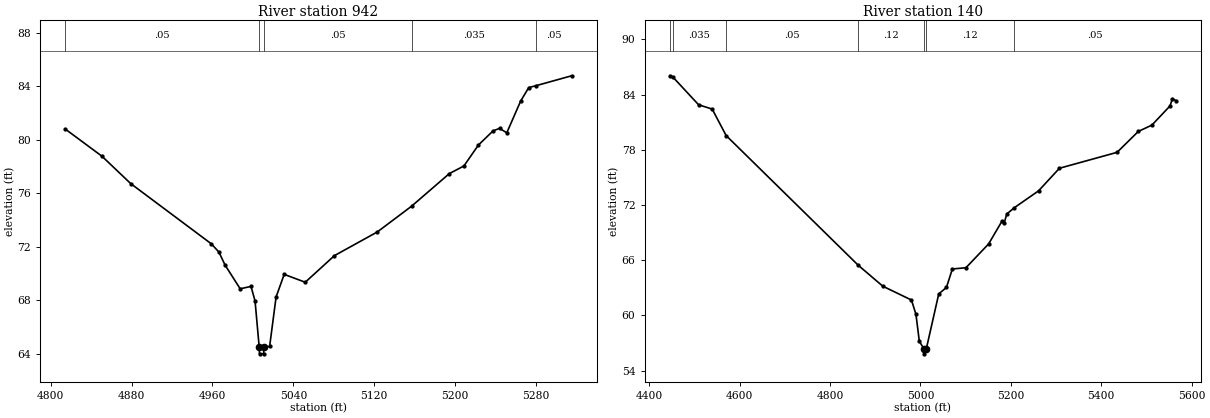
Type RM Length L Ch R = 1 ,942     ,802,802,802
BEGIN DESCRIPTION:
TRIB 2-10 TO GUADALUPE RIVER 2.0
END DESCRIPTION:
XS GIS Cut Line= 3
      2586175.02     13439175.04        2586075.       13439025.
      2585824.98     13438824.99
#Sta/Elev= 30
  4814.6   80.78  4850.7   78.76  4879.2   76.71  4958.9   72.21  4966.4   71.59
  4972.4   70.63  4987.4   68.85  4998.1   69.03  5002.1   67.94  5006.2   64.49
  5006.5   63.99  5010.5   63.99  5010.9   64.49  5016.5   64.54  5022.9   68.24
  5030.9   69.93  5051.7   69.34  5080.6   71.33    5123    73.1  5156.8   75.02
  5194.2   77.46  5208.6   78.03    5223    79.6  5237.4   80.65  5243.8   80.84
    5251   80.51  5264.7   82.88  5272.7   83.89  5279.9   84.03  5315.1   84.77
#Mann= 5 ,-1 , 0
  4814.6     .05       0  5006.2     .05       0  5010.9     .05       0
  5156.8    .035       0  5279.9     .05       0
Bank Sta=5006.2,5010.9
XS Rating Curve= 0 ,0
Exp/Cntr=0.3,0.1

Type RM Length L Ch R = 1 ,140     ,0,0,0
BEGIN DESCRIPTION:
TRIB 2-10 TO GUADALUPE RIVER 1.0
END DESCRIPTION:
XS GIS Cut Line= 3
      2586676.36     13439058.43      2586645.47     13438505.19
       2586081.7     13438550.63
#Sta/Elev= 30
  4445.9   86.04    4452   85.93  4509.4   82.89  4539.5   82.42  4570.4   79.54
  4862.7   65.44  4916.9   63.17  4980.2   61.67  4990.2   60.12  4997.6    57.2
  5008.2   56.32  5008.5   55.82  5012.9   56.32  5040.6   62.33  5057.7   63.04
  5070.7   65.04  5100.8   65.18    5151   67.77  5180.2   70.22  5185.2   69.99
  5191.1   71.02    5208   71.71  5261.3   73.53  5307.6   75.99  5435.1   77.72
    5482   79.99  5512.1   80.68  5552.3   82.77  5557.5   83.56  5565.6   83.33
#Mann= 7 ,-1 , 0
  4445.9     .05       0    4452    .035       0  4570.4     .05       0
  4862.7     .12       0  5008.2     .05       0  5012.9     .12       0
    5208     .05       0
Bank Sta=5008.2,5012.9
XS Rating Curve= 0 ,0
Exp/Cntr=0.3,0.1

Chan Stop Cuts=-1
Use User Specified Reach Order=0
Composite Channel Slope=5