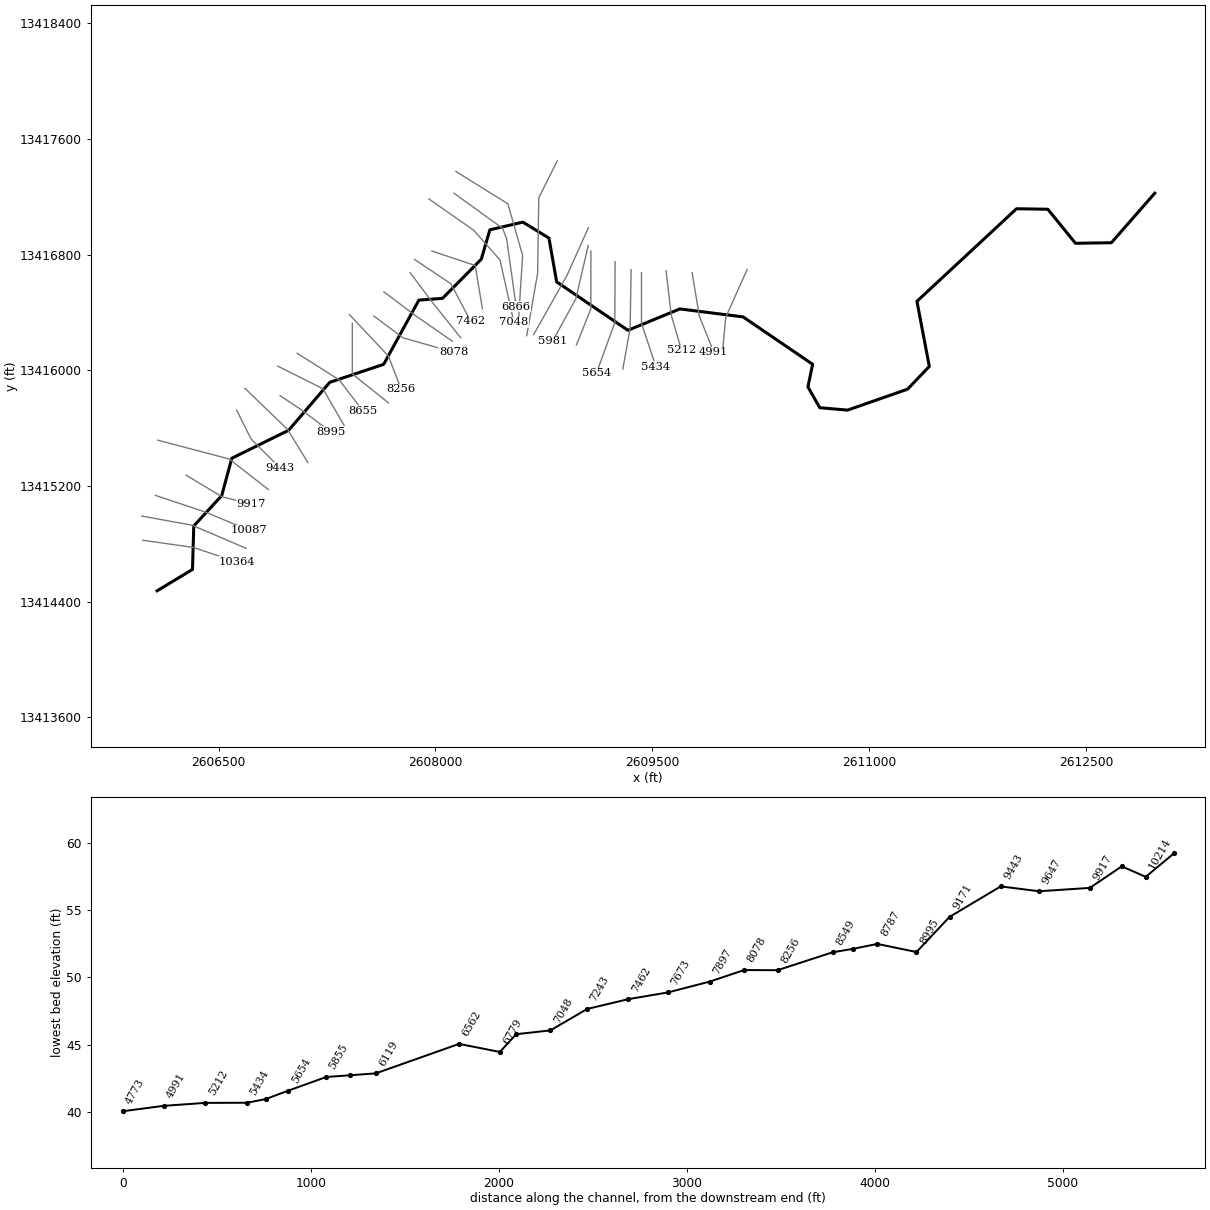
--- TRIB 2_4 TO GUADALUPE RIVER.prj (project) ---

Proj Title=TRIB 2_4 TO GUADALUPE RIVER Base Level Engineering
Current Plan=p01
Default Exp/Contr=0.3,0.1
English Units
Geom File=g01
Flow File=f01
Plan File=p01
Y Axis Title=Elevation
X Axis Title(PF)=Main Channel Distance
X Axis Title(XS)=Station
BEGIN DESCRIPTION:
TRIB 2_4 TO GUADALUPE RIVER
END DESCRIPTION:
DSS Export Rating Curves= 0
DSS Export Rating Curve Sorted= 0
DSS Export Volume Flow Curves= 0
DXF OffsetX= 0
DXF OffsetY= 0
DXF ScaleX= 1
DXF ScaleY= 10

--- TRIB 2_4 TO GUADALUPE RIVER.p01 (plan) ---

Plan Title=Multiple Run
Short Identifier=Multiple
Geom File=g01
Flow File=f01
Subcritical Flow
K Sum by GR= 0
Std Step Tol= 0.01
Critical Tol= 0.01
Num of Std Step Trials= 20
Max Error Tol= 0.3
Flow Tol Ratio= 0.001
Split Flow NTrial= 30
Split Flow Tol= 0.02
Split Flow Ratio= 0.02
Log Output Level= 0
Friction Slope Method= 1
Unsteady Friction Slope Method= 2
Unsteady Bridges Friction Slope Method= 1
Parabolic Critical Depth
Global Vel Dist=  1 , 1 , 1
Global Log Level= 0
CheckData=True
Encroach Param= -1, 0, 0, 0
BEGIN DESCRIPTION:
Multiple Run
END DESCRIPTION:

--- TRIB 2_4 TO GUADALUPE RIVER.f01 (steady flow) ---

Flow Title=Multiple
Number of Profiles=7
Profile Names=10-year,25-year,50-year,1pct_min,100-year,1pct_plu,500-year
River Rch & RM= TRIB 2_4 TO GUAD,Reach-1,10364
     536     822    1065     668    1332    2658    2058
River Rch & RM= TRIB 2_4 TO GUAD,Reach-1,10214
     696    1086    1426     904    1804    3600    2855
River Rch & RM= TRIB 2_4 TO GUAD,Reach-1,7048
     920    1464    1947    1251    2496    4980    4053
Boundary for River Rch & Prof#=TRIB 2_4 TO GUAD,Reach-1,1
Up Type=0
Dn Type=3
Dn Slope=0.005
Boundary for River Rch & Prof#=TRIB 2_4 TO GUAD,Reach-1,2
Up Type=0
Dn Type=3
Dn Slope=0.005
Boundary for River Rch & Prof#=TRIB 2_4 TO GUAD,Reach-1,3
Up Type=0
Dn Type=3
Dn Slope=0.005
Boundary for River Rch & Prof#=TRIB 2_4 TO GUAD,Reach-1,4
Up Type=0
Dn Type=3
Dn Slope=0.005
Boundary for River Rch & Prof#=TRIB 2_4 TO GUAD,Reach-1,5
Up Type=0
Dn Type=3
Dn Slope=0.005
Boundary for River Rch & Prof#=TRIB 2_4 TO GUAD,Reach-1,6
Up Type=0
Dn Type=3
Dn Slope=0.005
Boundary for River Rch & Prof#=TRIB 2_4 TO GUAD,Reach-1,7
Up Type=0
Dn Type=3
Dn Slope=0.005

--- TRIB 2_4 TO GUADALUPE RIVER.g01 (geometry) ---

Geom Title=Existing Conditions
Program Version=4.10

River Reach=TRIB 2_4 TO GUAD,Reach-1
Reach XY= 30
        2606075.       13414475.      2606319.55     13414622.53
      2606328.55     13414923.53      2606521.81     13415133.35
      2606591.46     13415391.75      2606984.82     13415585.47
      2607268.94     13415916.86       2607641.8     13416041.42
      2607885.51     13416485.52      2608048.83     13416497.57
      2608317.18     13416768.81      2608376.25     13416971.49
      2608604.65      13417024.9      2608785.06     13416914.39
      2608838.37     13416611.68      2609331.11     13416276.79
      2609690.28     13416424.61      2610127.44     13416369.52
      2610608.71     13416041.71      2610576.09     13415885.55
      2610657.86     13415741.27      2610850.08      13415724.8
       2611265.1     13415869.36      2611415.67     13416027.16
      2611330.09      13416477.3      2612018.95      13417117.5
      2612235.37     13417114.02      2612426.47     13416878.53
      2612675.01     13416882.55        2612975.       13417225.

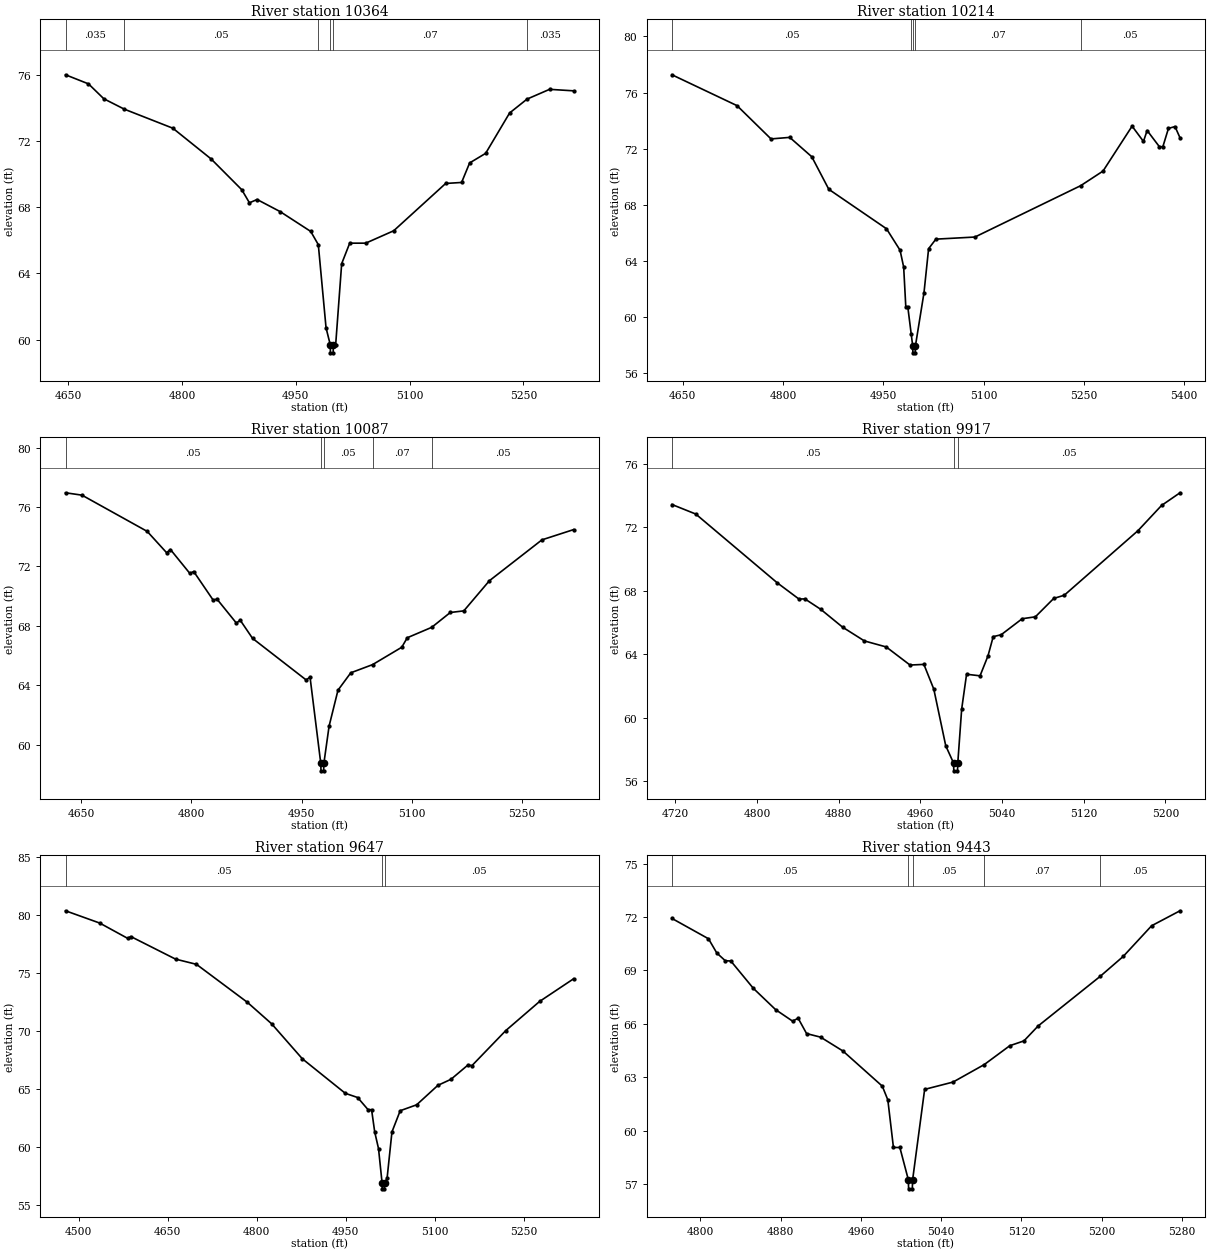
Type RM Length L Ch R = 1 ,10364   ,150,150,150
BEGIN DESCRIPTION:
TRIB 2-4 TO GUADALUPE RIVER 18.0
END DESCRIPTION:
XS GIS Cut Line= 3
      2605974.96     13414825.01        2606325.       13414775.
      2606624.98     13414675.01
#Sta/Elev= 30
  4646.4   76.01  4676.7   75.46  4696.9   74.56    4724   73.93  4787.9   72.78
  4838.4   70.92  4878.8   69.06  4888.9   68.27    4899   68.47  4929.3   67.74
  4969.7   66.54  4979.7   65.74  4989.9   60.71  4995.4    59.7  4995.7    59.2
  4999.3    59.2  4999.5    59.7  5002.6    59.7  5010.5   64.59  5021.1   65.83
  5042.2   65.83  5079.1   66.58  5147.6   69.44  5168.6    69.5  5179.2   70.68
  5200.3   71.26  5231.9    73.7  5254.9   74.54  5284.6   75.13  5316.2   75.04
#Mann= 6 ,-1 , 0
  4646.4    .035       0    4724     .05       0  4979.7     .07       0
  4995.4     .05       0  4999.5     .07       0  5254.9    .035       0
Bank Sta=4995.4,4999.5
XS Rating Curve= 0 ,0
Exp/Cntr=0.3,0.1

Type RM Length L Ch R = 1 ,10214   ,127,127,127
BEGIN DESCRIPTION:
Mapping XS 82cce161
END DESCRIPTION:
XS GIS Cut Line= 3
      2605969.16     13414991.87      2606316.41     13414928.93
      2606690.88     13414768.75
#Sta/Elev= 30
  4633.8   77.27  4731.2   75.07    4782    72.7    4810   72.81    4843   71.43
  4868.5   69.11  4954.8    66.3  4975.1   64.77  4980.5   63.57  4983.7   60.72
  4986.7   60.72  4991.8   58.79    4994   57.96  4994.2   57.46  4997.8   57.46
  4998.1   57.96  5010.9   61.74  5017.8   64.88  5028.7   65.56  5087.1   65.71
  5245.4   69.37  5278.8   70.41  5322.3   73.61  5339.3   72.52  5344.8    73.3
  5362.9   72.16  5368.3   72.14  5376.7   73.45  5386.5   73.58    5394   72.78
#Mann= 5 ,-1 , 0
  4633.8     .05       0  4991.8     .07       0    4994     .05       0
  4998.1     .07       0  5245.4     .05       0
Bank Sta=4994,4998.1
XS Rating Curve= 0 ,0
Exp/Cntr=0.3,0.1

Type RM Length L Ch R = 1 ,10087   ,170,170,170
BEGIN DESCRIPTION:
Mapping XS 557fd47d
END DESCRIPTION:
XS GIS Cut Line= 3
       2606063.7     13415134.83      2606407.43     13415020.25
      2606710.59     13414893.79
#Sta/Elev= 30
  4629.1   76.96  4651.5    76.8  4740.2   74.36  4766.5   72.93  4771.8   73.14
  4798.2   71.53  4803.4   71.66  4829.8   69.74  4835.1    69.8  4861.4   68.19
  4866.7   68.38  4883.4   67.16  4956.3   64.36  4961.6   64.55  4976.2   58.74
  4976.5   58.24  4980.1   58.24  4980.4   58.74  4987.5   61.25  4999.6   63.67
    5017   64.84  5046.6   65.39  5086.3   66.56  5093.8    67.2    5127    67.9
  5152.3    68.9  5170.7   69.01  5205.5   71.04  5276.9   73.79  5319.9   74.48
#Mann= 5 ,-1 , 0
  4629.1     .05       0  4976.2     .05       0  4980.4     .05       0
  5046.6     .07       0    5127     .05       0
Bank Sta=4976.2,4980.4
XS Rating Curve= 0 ,0
Exp/Cntr=0.3,0.1

Type RM Length L Ch R = 1 ,9917    ,270,270,270
BEGIN DESCRIPTION:
TRIB 2-4 TO GUADALUPE RIVER 17.0
END DESCRIPTION:
XS GIS Cut Line= 3
      2606275.01     13415274.99        2606525.       13415125.
      2606725.01       13415075.
#Sta/Elev= 30
  4716.7   73.43    4740   72.83  4819.7    68.5  4841.1   67.47  4846.9   67.48
  4862.5   66.82  4883.8    65.7  4905.2   64.83  4926.6   64.45  4949.9   63.31
  4963.5   63.35  4973.2   61.79  4984.9   58.22  4992.5   57.14  4992.8   56.64
  4996.4   56.64  4996.7   57.14  5000.5   60.53  5005.3   62.73  5018.5   62.63
  5026.3   63.89  5031.4    65.1  5039.2   65.22  5059.8   66.23  5072.7   66.35
  5090.7   67.51    5101   67.71  5173.2   71.78  5196.3   73.37  5214.4   74.17
#Mann= 3 ,-1 , 0
  4716.7     .05       0  4992.5     .05       0  4996.7     .05       0
Bank Sta=4992.5,4996.7
XS Rating Curve= 0 ,0
Exp/Cntr=0.3,0.1

Type RM Length L Ch R = 1 ,9647    ,204,204,204
BEGIN DESCRIPTION:
Mapping XS cccab72a
END DESCRIPTION:
XS GIS Cut Line= 3
      2606079.29     13415516.78       2606574.1     13415386.57
      2606844.95     13415174.75
#Sta/Elev= 30
    4478   80.38  4535.6   79.32  4582.7      78  4587.9   78.16  4663.3   76.21
  4698.5   75.76  4784.3   72.48  4825.1   70.63  4876.8   67.61  4949.2   64.63
  4969.9   64.27  4987.5   63.22  4993.4   63.22  4998.7   61.29  5005.1   59.86
  5011.1   56.89  5011.4   56.39    5015   56.39  5015.3   56.89  5019.5   57.29
  5027.7    61.3  5041.6   63.13  5069.3   63.64  5105.1   65.32  5127.1   65.84
  5155.8   67.08  5162.4   67.02  5219.3   70.04  5276.4   72.56  5333.5   74.51
#Mann= 3 ,-1 , 0
    4478     .05       0  5011.1     .05       0  5015.3     .05       0
Bank Sta=5011.1,5015.3
XS Rating Curve= 0 ,0
Exp/Cntr=0.3,0.1

Type RM Length L Ch R = 1 ,9443    ,272,272,272
BEGIN DESCRIPTION:
TRIB 2-4 TO GUADALUPE RIVER 16.0
END DESCRIPTION:
XS GIS Cut Line= 3
      2606624.99     13415725.02        2606725.       13415525.
      2606925.02     13415324.98
#Sta/Elev= 30
  4771.6   71.92    4808   70.78  4816.3   69.98  4824.7   69.55  4830.3   69.53
  4852.7      68    4875    66.8  4891.8   66.16  4897.4   66.32  4905.8   65.46
  4919.8   65.26  4942.1   64.48  4981.3   62.51  4986.8   61.74  4992.4   59.07
  4998.8   59.07  5007.3   57.25  5007.5   56.75  5011.2   56.75  5011.5   57.25
  5023.5   62.33  5051.8   62.74  5082.9   63.72  5108.4   64.78  5122.5   65.05
  5136.7   65.89  5198.5   68.67  5221.5   69.79  5249.8   71.51  5278.1   72.35
#Mann= 5 ,-1 , 0
  4771.6     .05       0  5007.3     .05       0  5011.5     .05       0
  5082.9     .07       0  5198.5     .05       0
Bank Sta=5007.3,5011.5
XS Rating Curve= 0 ,0
Exp/Cntr=0.3,0.1

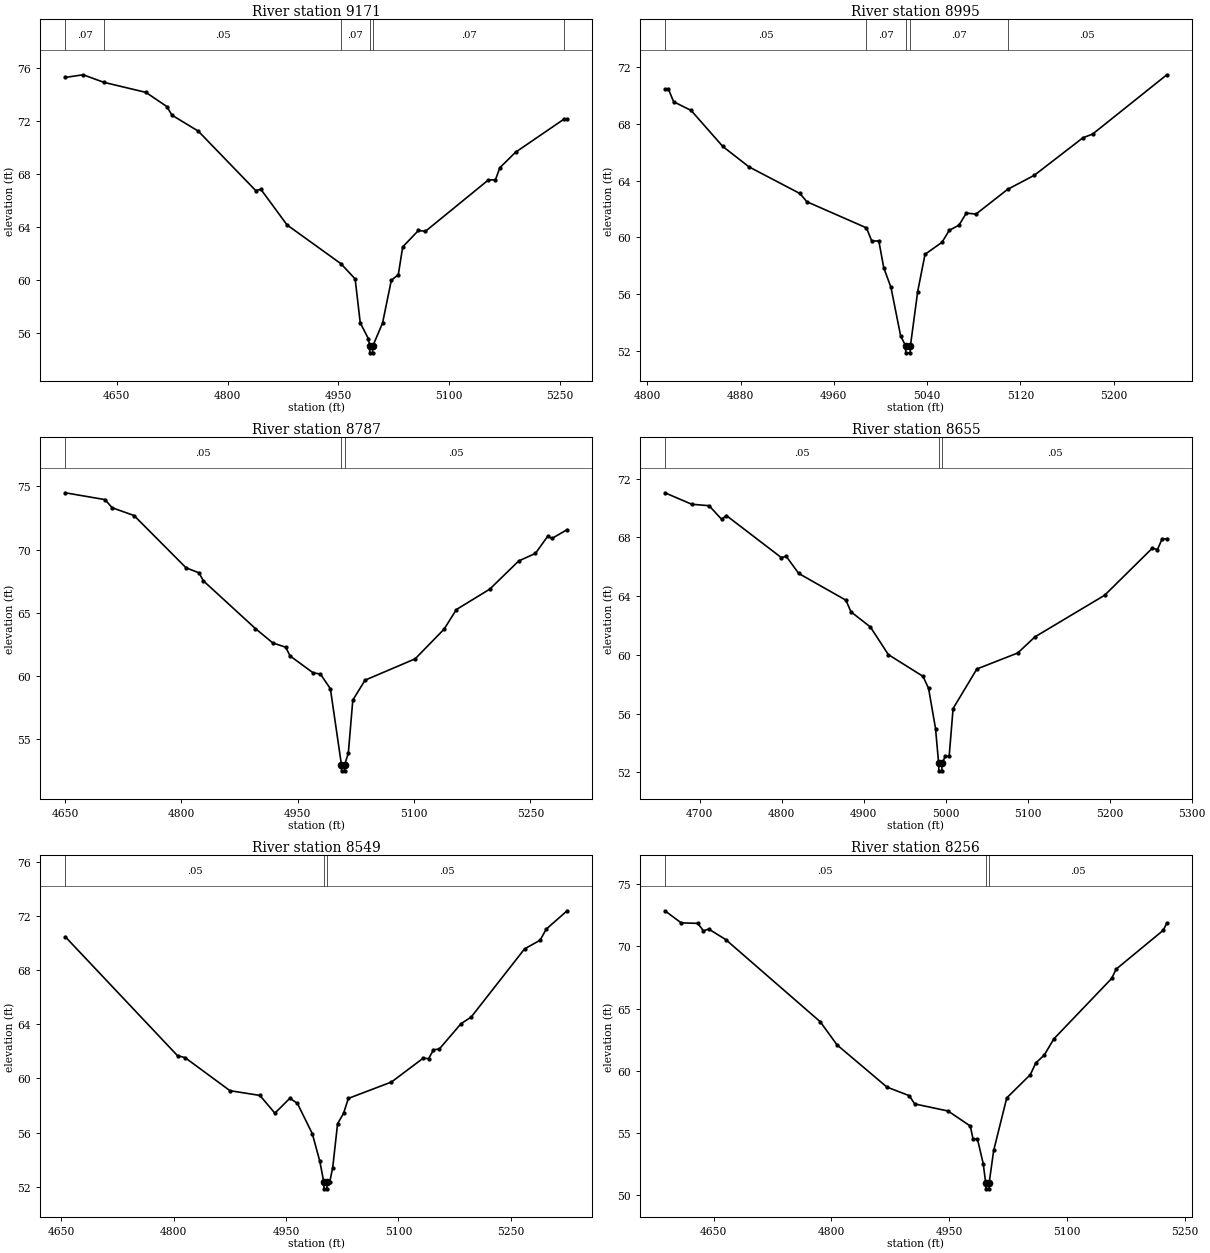
Type RM Length L Ch R = 1 ,9171    ,176,176,176
BEGIN DESCRIPTION:
Mapping XS 8b853290
END DESCRIPTION:
XS GIS Cut Line= 3
      2606681.76     13415876.13      2606976.87     13415591.43
      2607117.49     13415362.29
#Sta/Elev= 30
  4580.4   75.29  4604.7   75.49  4632.7   74.92  4689.6   74.16  4717.9   73.09
  4724.8   72.44  4760.3   71.24    4838   66.75  4845.2   66.83  4880.5   64.15
  4953.4   61.22  4972.6   60.07  4979.5   56.75  4990.5   55.56  4992.2   54.99
  4992.4   54.49  4996.1   54.49  4996.4   54.99  5009.7   56.75  5021.5   59.96
    5031    60.4  5036.9   62.49  5058.2   63.73  5067.7   63.67  5152.9   67.55
  5162.3   67.55  5168.3   68.47  5189.6   69.64  5255.6   72.16  5259.3   72.16
#Mann= 6 ,-1 , 0
  4580.4     .07       0  4632.7     .05       0  4953.4     .07       0
  4992.2     .05       0  4996.4     .07       0  5255.6     .05       0
Bank Sta=4992.2,4996.4
XS Rating Curve= 0 ,0
Exp/Cntr=0.3,0.1

Type RM Length L Ch R = 1 ,8995    ,208,208,208
BEGIN DESCRIPTION:
TRIB 2-4 TO GUADALUPE RIVER 15.0
END DESCRIPTION:
XS GIS Cut Line= 3
      2606925.01     13415824.99        2607075.       13415725.
      2607275.03     13415574.98
#Sta/Elev= 30
  4815.2   70.43  4818.2   70.43  4822.7   69.54  4837.7   68.93  4864.8    66.4
  4887.3   64.96  4930.9   63.09  4936.9   62.51    4988   60.67  4992.5   59.75
  4998.6   59.75  5002.8   57.87    5009   56.48  5017.3   53.07  5021.5   52.38
  5021.7   51.88  5025.4   51.88  5025.7   52.38  5031.9   56.19  5038.2   58.81
  5052.8   59.66    5059    60.5  5067.3   60.86  5073.6   61.71  5081.9   61.64
    5109   63.38  5131.9   64.37  5173.6   67.01  5181.9   67.27  5245.5   71.44
#Mann= 5 ,-1 , 0
  4815.2     .05       0    4988     .07       0  5021.5     .05       0
  5025.7     .07       0    5109     .05       0
Bank Sta=5021.5,5025.7
XS Rating Curve= 0 ,0
Exp/Cntr=0.3,0.1

Type RM Length L Ch R = 1 ,8787    ,132,132,132
BEGIN DESCRIPTION:
Mapping XS 37590578
END DESCRIPTION:
XS GIS Cut Line= 3
       2606909.2     13416028.92      2607221.67     13415872.68
      2607370.51     13415614.81
#Sta/Elev= 30
  4650.1    74.5  4701.3   73.96  4710.8   73.31  4738.8    72.7  4805.9   68.56
  4822.6   68.16  4828.2   67.53  4895.3   63.75  4917.7   62.61  4934.4   62.27
    4940   61.58  4969.6   60.25  4979.2   60.14    4992   58.98  5006.2   52.98
  5006.5   52.48  5010.2   52.48  5010.4   52.98  5015.1   53.87  5020.9   58.08
  5036.7   59.66  5101.3   61.35  5138.6    63.7  5154.4   65.25  5197.5   66.87
  5234.8    69.1  5256.4    69.7  5272.1   71.05  5277.9   70.89  5297.2   71.58
#Mann= 3 ,-1 , 0
  4650.1     .05       0  5006.2     .05       0  5010.4     .05       0
Bank Sta=5006.2,5010.4
XS Rating Curve= 0 ,0
Exp/Cntr=0.3,0.1

Type RM Length L Ch R = 1 ,8655    ,106,106,106
BEGIN DESCRIPTION:
Mapping XS 65fd3e80
END DESCRIPTION:
XS GIS Cut Line= 3
      2607043.42     13416118.16      2607334.21     13415933.71
      2607496.99     13415721.01
#Sta/Elev= 30
  4657.5   71.03  4690.2   70.25  4711.4   70.15  4726.6   69.23  4732.5   69.48
  4799.5   66.62  4805.4   66.71  4820.7   65.54  4878.3   63.72  4884.4   62.93
  4908.1    61.9    4930   60.02  4972.3   58.54  4979.1   57.72  4987.6   54.98
  4991.4   52.61  4991.6   52.11  4995.3   52.11  4995.6   52.61  4999.4    53.1
  5004.2    53.1    5009   56.35    5038   59.04  5087.9   60.13  5108.7   61.22
  5193.9   64.06    5252   67.26  5258.3   67.17    5264    67.9  5269.7    67.9
#Mann= 3 ,-1 , 0
  4657.5     .05       0  4991.4     .05       0  4995.6     .05       0
Bank Sta=4991.4,4995.6
XS Rating Curve= 0 ,0
Exp/Cntr=0.3,0.1

Type RM Length L Ch R = 1 ,8549    ,293,293,293
BEGIN DESCRIPTION:
TRIB 2-4 TO GUADALUPE RIVER 14.0
END DESCRIPTION:
XS GIS Cut Line= 3
        2607425.     13416325.05        2607425.       13415975.
        2607675.       13415775.
#Sta/Elev= 30
    4655   70.46    4805   61.68    4815   61.54    4875    59.1    4915   58.75
    4935   57.44    4955   58.54    4965   58.17    4985   55.92    4995   53.89
  5000.3   52.36  5000.6   51.86  5004.4   51.86  5004.7   52.36  5008.2   52.36
  5012.2   53.42  5018.7   56.66  5026.7   57.43  5033.1   58.53  5090.7   59.74
  5133.1    61.5  5140.3   61.46  5146.7   62.11  5154.7   62.18  5183.5   64.04
  5197.1   64.53  5268.4   69.56  5289.2    70.2  5297.2   71.01  5325.2   72.37
#Mann= 3 ,-1 , 0
    4655     .05       0  5000.3     .05       0  5004.7     .05       0
Bank Sta=5000.3,5004.7
XS Rating Curve= 0 ,0
Exp/Cntr=0.3,0.1

Type RM Length L Ch R = 1 ,8256    ,178,178,178
BEGIN DESCRIPTION:
Mapping XS 6241aff0
END DESCRIPTION:
XS GIS Cut Line= 3
      2607405.67     13416384.86      2607674.79     13416098.38
      2607763.18     13415869.61
#Sta/Elev= 30
  4588.2   72.86  4608.9   71.89  4629.9   71.85  4637.2   71.25    4644   71.39
  4665.5   70.55  4785.7   63.95  4807.1   62.09  4870.6    58.7    4899   58.01
  4905.8   57.35  4948.3   56.78  4976.6   55.57  4980.1   54.52  4985.7   54.52
    4993   52.55  4996.1   51.03  4996.4   50.53  5000.2   50.53  5000.6   51.03
  5006.3   53.61  5022.9   57.83  5052.9    59.7  5059.9   60.64  5070.6   61.27
  5082.8   62.57  5156.4   67.43    5162   68.17  5221.9   71.29  5226.5   71.87
#Mann= 3 ,-1 , 0
  4588.2     .05       0  4996.1     .05       0  5000.6     .05       0
Bank Sta=4996.1,5000.6
XS Rating Curve= 0 ,0
Exp/Cntr=0.3,0.1

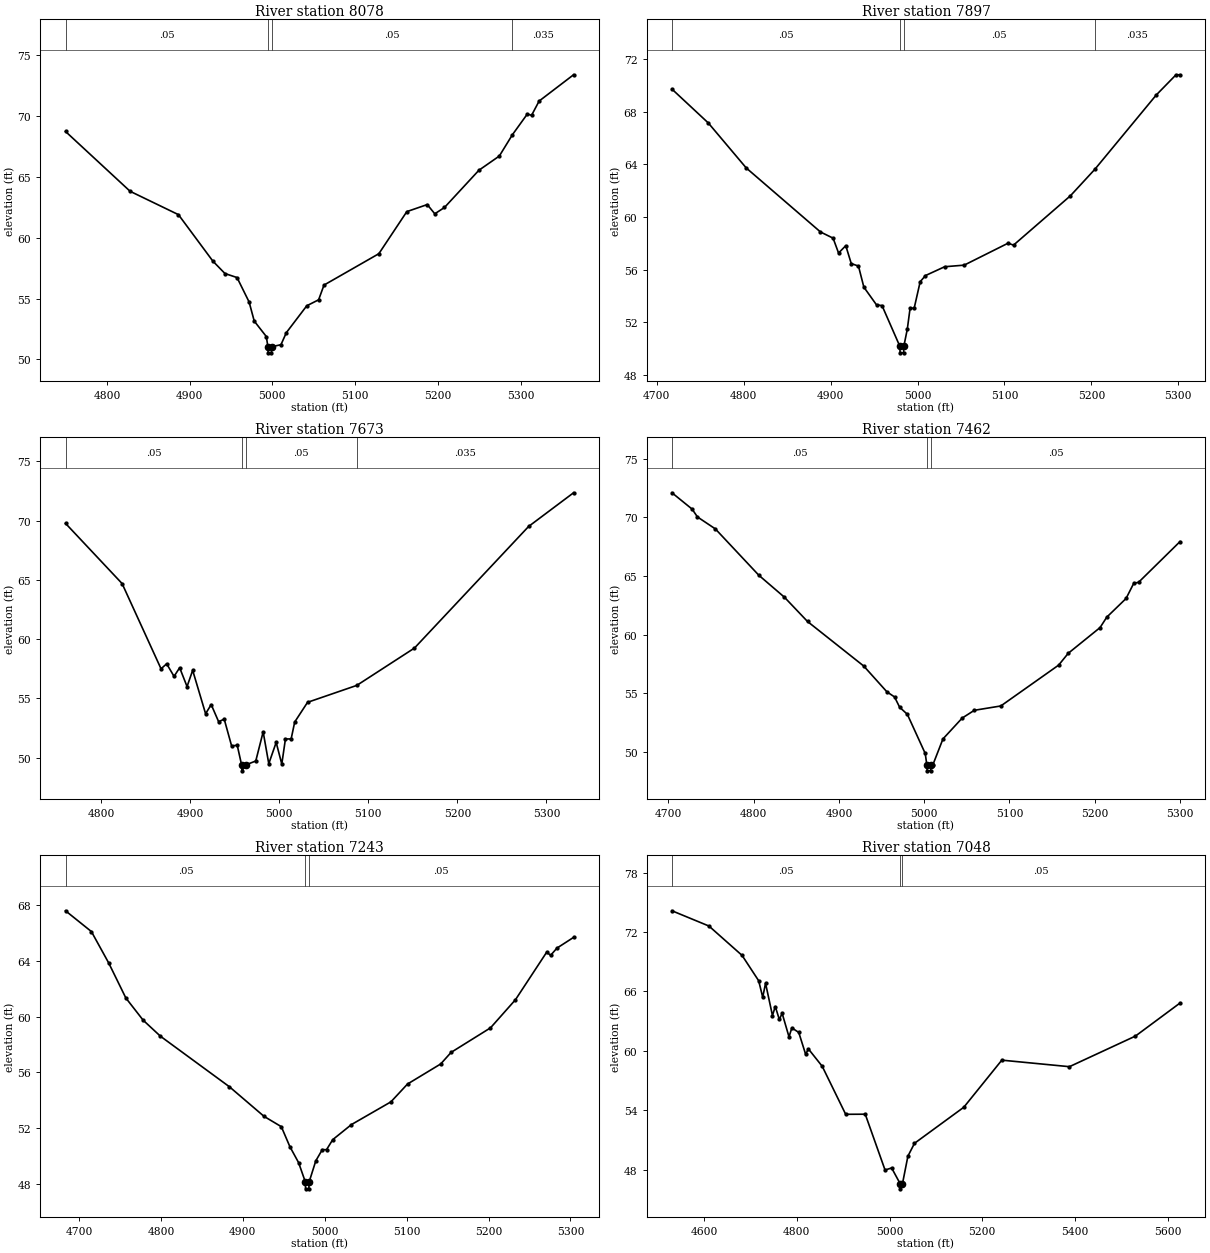
Type RM Length L Ch R = 1 ,8078    ,181,181,181
BEGIN DESCRIPTION:
TRIB 2-4 TO GUADALUPE RIVER 13.0
END DESCRIPTION:
XS GIS Cut Line= 3
        2607575.       13416375.        2607775.       13416225.
      2608124.99       13416125.
#Sta/Elev= 30
    4750   68.74  4828.1   63.82  4886.5    61.9  4928.1   58.08  4942.7   57.06
  4957.3   56.73  4971.9   54.72  4978.1   53.15  4992.7   51.88  4994.6   51.04
  4994.9   50.54  4998.9   50.54  4999.2   51.04  5010.4   51.21  5016.9    52.2
  5041.6   54.41  5055.9    54.9  5062.4   56.11  5128.7   58.69  5162.5   62.15
  5187.2   62.73  5196.3   61.97    5208   62.49  5249.6   65.55  5274.3   66.72
  5290.1   68.47  5308.1   70.17  5313.3   70.07  5322.4   71.24    5364    73.4
#Mann= 4 ,-1 , 0
    4750     .05       0  4994.6     .05       0  4999.2     .05       0
  5290.1    .035       0
Bank Sta=4994.6,4999.2
XS Rating Curve= 0 ,0
Exp/Cntr=0.3,0.1

Type RM Length L Ch R = 1 ,7897    ,224,224,224
BEGIN DESCRIPTION:
Mapping XS 173d0f2e
END DESCRIPTION:
XS GIS Cut Line= 3
      2607643.53     13416542.83      2607862.29     13416377.89
      2608117.49     13416200.81
#Sta/Elev= 30
  4717.4   69.72  4759.2   67.15  4802.9   63.73  4888.3   58.87  4902.8    58.4
  4909.1   57.27  4917.4   57.83  4923.7   56.47    4932   56.28  4938.2   54.68
  4952.8   53.33  4959.1   53.28  4979.6   50.19  4979.9   49.69  4983.9   49.69
  4984.2   50.19  4988.2   51.49  4991.4   53.08  4996.1   53.08    5003   55.09
  5009.1   55.56  5031.2   56.23  5053.6   56.35  5104.2   58.02  5110.4   57.87
  5175.9   61.62    5204   63.63  5274.6   69.27  5297.4   70.81    5302   70.81
#Mann= 4 ,-1 , 0
  4717.4     .05       0  4979.6     .05       0  4984.2     .05       0
    5204    .035       0
Bank Sta=4979.6,4984.2
XS Rating Curve= 0 ,0
Exp/Cntr=0.3,0.1

Type RM Length L Ch R = 1 ,7673    ,211,211,211
BEGIN DESCRIPTION:
TRIB 2-4 TO GUADALUPE RIVER 12.0
END DESCRIPTION:
XS GIS Cut Line= 3
      2607825.03     13416674.97        2607975.       13416475.
      2608174.99     13416225.01
#Sta/Elev= 30
  4760.3   69.76  4823.8   64.68  4867.5   57.49  4873.8   57.91  4882.1   56.85
  4888.4   57.58  4896.7   55.99    4903   57.36  4917.5    53.7  4923.8   54.47
  4932.1   53.03  4938.4   53.24  4946.7   50.98    4953   51.04  4957.9   49.38
  4958.3   48.88  4962.6   49.38  4973.8   49.71  4982.1   52.17  4988.4   49.48
  4996.7   51.28    5003   49.45  5007.1   51.57  5013.5   51.57  5017.5      53
  5031.9   54.66  5087.2   56.09  5151.9   59.24    5280    69.5  5330.4   72.34
#Mann= 4 ,-1 , 0
  4760.3     .05       0  4957.9     .05       0  4962.6     .05       0
  5087.2    .035       0
Bank Sta=4957.9,4962.6
XS Rating Curve= 0 ,0
Exp/Cntr=0.3,0.1

Type RM Length L Ch R = 1 ,7462    ,219,219,219
BEGIN DESCRIPTION:
Mapping XS 5e30b8df
END DESCRIPTION:
XS GIS Cut Line= 3
      2607855.39     13416766.75      2608107.08     13416598.38
       2608243.7     13416338.98
#Sta/Elev= 30
  4704.1   72.08  4727.7   70.69    4734   70.02    4755      69    4806   65.05
    4836   63.18  4863.1   61.11  4929.1   57.31  4956.3   55.11  4965.2   54.68
  4971.2    53.8  4980.2    53.2  5001.2   49.86  5003.1   48.88  5003.5   48.38
  5007.5   48.38  5007.8   48.88  5010.1   48.88    5022    51.1  5044.6   52.88
  5058.8   53.54  5089.9   53.91  5157.7   57.39    5169    58.4  5206.3   60.59
  5214.2   61.48  5236.8   63.07  5245.8   64.36  5251.5   64.45  5300.1   67.92
#Mann= 3 ,-1 , 0
  4704.1     .05       0  5003.1     .05       0  5007.8     .05       0
Bank Sta=5003.1,5007.8
XS Rating Curve= 0 ,0
Exp/Cntr=0.3,0.1

Type RM Length L Ch R = 1 ,7243    ,195,195,195
BEGIN DESCRIPTION:
TRIB 2-4 TO GUADALUPE RIVER 11.0
END DESCRIPTION:
XS GIS Cut Line= 3
      2607975.04     13416824.99        2608275.       13416725.
        2608325.     13416425.02
#Sta/Elev= 30
  4683.5    67.6  4715.1   66.11  4736.2   63.86  4757.2   61.34  4778.3   59.75
  4799.4    58.6  4883.7   54.97  4925.9   52.85    4947   52.11  4957.5   50.67
  4968.1   49.53  4976.3   48.15  4976.6   47.65  4980.6   47.65    4981   48.15
  4989.1   49.66    4997   50.46  5002.2   50.46  5009.8   51.18  5032.6   52.26
  5080.8   53.89  5101.1   55.17  5141.6   56.61  5154.3   57.44  5202.4    59.2
  5232.9   61.22  5270.9   64.62  5275.9   64.41  5283.5   64.92  5303.8   65.69
#Mann= 3 ,-1 , 0
  4683.5     .05       0  4976.3     .05       0    4981     .05       0
Bank Sta=4976.3,4981
XS Rating Curve= 0 ,0
Exp/Cntr=0.3,0.1

Type RM Length L Ch R = 1 ,7048    ,182,182,182
BEGIN DESCRIPTION:
Mapping XS f34c6c35
END DESCRIPTION:
XS GIS Cut Line= 4
      2607954.23     13417185.32      2608264.11     13416969.18
       2608446.4     13416763.45      2608542.76     13416331.14
#Sta/Elev= 30
  4530.8   74.15  4610.5   72.61    4682   69.64  4717.8   67.08  4726.5   65.41
  4732.6   66.83  4747.5   63.57  4753.6   64.48  4762.3   63.17  4768.4   63.79
  4783.2   61.41  4789.3   62.32  4804.2   61.86    4819   59.66  4825.1   60.19
  4854.8   58.44  4905.4   53.59  4947.6    53.6  4990.3   47.96  5004.5   48.17
  5023.1   46.56  5023.4   46.06  5027.8   46.56  5039.6   49.36  5053.8   50.66
  5160.1    54.3  5242.1   59.06  5387.9    58.4  5530.2   61.49  5626.4   64.83
#Mann= 3 ,-1 , 0
  4530.8     .05       0  5023.1     .05       0  5027.8     .05       0
Bank Sta=5023.1,5027.8
XS Rating Curve= 0 ,0
Exp/Cntr=0.3,0.1

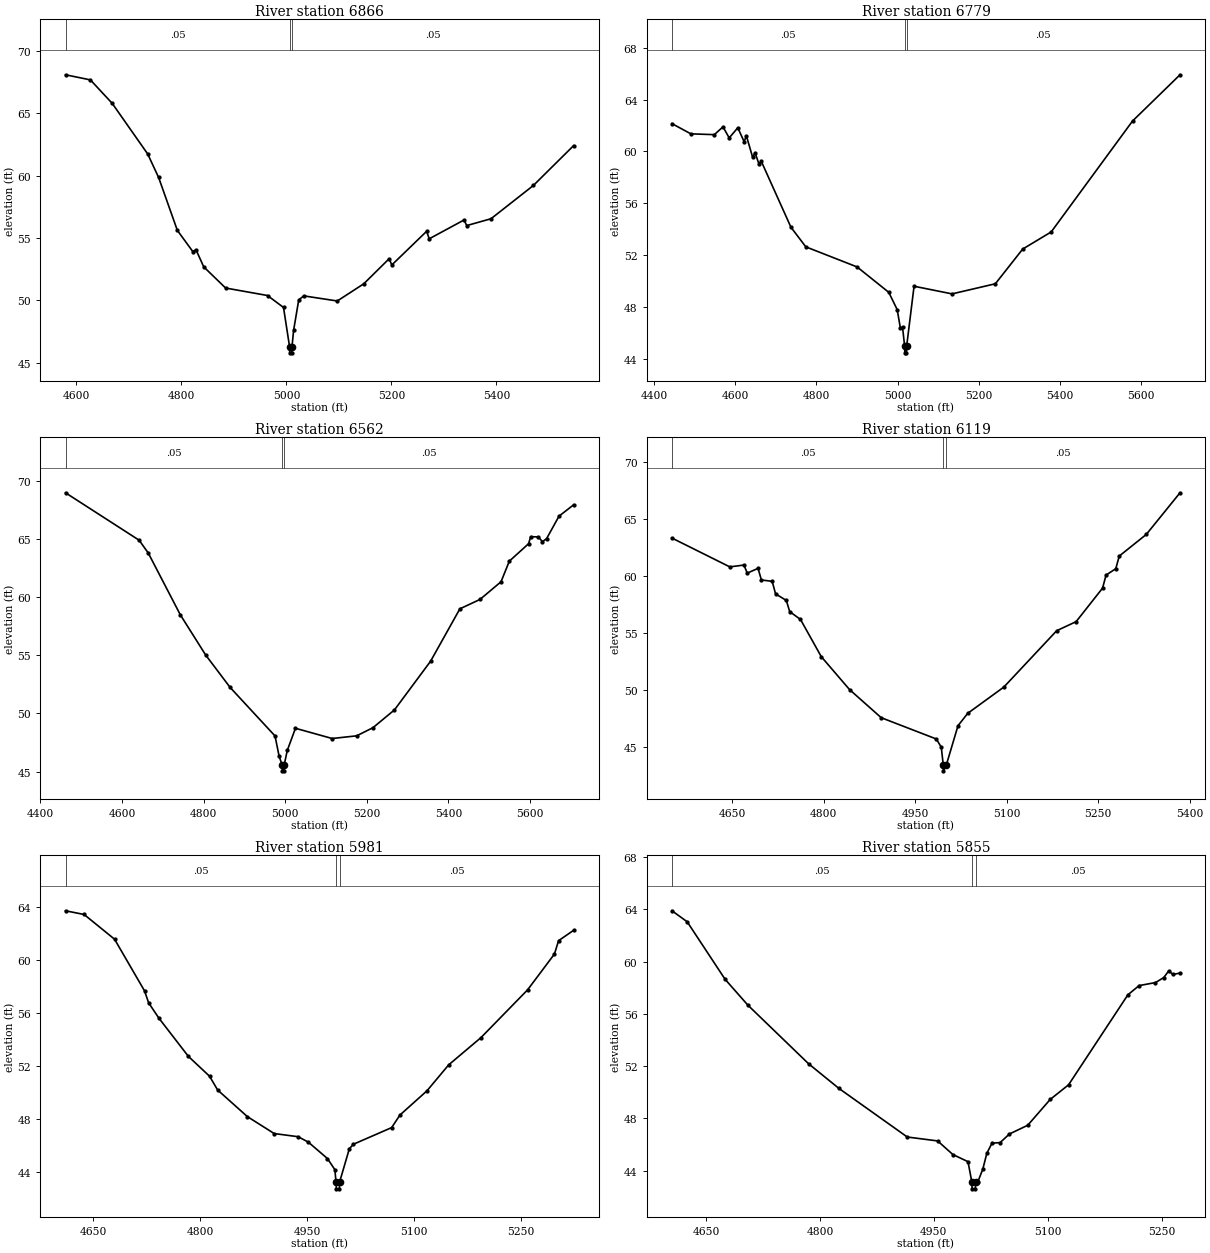
Type RM Length L Ch R = 1 ,6866    ,87,87,87
BEGIN DESCRIPTION:
Mapping XS d511c46f
END DESCRIPTION:
XS GIS Cut Line= 4
      2608127.94      13417225.1      2608464.72     13416982.06
       2608492.5     13416909.14      2608558.38     13416439.29
#Sta/Elev= 30
  4579.1   68.09  4626.5   67.68    4668    65.8  4735.6   61.74  4756.5   59.85
  4792.1   55.61  4821.5   53.91  4827.7   54.05  4842.4   52.68  4884.1   50.98
  4963.9   50.38  4994.4   49.42  5005.9   46.28  5006.3   45.78  5010.3   45.78
  5010.6   46.28  5013.6   47.58  5023.4   50.03    5033   50.35  5096.8   49.94
  5147.3   51.32  5195.6   53.33  5200.7   52.83    5267   55.53    5272   54.93
  5338.3   56.44  5343.4   55.99  5389.7   56.54  5470.4   59.21  5546.9    62.4
#Mann= 3 ,-1 , 0
  4579.1     .05       0  5005.9     .05       0  5010.6     .05       0
Bank Sta=5005.9,5010.6
XS Rating Curve= 0 ,0
Exp/Cntr=0.3,0.1

Type RM Length L Ch R = 1 ,6779    ,217,217,217
BEGIN DESCRIPTION:
Mapping XS 394c2e0c
END DESCRIPTION:
XS GIS Cut Line= 4
      2608141.71     13417375.44      2608501.09     13417151.47
      2608602.65      13416794.7      2608574.12      13416338.2
#Sta/Elev= 30
  4444.2   62.15  4490.8   61.36  4548.6    61.3  4569.9    61.9  4585.2   61.05
  4606.4   61.83  4621.8   60.77  4627.7   61.19    4643   59.55  4648.9   59.91
  4658.4   59.04  4664.3   59.24  4737.4   54.15    4774   52.64  4900.3   51.09
  4978.4   49.13  4999.2   47.79  5007.1   46.35  5012.3   46.45  5017.5   44.96
  5017.9   44.46    5022   44.46  5022.4   44.96  5040.7    49.6  5134.3   49.01
    5241   49.79  5308.4   52.47  5378.6   53.79    5579   62.35    5696   65.92
#Mann= 3 ,-1 , 0
  4444.2     .05       0  5017.5     .05       0  5022.4     .05       0
Bank Sta=5017.5,5022.4
XS Rating Curve= 0 ,0
Exp/Cntr=0.3,0.1

Type RM Length L Ch R = 1 ,6562    ,443,443,443
BEGIN DESCRIPTION:
Mapping XS 26879dd0
END DESCRIPTION:
XS GIS Cut Line= 4
      2608842.23     13417448.34      2608714.63     13417193.14
      2608706.82     13416672.31      2608631.29     13416239.97
#Sta/Elev= 30
  4461.4   68.97  4641.9   64.89  4664.2   63.79  4742.9   58.47  4804.9   55.02
  4864.9   52.23  4974.9   48.06  4984.9   46.32  4992.4   45.56  4992.8   45.06
    4997   45.06  4997.3   45.56  5004.9   46.81  5024.9   48.72  5114.9   47.84
  5174.9   48.07  5214.9   48.77  5267.6    50.3  5356.2   54.49  5427.9   58.99
  5477.3    59.8  5528.8   61.32  5549.1   63.09  5596.3   64.59  5601.4   65.19
  5620.2   65.18  5630.3   64.76  5640.5   65.03  5670.9   66.96  5706.5   67.93
#Mann= 3 ,-1 , 0
  4461.4     .05       0  4992.4     .05       0  4997.3     .05       0
Bank Sta=4992.4,4997.3
XS Rating Curve= 0 ,0
Exp/Cntr=0.3,0.1

Type RM Length L Ch R = 1 ,6119    ,138,138,138
BEGIN DESCRIPTION:
Mapping XS 3308328a
END DESCRIPTION:
XS GIS Cut Line= 3
      2609058.39     13416987.43      2608909.95     13416656.68
      2608679.09     13416246.86
#Sta/Elev= 30
  4551.5   63.32  4646.3   60.79  4669.5   60.95  4674.9   60.24  4692.6   60.66
  4698.1   59.64  4715.8   59.52  4721.3   58.42    4739   57.84  4744.5   56.86
  4762.2   56.17  4796.3    52.9  4842.6   50.01  4894.5   47.54  4984.8   45.67
    4993   44.95  4996.3   43.37  4996.6   42.87  5001.2   43.37  5020.4   46.83
  5036.3   47.92  5095.6   50.23  5182.2   55.18  5214.1   55.98  5257.4   58.92
  5263.2   60.07  5279.1   60.63  5284.8   61.74  5329.1   63.64  5384.4    67.3
#Mann= 3 ,-1 , 0
  4551.5     .05       0  4996.3     .05       0  5001.2     .05       0
Bank Sta=4996.3,5001.2
XS Rating Curve= 0 ,0
Exp/Cntr=0.3,0.1

Type RM Length L Ch R = 1 ,5981    ,126,126,126
BEGIN DESCRIPTION:
Mapping XS a790a80f
END DESCRIPTION:
XS GIS Cut Line= 3
      2609056.44     13416862.96      2608971.36     13416494.88
      2608809.94     13416201.55
#Sta/Elev= 30
  4611.2   63.75  4637.3   63.47    4680    61.6    4722    57.7  4727.9   56.78
  4742.5   55.61  4783.6   52.74  4813.3   51.24  4824.6    50.2  4866.3   48.19
  4903.9   46.91  4937.5   46.67  4951.8   46.26  4978.6   45.02    4989   44.18
  4990.7   43.23  4991.1   42.73  4995.3   42.73  4995.6   43.23  5009.3   45.76
    5015    46.1  5068.7   47.36  5080.3   48.31  5118.2   50.14  5148.6    52.1
  5193.9   54.16  5259.3   57.77    5297   60.48  5302.8   61.49  5323.8   62.27
#Mann= 3 ,-1 , 0
  4611.2     .05       0  4990.7     .05       0  4995.6     .05       0
Bank Sta=4990.7,4995.6
XS Rating Curve= 0 ,0
Exp/Cntr=0.3,0.1

Type RM Length L Ch R = 1 ,5855    ,201,201,201
BEGIN DESCRIPTION:
TRIB 2-4 TO GUADALUPE RIVER 8.0
END DESCRIPTION:
XS GIS Cut Line= 3
        2609075.     13416825.04        2609075.       13416425.
        2608975.     13416174.99
#Sta/Elev= 30
    4605    63.9    4625   63.06    4675   58.65    4705   56.67    4785   52.18
    4825   50.29    4915   46.57    4955   46.27    4975   45.23    4995   44.68
  5000.1    43.1  5000.4    42.6  5004.6    42.6    5005    43.1  5007.7    43.1
  5014.5   44.11  5019.8   45.32  5026.6    46.1  5037.3   46.14  5049.5    46.8
  5073.7   47.47  5103.3   49.45  5127.5   50.57  5205.6   57.46  5220.4   58.17
    5242    58.4  5252.8   58.78  5259.5    59.3  5264.9   59.02  5274.3   59.13
#Mann= 3 ,-1 , 0
    4605     .05       0  5000.1     .05       0    5005     .05       0
Bank Sta=5000.1,5005
XS Rating Curve= 0 ,0
Exp/Cntr=0.3,0.1

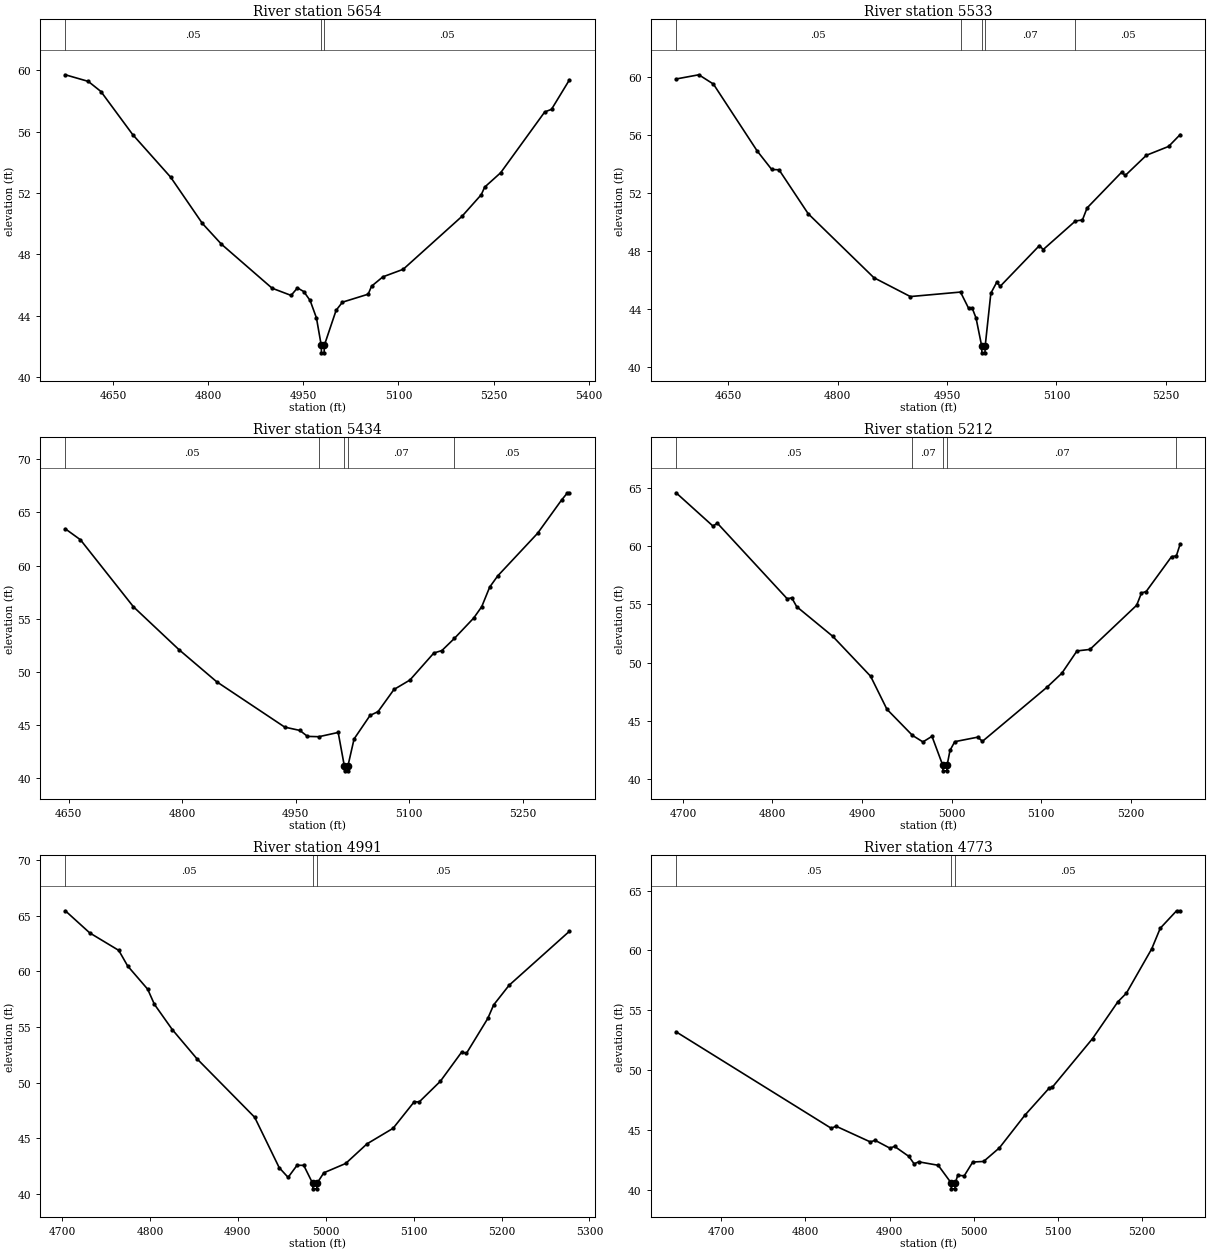
Type RM Length L Ch R = 1 ,5654    ,121,121,121
BEGIN DESCRIPTION:
Mapping XS f3092ff0
END DESCRIPTION:
XS GIS Cut Line= 3
       2609242.5     13416751.19      2609240.76     13416331.02
      2609112.85     13415978.38
#Sta/Elev= 30
  4574.5    59.7  4610.7   59.27  4630.7   58.61  4680.7   55.81  4740.7   53.03
  4790.7   50.02  4820.7   48.67  4900.7    45.8  4930.7   45.33  4940.7   45.82
  4950.7   45.58  4960.7      45  4970.7   43.86  4978.2   42.09  4978.6   41.59
  4982.8   41.59  4983.2   42.09  5001.7   44.36  5011.7   44.89  5052.3   45.41
  5057.6   45.93  5075.5   46.54  5107.5   47.03    5200   50.47  5230.7   51.89
    5236   52.38  5261.3   53.32  5330.8   57.28  5341.5   57.45  5369.8   59.37
#Mann= 3 ,-1 , 0
  4574.5     .05       0  4978.2     .05       0  4983.2     .05       0
Bank Sta=4978.2,4983.2
XS Rating Curve= 0 ,0
Exp/Cntr=0.3,0.1

Type RM Length L Ch R = 1 ,5533    ,99,99,99
BEGIN DESCRIPTION:
Mapping XS c4348c8f
END DESCRIPTION:
XS GIS Cut Line= 3
      2609353.31     13416696.22      2609346.36     13416290.01
      2609296.12     13416009.34
#Sta/Elev= 30
  4578.3   59.84  4609.5   60.13  4629.5   59.49  4689.5   54.88  4709.5    53.6
  4719.5   53.58  4759.5   50.55  4849.6   46.14  4899.6   44.84  4968.4   45.15
  4979.6   44.02  4984.6   44.02  4989.7   43.36  4997.3   41.46  4997.7   40.96
  5001.9   40.96  5002.3   41.46    5010   45.07  5017.9   45.81  5022.9   45.55
  5076.7   48.36  5081.8   48.08    5126   50.05  5135.6   50.12    5142   50.95
  5189.3   53.41  5194.4   53.19  5223.3   54.58  5253.8   55.19  5269.7   56.01
#Mann= 5 ,-1 , 0
  4578.3     .05       0  4968.4     .07       0  4997.3     .05       0
  5002.3     .07       0    5126     .05       0
Bank Sta=4997.3,5002.3
XS Rating Curve= 0 ,0
Exp/Cntr=0.3,0.1

Type RM Length L Ch R = 1 ,5434    ,222,222,222
BEGIN DESCRIPTION:
TRIB 2-4 TO GUADALUPE RIVER 7.0
END DESCRIPTION:
XS GIS Cut Line= 3
        2609425.     13416675.01        2609425.       13416325.
      2609524.99     13416025.04
#Sta/Elev= 30
  4645.4   63.45  4665.4   62.42  4735.4   56.12  4795.4    52.1  4845.4   49.07
  4935.4    44.8  4955.4   44.49  4965.4   43.93  4980.5    43.9    5006    44.3
    5014   41.19  5014.4   40.69  5018.6   40.69    5019   41.19    5027   43.69
  5048.1    45.9  5058.7   46.26  5079.7   48.34  5100.8   49.23  5132.4   51.77
    5143      52  5159.5   53.14  5185.1   55.06  5195.7   56.13  5206.2   57.97
  5216.8   59.02  5269.5   63.03  5301.1   66.15    5309   66.84  5311.6   66.84
#Mann= 5 ,-1 , 0
  4645.4     .05       0  4980.5     .07       0    5014     .05       0
    5019     .07       0  5159.5     .05       0
Bank Sta=5014,5019
XS Rating Curve= 0 ,0
Exp/Cntr=0.3,0.1

Type RM Length L Ch R = 1 ,5212    ,221,221,221
BEGIN DESCRIPTION:
Mapping XS f4dc23ec
END DESCRIPTION:
XS GIS Cut Line= 3
      2609594.93     13416688.64      2609631.39     13416379.63
      2609702.06     13416138.32
#Sta/Elev= 30
  4692.4   64.61  4733.5   61.75  4738.5   61.99  4816.4   55.49  4821.5   55.57
    4827   54.81  4867.2   52.26  4909.5   48.82  4927.7   45.98  4956.2   43.73
  4967.9   43.17    4978   43.65  4989.9   41.18  4990.3   40.68  4994.6   40.68
  4994.9   41.18  4998.1   42.44  5003.4   43.19  5029.1   43.58  5034.3   43.22
  5106.4   47.88    5123   49.09  5139.8      51  5154.3   51.13  5206.4   54.93
  5211.8   55.99    5217   56.11  5245.3   59.11  5250.7   59.18    5255   60.21
#Mann= 5 ,-1 , 0
  4692.4     .05       0  4956.2     .07       0  4989.9     .05       0
  4994.9     .07       0  5250.7     .05       0
Bank Sta=4989.9,4994.9
XS Rating Curve= 0 ,0
Exp/Cntr=0.3,0.1

Type RM Length L Ch R = 1 ,4991    ,218,218,218
BEGIN DESCRIPTION:
TRIB 2-4 TO GUADALUPE RIVER 6.0
END DESCRIPTION:
XS GIS Cut Line= 3
      2609775.01     13416674.97        2609825.       13416375.
      2609925.01     13416124.97
#Sta/Elev= 30
  4703.8   65.45  4731.6   63.46  4764.6   61.89  4774.7   60.49  4797.5    58.4
  4805.1   57.05  4825.4   54.78  4853.3   52.17  4919.2   46.89  4947.1   42.36
  4957.2   41.49  4967.4   42.58    4975   42.57  4985.1   40.96  4985.5   40.46
  4989.8   40.46  4990.1   40.96  4997.8    41.9  5022.7   42.74  5046.9    44.5
  5076.6    45.9  5100.8    48.3  5106.2   48.26  5130.4   50.13  5154.7   52.76
    5160   52.63  5184.3   55.77    5191   56.99  5208.5   58.75  5277.2   63.61
#Mann= 3 ,-1 , 0
  4703.8     .05       0  4985.1     .05       0  4990.1     .05       0
Bank Sta=4985.1,4990.1
XS Rating Curve= 0 ,0
Exp/Cntr=0.3,0.1

Type RM Length L Ch R = 1 ,4773    ,253,253,253
BEGIN DESCRIPTION:
Mapping XS 4401fa5b
END DESCRIPTION:
XS GIS Cut Line= 3
      2610155.68      13416697.3      2610008.12     13416367.47
      2609985.56     13416131.38
#Sta/Elev= 30
  4646.5   53.19  4830.8   45.12  4836.3    45.3  4877.2   43.98  4882.7   44.12
  4900.4   43.46  4905.9   43.61  4922.9   42.77  4929.1   42.15  4934.5   42.32
  4957.7   42.03    4973   40.56  4973.3   40.06  4977.6   40.06    4978   40.56
  4980.9   41.19  4988.6   41.15  4998.7    42.3  5011.6   42.35  5030.4   43.49
  5060.5   46.21  5089.4   48.48  5093.2   48.56  5140.9   52.62    5171    55.7
  5181.1   56.42  5211.2   60.13  5221.3   61.85  5240.7   63.31    5245   63.31
#Mann= 3 ,-1 , 0
  4646.5     .05       0    4973     .05       0    4978     .05       0
Bank Sta=4973,4978
XS Rating Curve= 0 ,0
Exp/Cntr=0.3,0.1