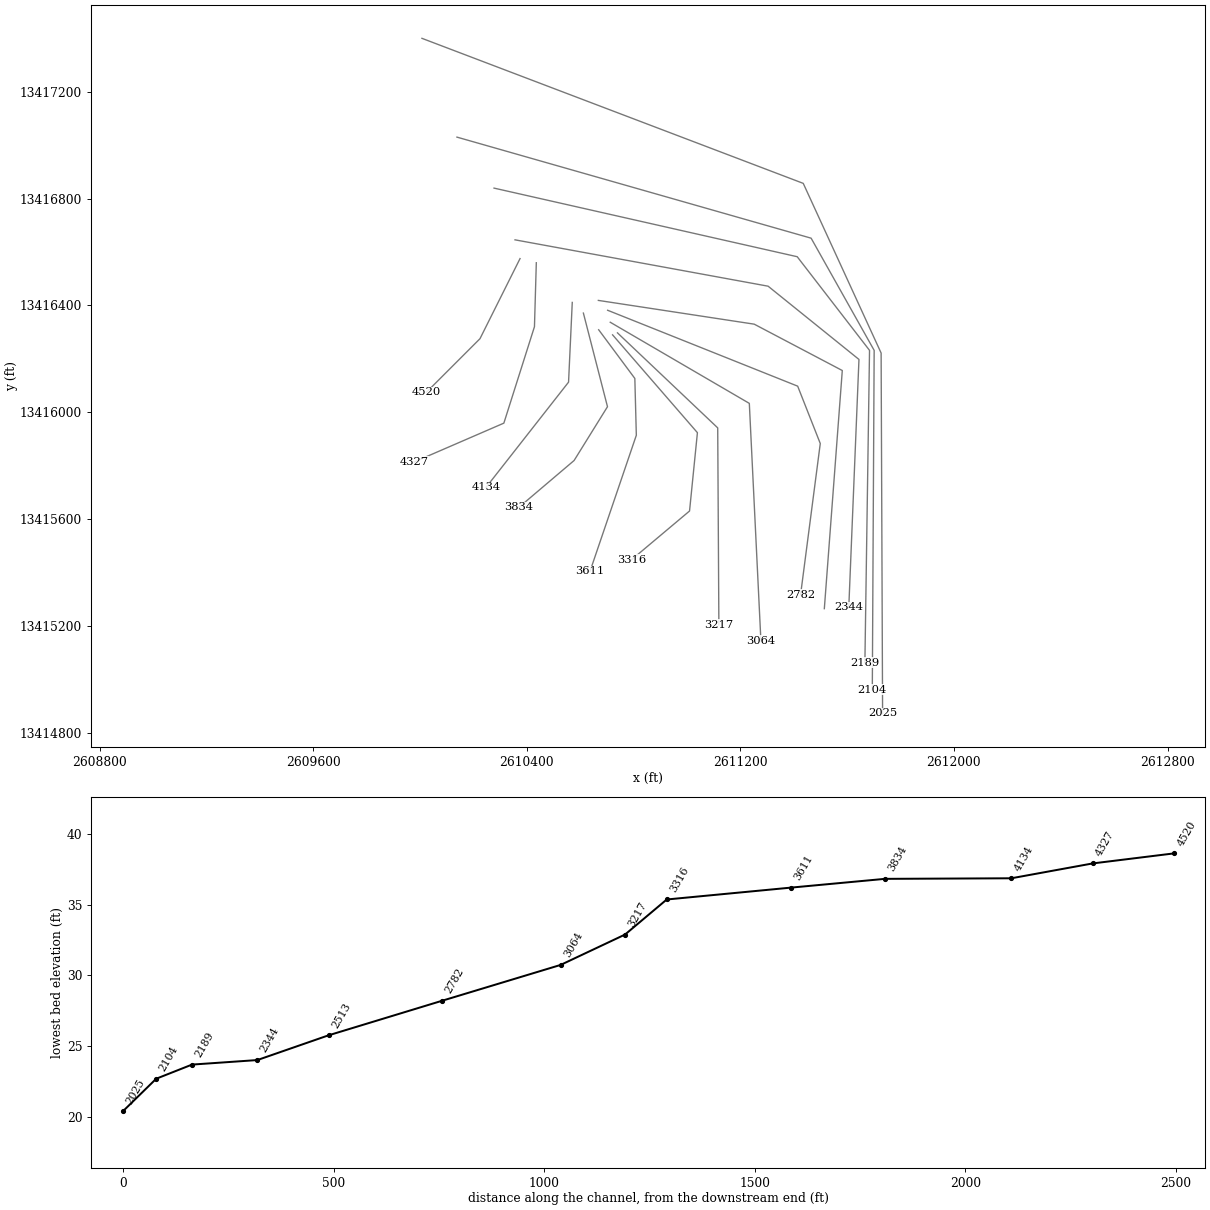
HEC-RAS study TRIB 2_4 TO GUADALUPE RIVER.prj: TRIB 2_4 TO GUADALUPE RIVER Base Level Engineering

--- TRIB 2_4 TO GUADALUPE RIVER.g01 (geometry) --- (continued)

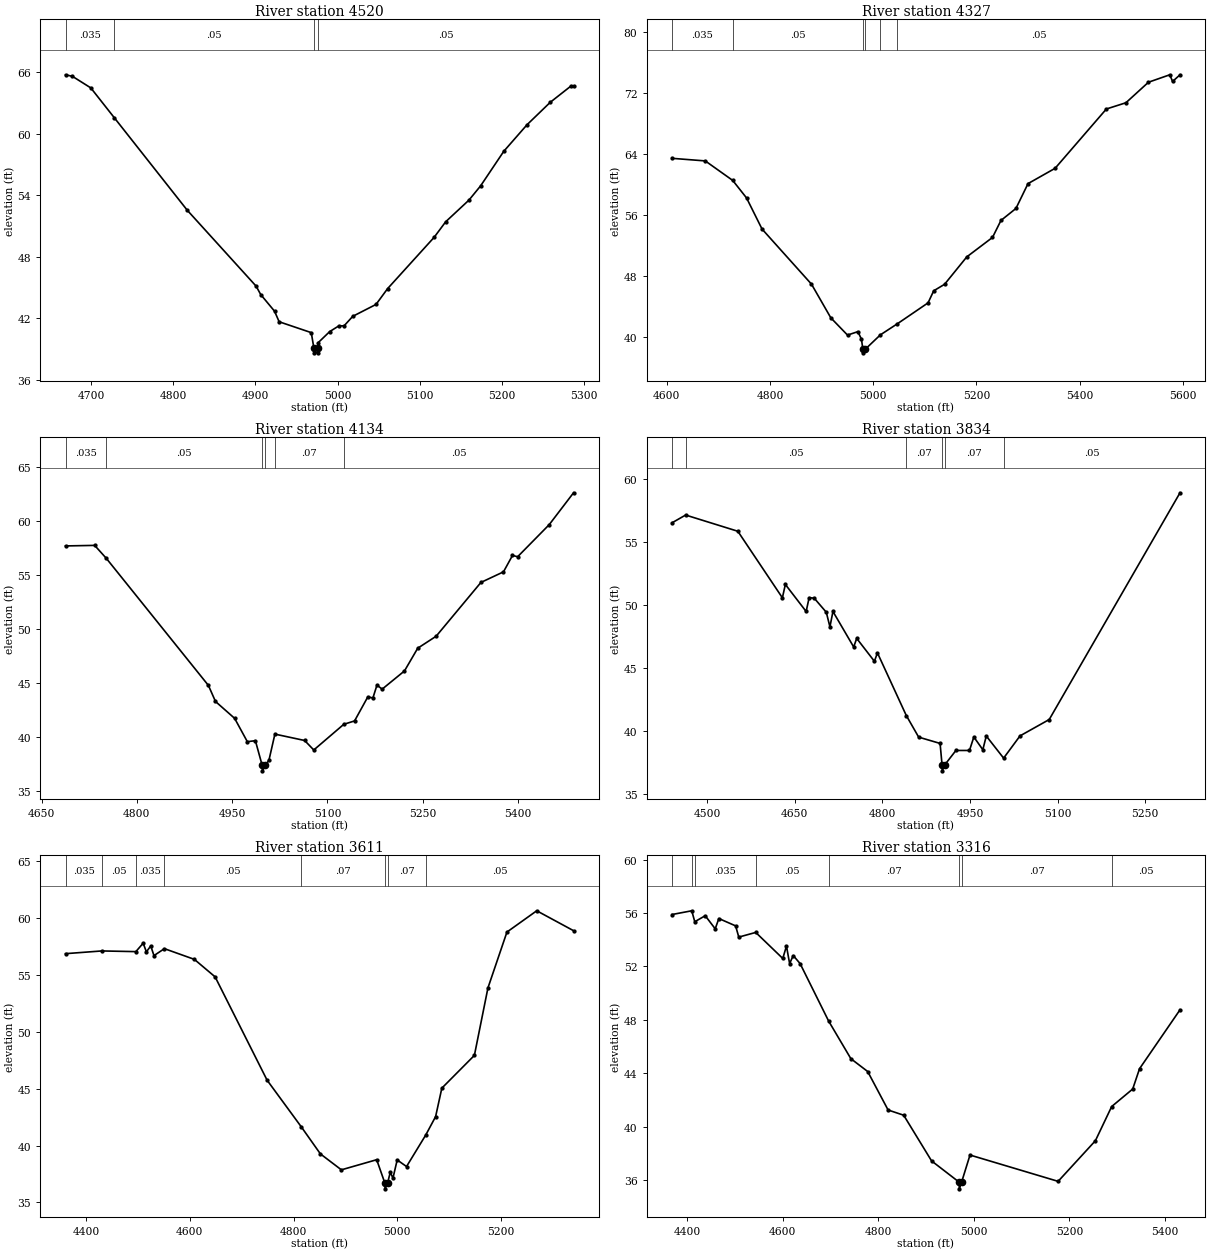
Type RM Length L Ch R = 1 ,4520    ,193,193,193
BEGIN DESCRIPTION:
TRIB 2-4 TO GUADALUPE RIVER 5.0
END DESCRIPTION:
XS GIS Cut Line= 3
      2610375.02     13416575.04        2610225.       13416275.
      2610024.99     13416074.99
#Sta/Elev= 30
  4668.9   65.73  4677.3   65.58  4699.7   64.45  4728.3   61.54  4817.1   52.52
  4900.9   45.12  4906.5    44.3  4923.3   42.68  4928.9   41.65    4968   40.59
  4971.1   39.12  4971.5   38.62  4975.8   38.62  4976.2   39.12  4976.4   39.61
  4990.4   40.69  5001.6   41.25  5007.9   41.25  5018.5   42.18  5046.8   43.34
  5060.9   44.88  5117.5   49.88  5131.6    51.4  5159.9   53.51  5174.1    54.9
  5202.3   58.27  5230.6   60.86  5258.9   63.05  5283.7   64.61  5287.2   64.61
#Mann= 4 ,-1 , 0
  4668.9    .035       0  4728.3     .05       0  4971.1     .05       0
  4976.2     .05       0
Bank Sta=4971.1,4976.2
XS Rating Curve= 0 ,0
Exp/Cntr=0.3,0.1

Type RM Length L Ch R = 1 ,4327    ,193,193,193
BEGIN DESCRIPTION:
Mapping XS 39e32f6f
END DESCRIPTION:
XS GIS Cut Line= 4
      2610435.99     13416559.44      2610429.04     13416319.88
      2610314.46     13415958.76       2609978.8     13415813.43
#Sta/Elev= 30
    4610   63.43  4674.5   63.09  4727.7   60.53  4754.5   58.23  4784.5   54.15
  4880.3   46.92  4917.8    42.5  4950.1   40.24  4970.2   40.69  4977.1    39.7
  4979.8   38.41  4980.2   37.91  4984.9   38.41  5013.8   40.27  5046.4   41.71
  5106.2   44.47  5117.1   46.05  5138.1    46.9  5181.2    50.5    5231   53.05
  5247.4   55.28  5276.4   56.85  5299.8   60.11  5352.3   62.12  5451.6    69.9
  5489.5   70.72  5533.1   73.41  5574.5   74.39  5579.9   73.51  5594.3   74.39
#Mann= 6 ,-1 , 0
    4610    .035       0  4727.7     .05       0  4979.8     .05       0
  4984.9     .05       0  5013.8     .07       0  5046.4     .05       0
Bank Sta=4979.8,4984.9
XS Rating Curve= 0 ,0
Exp/Cntr=0.3,0.1

Type RM Length L Ch R = 1 ,4134    ,300,300,300
BEGIN DESCRIPTION:
Mapping XS 377dfe53
END DESCRIPTION:
XS GIS Cut Line= 3
      2610570.62     13416410.86      2610556.74     13416112.27
      2610247.73     13415718.19
#Sta/Elev= 30
  4687.7   57.68  4733.6   57.73  4751.8   56.54  4912.6   44.77  4923.8   43.28
  4953.9   41.72  4973.9   39.56  4986.6   39.65  4997.3   37.36  4997.7   36.86
  5002.4   37.36    5008   37.86  5017.3   40.26  5064.1   39.67  5078.5   38.79
  5125.8   41.17  5142.7   41.48  5163.5    43.7  5171.6   43.61    5178    44.8
  5186.1   44.42  5221.3   46.11  5242.1   48.21  5271.1   49.32  5341.6    54.3
  5377.1   55.28  5391.3    56.8  5399.4   56.68  5449.1   59.65  5487.4    62.6
#Mann= 6 ,-1 , 0
  4687.7    .035       0  4751.8     .05       0  4997.3     .05       0
  5002.4     .05       0  5017.3     .07       0  5125.8     .05       0
Bank Sta=4997.3,5002.4
XS Rating Curve= 0 ,0
Exp/Cntr=0.3,0.1

Type RM Length L Ch R = 1 ,3834    ,223,223,223
BEGIN DESCRIPTION:
Mapping XS 2f607cb2
END DESCRIPTION:
XS GIS Cut Line= 4
       2610612.3     13416370.91      2610702.57     13416020.25
      2610577.57     13415818.86      2610370.97     13415643.51
#Sta/Elev= 30
  4439.7   56.54  4463.1   57.16  4552.5   55.87  4628.8   50.58  4633.9   51.64
  4669.5   49.49  4674.6   50.59  4683.3   50.55    4704   49.43  4710.2   48.27
  4715.4   49.49  4750.9   46.67  4756.1   47.35  4786.4   45.53  4791.6    46.2
    4841   41.22  4862.2    39.5  4898.9      39  4902.2   37.32  4902.6   36.82
  4907.3   37.32    4926   38.44  4949.2   38.44  4956.7   39.51  4972.1    38.5
    4978   39.59  5007.7   37.83  5035.8    39.6  5085.8    40.9  5309.8   58.93
#Mann= 6 ,-1 , 0
  4439.7    .035       0  4463.1     .05       0    4841     .07       0
  4902.2     .05       0  4907.3     .07       0  5007.7     .05       0
Bank Sta=4902.2,4907.3
XS Rating Curve= 0 ,0
Exp/Cntr=0.3,0.1

Type RM Length L Ch R = 1 ,3611    ,295,295,295
BEGIN DESCRIPTION:
Mapping XS 8bf08702
END DESCRIPTION:
XS GIS Cut Line= 4
      2610669.59     13416308.43        2610805.     13416126.15
      2610810.59     13415913.41      2610636.99     13415403.44
#Sta/Elev= 30
  4360.8   56.87  4430.9   57.11  4496.3   57.05  4510.4   57.79  4516.6   57.03
    4525   57.55  4531.2    56.7  4551.3   57.31    4609   56.37    4649   54.83
  4749.1   45.75  4815.1   41.64  4851.8   39.27  4892.2   37.87  4960.2   38.76
    4976    36.7  4976.4    36.2  4981.1    36.7  4986.3   37.64  4991.6   37.15
  4999.7   38.74  5017.7   38.16  5054.7   40.93  5073.7   42.55  5085.7   45.05
  5148.4   47.93  5174.5   53.86  5211.1   58.77  5268.5   60.64  5339.4   58.89
#Mann= 8 ,-1 , 0
  4360.8    .035       0  4430.9     .05       0  4496.3    .035       0
  4551.3     .05       0  4815.1     .07       0    4976     .05       0
  4981.1     .07       0  5054.7     .05       0
Bank Sta=4976,4981.1
XS Rating Curve= 0 ,0
Exp/Cntr=0.3,0.1

Type RM Length L Ch R = 1 ,3316    ,99,99,99
BEGIN DESCRIPTION:
Mapping XS eb5976bc
END DESCRIPTION:
XS GIS Cut Line= 4
      2610721.64     13416289.38      2611039.37     13415923.03
      2611009.86     13415629.63      2610792.88     13415447.37
#Sta/Elev= 30
  4368.2   55.89  4409.6   56.17  4415.9   55.35  4437.8    55.8  4458.7   54.82
  4466.3   55.59  4501.4   55.04    4508    54.2  4543.5   54.55  4600.1    52.6
  4607.8   53.53  4614.4   52.22    4622   52.82  4636.3   52.22    4696   47.92
  4742.6    45.1  4777.8   44.14  4820.5   41.26  4853.1   40.87  4911.5   37.45
  4969.2   35.86  4969.6   35.36  4974.3   35.86  4991.9   37.89  5176.3   35.92
  5254.3   38.96  5288.4   41.52  5332.4   42.83  5346.7   44.35  5431.4   48.76
#Mann= 8 ,-1 , 0
  4368.2    .035       0  4409.6     .07       0  4415.9    .035       0
  4543.5     .05       0    4696     .07       0  4969.2     .05       0
  4974.3     .07       0  5288.4     .05       0
Bank Sta=4969.2,4974.3
XS Rating Curve= 0 ,0
Exp/Cntr=0.3,0.1

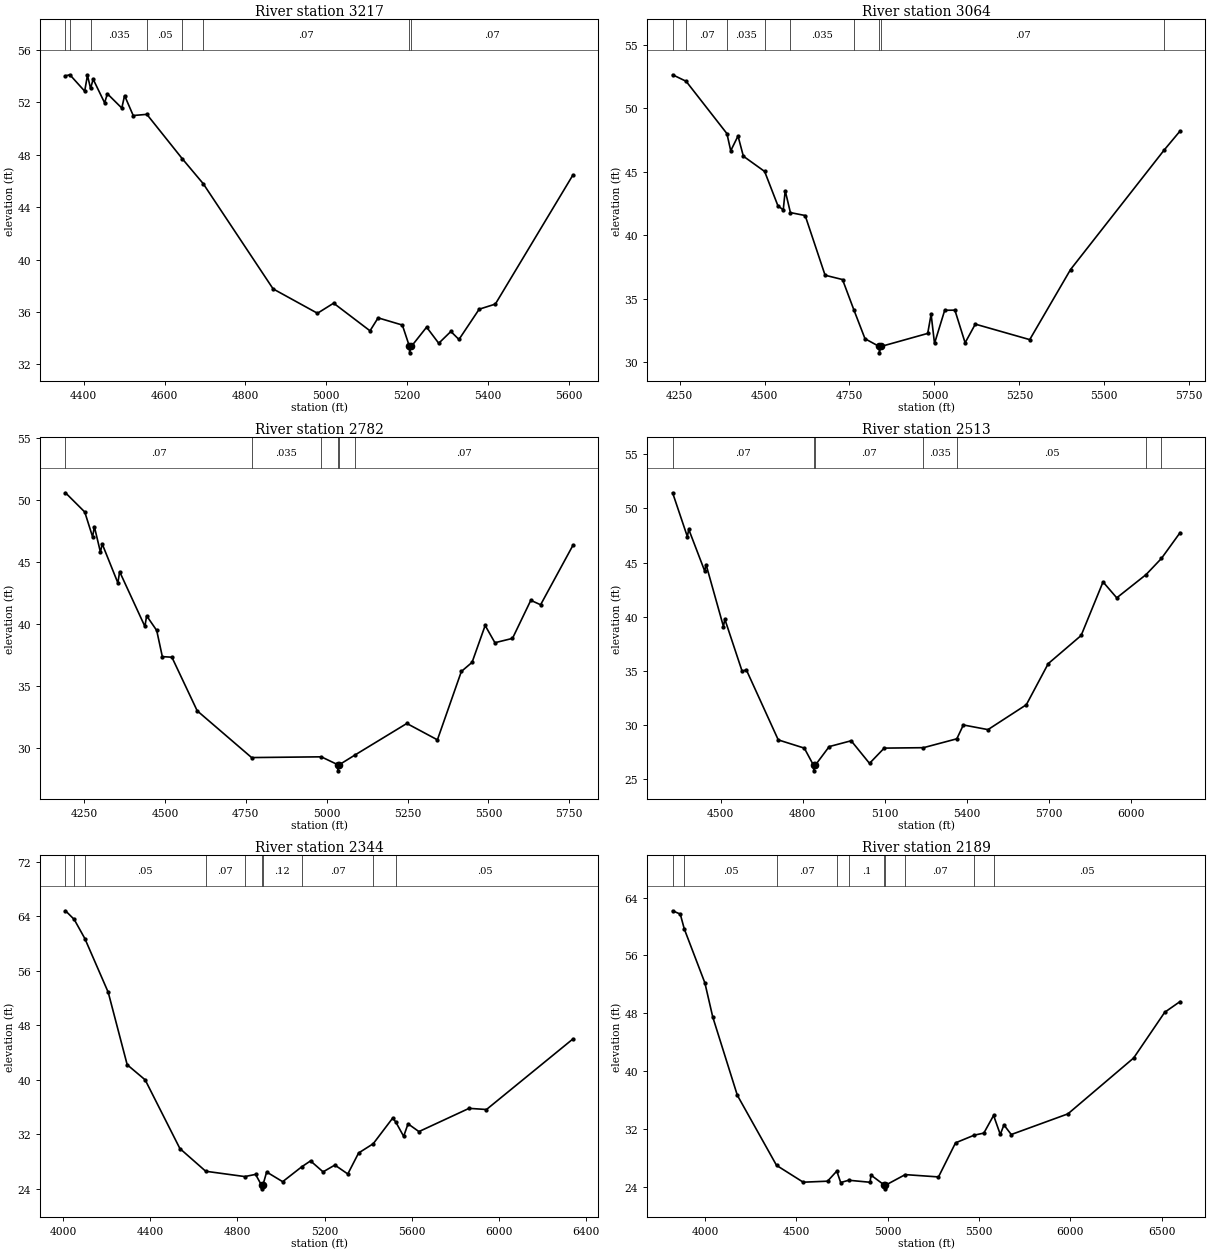
Type RM Length L Ch R = 1 ,3217    ,153,153,153
BEGIN DESCRIPTION:
Mapping XS aaa19b7a
END DESCRIPTION:
XS GIS Cut Line= 3
      2610739.97     13416296.87       2611115.4     13415940.97
      2611119.74     13415203.09
#Sta/Elev= 30
    4355   54.02  4365.9    54.1  4402.5   52.85  4409.4   54.06    4417   53.06
  4423.5   53.76  4451.8   51.96  4458.7   52.65  4494.3   51.56  4501.2   52.51
  4522.6   50.99  4556.3   51.08    4644   47.69  4695.7   45.79  4868.6   37.76
  4978.3    35.9  5018.3   36.67  5108.3   34.56  5128.3   35.55  5188.3      35
  5205.7   33.38  5206.1   32.88  5210.8   33.38  5248.3   34.84  5278.3   33.61
  5308.3   34.51  5328.3    33.9  5378.3   36.21  5418.3    36.6  5610.2   46.45
#Mann= 8 ,-1 , 0
    4355    .035       0  4365.9     .07       0    4417    .035       0
  4556.3     .05       0    4644    .035       0  4695.7     .07       0
  5205.7     .05       0  5210.8     .07       0
Bank Sta=5205.7,5210.8
XS Rating Curve= 0 ,0
Exp/Cntr=0.3,0.1

Type RM Length L Ch R = 1 ,3064    ,282,282,282
BEGIN DESCRIPTION:
Mapping XS 6b797b7e
END DESCRIPTION:
XS GIS Cut Line= 3
       2610712.9     13416336.61      2611233.77     13416032.76
      2611277.17     13415143.04
#Sta/Elev= 30
  4229.3   52.62    4269   52.11  4389.2   47.99  4400.4   46.64  4421.9    47.8
  4437.6   46.21  4500.2   45.01  4539.3   42.31    4555   41.98  4560.8   43.49
  4576.1   41.77  4619.5   41.54  4678.2   36.84  4729.5    36.5  4763.1    34.1
  4795.7   31.84  4837.5   31.23  4837.9   30.73  4842.6   31.23  4980.3   32.26
  4990.3   33.77  5000.3   31.47  5030.3   34.08  5060.3   34.09  5090.4   31.52
  5120.4   32.99  5280.6   31.77  5400.8   37.29  5676.5    46.7  5723.1   48.19
#Mann= 9 ,-1 , 0
  4229.3    .035       0    4269     .07       0  4389.2    .035       0
  4500.2     .07       0  4576.1    .035       0  4763.1     .07       0
  4837.5     .05       0  4842.6     .07       0  5676.5     .05       0
Bank Sta=4837.5,4842.6
XS Rating Curve= 0 ,0
Exp/Cntr=0.3,0.1

Type RM Length L Ch R = 1 ,2782    ,269,269,269
BEGIN DESCRIPTION:
Mapping XS 2efdfa55
END DESCRIPTION:
XS GIS Cut Line= 4
       2610703.1      13416381.5      2611414.88     13416097.22
      2611499.51     13415882.38      2611425.72     13415315.93
#Sta/Elev= 30
  4192.5   50.61  4252.1   49.06  4276.4   47.05  4281.8   47.88  4300.6   45.82
    4306   46.49  4354.5   43.34  4359.9   44.25    4438   39.83  4443.4   40.69
  4474.5   39.51  4491.9    37.4  4521.5   37.35  4599.7   33.03  4767.9   29.26
  4983.3   29.32  5033.8   28.69  5034.3   28.19  5039.3   28.69  5088.2   29.48
  5247.7   32.01  5342.2   30.69  5416.2    36.2  5449.4   36.94  5489.8   39.91
    5520   38.52  5574.3   38.87  5630.9   41.94  5661.2   41.58  5761.1   46.37
#Mann= 6 ,-1 , 0
  4192.5     .07       0  4767.9    .035       0  4983.3     .05       0
  5033.8     .05       0  5039.3     .05       0  5088.2     .07       0
Bank Sta=5033.8,5039.3
XS Rating Curve= 0 ,0
Exp/Cntr=0.3,0.1

Type RM Length L Ch R = 1 ,2513    ,169,169,169
BEGIN DESCRIPTION:
Mapping XS 13694d3b
END DESCRIPTION:
XS GIS Cut Line= 4
      2610668.35      13416418.4      2611252.12     13416329.43
      2611581.98     13416155.81      2611514.71     13415263.91
#Sta/Elev= 30
  4323.5   51.45  4377.5    47.4  4382.6   48.07    4441   44.22  4446.1   44.81
  4509.6   39.09  4514.7   39.77  4578.2   34.94  4593.2    35.1  4710.3   28.61
  4805.7   27.85  4839.7   26.25  4840.1   25.75  4845.2   26.25  4896.7   27.99
  4977.2   28.53  5044.4   26.44  5098.1   27.85  5241.8   27.89    5364   28.71
  5387.9   29.99  5478.1   29.56  5618.5   31.86  5698.7   35.66  5819.1   38.26
  5899.3   43.21  5949.5   41.74  6056.9   43.89    6113   45.38  6181.2   47.76
#Mann= 7 ,-1 , 0
  4323.5     .07       0  4839.7     .05       0  4845.2     .07       0
  5241.8    .035       0    5364     .05       0  6056.9     .07       0
    6113     .05       0
Bank Sta=4839.7,4845.2
XS Rating Curve= 0 ,0
Exp/Cntr=0.3,0.1

Type RM Length L Ch R = 1 ,2344    ,155,155,155
BEGIN DESCRIPTION:
Mapping XS 27439e2e
END DESCRIPTION:
XS GIS Cut Line= 4
      2610356.21     13416645.25      2611304.13     13416471.64
      2611644.41     13416197.34      2611606.28     13415268.38
#Sta/Elev= 30
    4010    64.8  4049.9   63.54    4099   60.72  4206.4   52.83  4293.4   42.21
    4376   39.99  4535.5   29.91  4654.1   26.58  4833.5    25.8  4883.1   26.12
  4910.8    24.5  4911.3      24  4916.3    24.5  4933.9   26.47  5007.5   25.05
  5095.3   27.24  5135.5    28.1  5193.1   26.49  5247.2   27.49  5306.6   26.18
  5356.2   29.26  5423.4   30.62  5513.2    34.4  5527.7   33.76  5563.2    31.7
  5583.2   33.54  5633.3    32.4  5863.5   35.81  5943.5   35.64  6340.5   45.99
#Mann= 10 ,-1 , 0
    4010     .05       0  4049.9    .035       0    4099     .05       0
  4654.1     .07       0  4833.5     .12       0  4910.8     .05       0
  4916.3     .12       0  5095.3     .07       0  5423.4    .035       0
  5527.7     .05       0
Bank Sta=4910.8,4916.3
XS Rating Curve= 0 ,0
Exp/Cntr=0.3,0.1

Type RM Length L Ch R = 1 ,2189    ,85,85,85
BEGIN DESCRIPTION:
Mapping XS 8fa15ab6
END DESCRIPTION:
XS GIS Cut Line= 4
       2610277.7     13416838.98      2611413.14     13416582.03
      2611683.98     13416231.34      2611666.61     13415061.22
#Sta/Elev= 30
  3822.2   62.18  3864.2   61.72  3886.2   59.66  3998.8    52.2    4042   47.47
  4176.6   36.63  4391.1   26.93  4537.1    24.6  4670.4   24.74  4720.9   26.14
  4742.2   24.55  4786.2   24.87    4903   24.59  4908.2   25.58    4982   24.18
  4982.4   23.68  4987.5   24.18  5095.4   25.65  5277.6   25.33  5370.9   30.05
    5473   31.11  5525.8    31.4  5579.1   33.84  5615.8   31.21  5635.8   32.53
  5675.8    31.2  5985.9   34.06  6345.9    41.8  6515.9   48.13  6599.7   49.61
#Mann= 10 ,-1 , 0
  3822.2    .035       0  3886.2     .05       0  4391.1     .07       0
  4720.9     .12       0  4786.2      .1       0    4982     .05       0
  4987.5      .1       0  5095.4     .07       0    5473    .035       0
  5579.1     .05       0
Bank Sta=4982,4987.5
XS Rating Curve= 0 ,0
Exp/Cntr=0.3,0.1

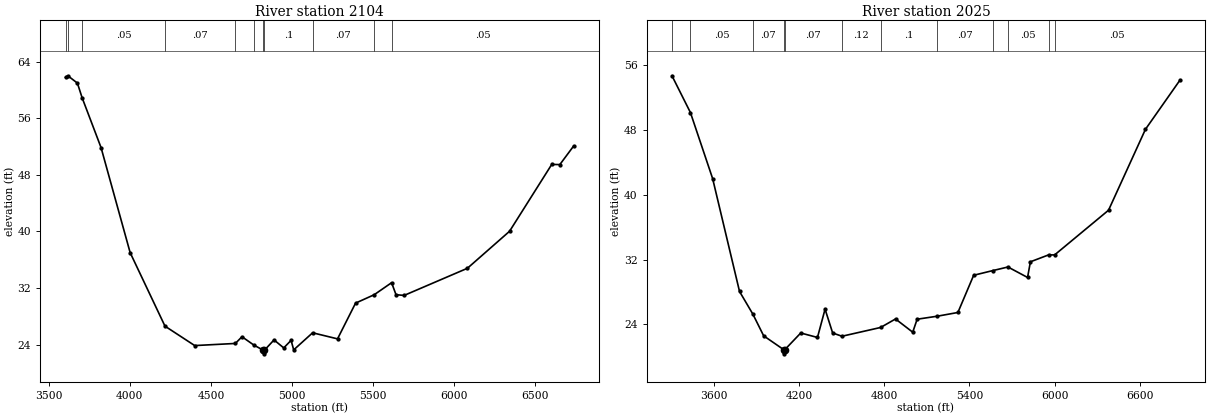
Type RM Length L Ch R = 1 ,2104    ,79,79,79
BEGIN DESCRIPTION:
Mapping XS 0a52b3bf
END DESCRIPTION:
XS GIS Cut Line= 4
      2610138.79     13417029.96      2611465.23     13416651.47
      2611701.34     13416231.34      2611694.39     13414960.47
#Sta/Elev= 30
  3603.6   61.81  3618.2   62.04    3677      61  3705.7   58.95  3822.7   51.88
  4002.2      37  4216.9    26.6  4400.2   23.85  4650.7   24.15  4691.6    25.1
  4764.9   23.92    4824   23.18  4824.5   22.68  4829.5   23.18  4889.2   24.65
  4949.1   23.52  4994.4   24.59  5010.4   23.24  5127.1   25.66  5280.7    24.8
  5391.9   29.86    5507   31.05    5614   32.75  5641.3   31.05  5691.3   30.95
  6081.3   34.79  6341.3   40.03  6601.3   49.49  6651.3   49.47  6735.8   52.08
#Mann= 11 ,-1 , 0
  3603.6     .05       0  3618.2    .035       0  3705.7     .05       0
  4216.9     .07       0  4650.7     .12       0  4764.9      .1       0
    4824     .05       0  4829.5      .1       0  5127.1     .07       0
    5507    .035       0    5614     .05       0
Bank Sta=4824,4829.5
XS Rating Curve= 0 ,0
Exp/Cntr=0.3,0.1

Type RM Length L Ch R = 1 ,2025    ,0,0,0
BEGIN DESCRIPTION:
TRIB 2-4 TO GUADALUPE RIVER 1.0
END DESCRIPTION:
XS GIS Cut Line= 4
      2610007.65     13417399.95      2611435.74     13416856.75
      2611727.41     13416221.33       2611732.9     13414871.71
#Sta/Elev= 30
  3306.2   54.67    3436   50.14  3592.5   41.99  3781.8   28.07  3875.9   25.27
  3951.8    22.6  4094.3   20.88  4094.7   20.38  4099.8   20.88  4212.8   22.95
  4330.5    22.4    4384   25.89  4437.5   22.95  4503.2   22.55  4774.8   23.63
    4880   24.68  5001.1   23.05  5032.3   24.65  5173.7   25.02  5319.2   25.48
  5430.2   30.07  5563.3   30.64  5671.6   31.09  5809.6    29.8  5829.6   31.73
  5957.4   32.58  6000.2   32.58  6379.6   38.09  6639.6   48.07  6882.9   54.14
#Mann= 12 ,-1 , 0
  3306.2     .07       0    3436     .05       0  3875.9     .07       0
  4094.3     .05       0  4099.8     .07       0  4503.2     .12       0
  4774.8      .1       0  5173.7     .07       0  5563.3    .035       0
  5671.6     .05       0  5957.4     .07       0  6000.2     .05       0
Bank Sta=4094.3,4099.8
XS Rating Curve= 0 ,0
Exp/Cntr=0.3,0.1

Chan Stop Cuts=-1
Use User Specified Reach Order=0
Composite Channel Slope=5