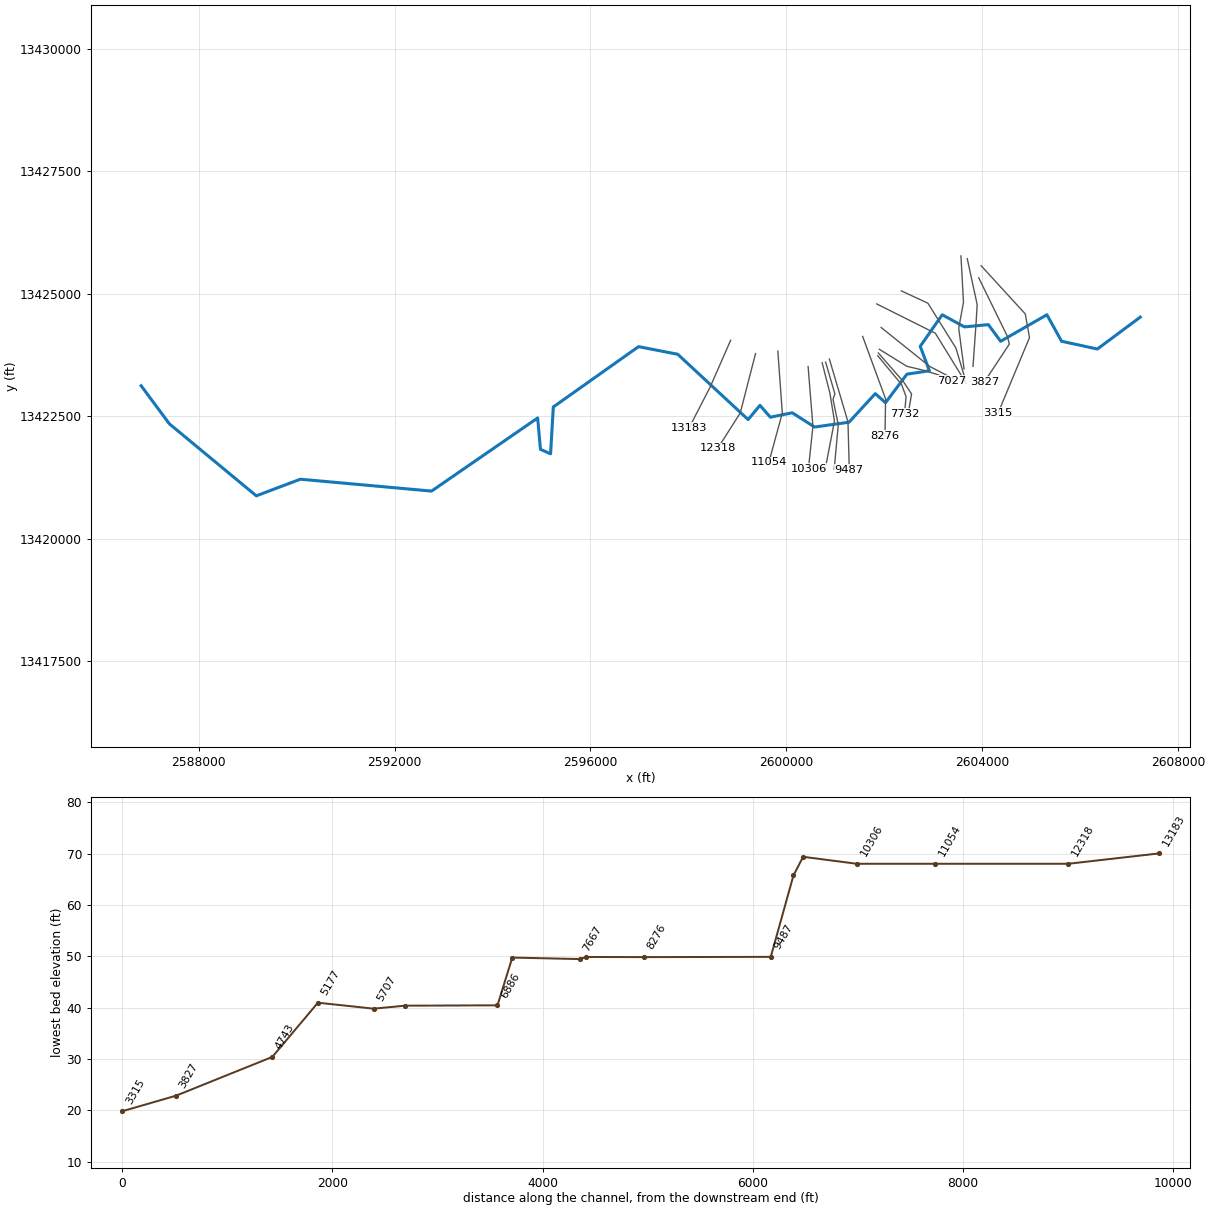
--- TRIB 2_6 TO GUADALUPE RIVER.prj (project) ---

Proj Title=TRIB 2_6 TO GUADALUPE RIVER Base Level Engineering
Current Plan=p01
Default Exp/Contr=0.3,0.1
English Units
Geom File=g01
Flow File=f01
Plan File=p01
Y Axis Title=Elevation
X Axis Title(PF)=Main Channel Distance
X Axis Title(XS)=Station
BEGIN DESCRIPTION:
TRIB 2_6 TO GUADALUPE RIVER
END DESCRIPTION:
DSS Export Rating Curves= 0
DSS Export Rating Curve Sorted= 0
DSS Export Volume Flow Curves= 0
DXF OffsetX= 0
DXF OffsetY= 0
DXF ScaleX= 1
DXF ScaleY= 10

--- TRIB 2_6 TO GUADALUPE RIVER.p01 (plan) ---

Plan Title=Multiple Run
Short Identifier=Multiple
Geom File=g01
Flow File=f01
Subcritical Flow
K Sum by GR= 0
Std Step Tol= 0.01
Critical Tol= 0.01
Num of Std Step Trials= 20
Max Error Tol= 0.3
Flow Tol Ratio= 0.001
Split Flow NTrial= 30
Split Flow Tol= 0.02
Split Flow Ratio= 0.02
Log Output Level= 0
Friction Slope Method= 1
Unsteady Friction Slope Method= 2
Unsteady Bridges Friction Slope Method= 1
Parabolic Critical Depth
Global Vel Dist=  1 , 1 , 1
Global Log Level= 0
CheckData=True
Encroach Param= -1, 0, 0, 0
BEGIN DESCRIPTION:
Multiple Run
END DESCRIPTION:

--- TRIB 2_6 TO GUADALUPE RIVER.f01 (steady flow) ---

Flow Title=Multiple
Number of Profiles=7
Profile Names=10-year,25-year,50-year,1pct_min,100-year,1pct_plu,500-year
River Rch & RM= TRIB 2_6 TO GUAD,Reach-1,13183
    1119    1761    2324    1477    2947    5880    4685
River Rch & RM= TRIB 2_6 TO GUAD,Reach-1,7027
    1764    2863    3857    2501    4991    9958    8265
Boundary for River Rch & Prof#=TRIB 2_6 TO GUAD,Reach-1,1
Up Type=0
Dn Type=3
Dn Slope=0.005
Boundary for River Rch & Prof#=TRIB 2_6 TO GUAD,Reach-1,2
Up Type=0
Dn Type=3
Dn Slope=0.005
Boundary for River Rch & Prof#=TRIB 2_6 TO GUAD,Reach-1,3
Up Type=0
Dn Type=3
Dn Slope=0.005
Boundary for River Rch & Prof#=TRIB 2_6 TO GUAD,Reach-1,4
Up Type=0
Dn Type=3
Dn Slope=0.005
Boundary for River Rch & Prof#=TRIB 2_6 TO GUAD,Reach-1,5
Up Type=0
Dn Type=3
Dn Slope=0.005
Boundary for River Rch & Prof#=TRIB 2_6 TO GUAD,Reach-1,6
Up Type=0
Dn Type=3
Dn Slope=0.005
Boundary for River Rch & Prof#=TRIB 2_6 TO GUAD,Reach-1,7
Up Type=0
Dn Type=3
Dn Slope=0.005

--- TRIB 2_6 TO GUADALUPE RIVER.g01 (geometry) ---

Geom Title=Existing Conditions
Program Version=4.10

River Reach=TRIB 2_6 TO GUAD,Reach-1
Reach XY= 30
        2586825.       13423125.      2587401.67     13422347.52
      2589176.65     13420878.11        2590075.     13421217.44
      2592754.97     13420975.07      2594921.68     13422467.42
      2594978.13     13421826.61      2595185.02     13421736.22
      2595241.23     13422692.04      2596981.05     13423922.89
      2597781.19     13423767.17      2599218.61     13422434.17
      2599459.78     13422724.77      2599671.57     13422482.79
      2600119.16     13422572.95      2600575.08      13422282.3
      2601277.71      13422380.4      2601814.98     13422964.06
      2602023.34     13422778.08      2602461.39     13423361.78
      2602919.83     13423430.41      2602732.59     13423928.33
      2603181.02     13424573.39      2603635.47     13424325.53
      2604123.37     13424371.87      2604374.78     13424031.99
      2605319.12     13424573.52      2605618.94     13424032.48
      2606349.91     13423874.38        2607225.       13424525.

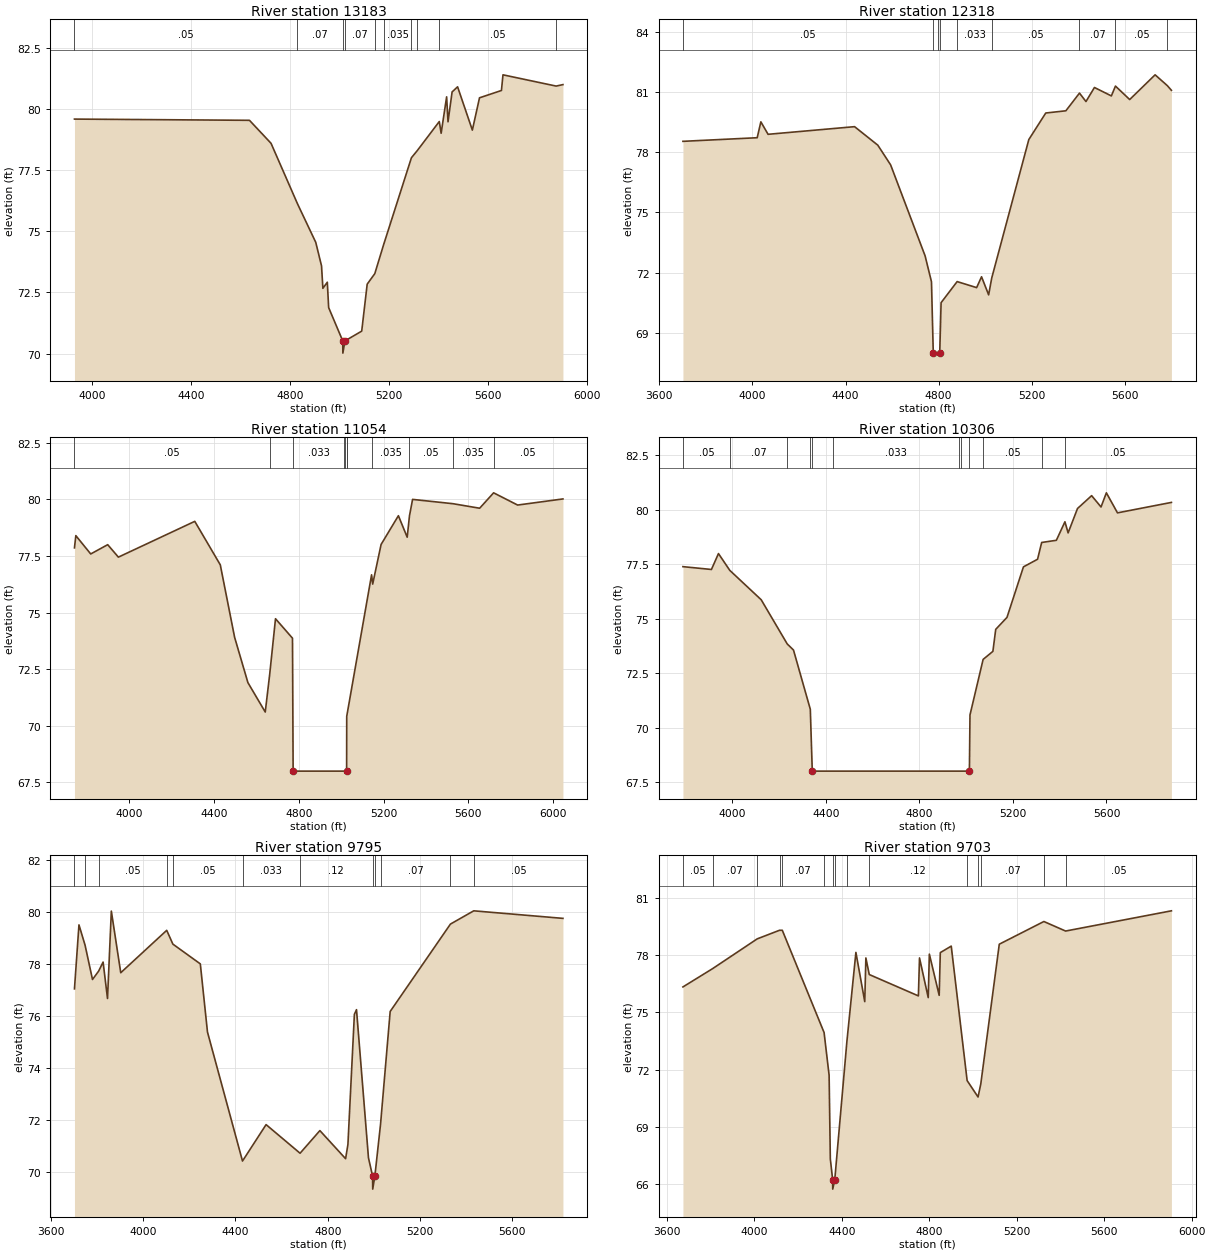
Type RM Length L Ch R = 1 ,13183   ,865,865,865
BEGIN DESCRIPTION:
Mapping XS 9e0baab3
END DESCRIPTION:
XS GIS Cut Line= 3
      2598861.89     13424052.81      2598445.21     13423102.27
      2598015.82     13422269.51
#Sta/Elev= 30
  3927.1   79.59  4634.6   79.54  4721.8    78.6  4828.6   76.13  4902.6   74.55
  4925.9   73.59  4931.4   72.67  4949.3   72.92  4954.8   71.88  5011.7   70.52
  5012.2   70.02  5020.7   70.52  5088.4   70.92  5110.5   72.84  5141.3   73.27
  5176.8   74.45  5289.4   78.01  5312.9    78.3    5402   79.49  5409.5   79.01
  5431.7    80.5  5437.3   79.48  5453.8    80.7    5476   80.91  5535.7   79.14
  5564.6   80.46  5653.3   80.76  5659.5    81.4  5874.4   80.94  5901.9      81
#Mann= 10 ,-1 , 0
  3927.1     .05       0  4828.6     .07       0  5011.7     .05       0
  5020.7     .07       0  5141.3     .05       0  5176.8    .035       0
  5289.4     .05       0  5312.9    .035       0    5402     .05       0
  5874.4     .07       0
Bank Sta=5011.7,5020.7
XS Rating Curve= 0 ,0
Exp/Cntr=0.3,0.1

Type RM Length L Ch R = 1 ,12318   ,1264,1264,1264
BEGIN DESCRIPTION:
Mapping XS 334c7226
END DESCRIPTION:
XS GIS Cut Line= 3
      2599369.68     13423779.32      2599057.19     13422568.42
      2598601.48      13421852.3
#Sta/Elev= 30
  3701.1   78.54  4020.3   78.72    4036   79.51    4067   78.89  4438.8   79.27
  4538.6   78.35  4593.7   77.37  4741.9   72.84  4769.3   71.55    4777      68
  4795.7      68  4804.8      68  4810.6   70.51  4879.6   71.56  4963.4   71.26
  4984.5    71.8    5015    70.9  5028.3   71.74  5187.7   78.63  5260.5   79.95
  5346.9   80.06  5405.4   80.94  5433.3   80.52  5469.7   81.22  5542.5    80.8
    5560   81.29  5621.2   80.62  5730.4   81.85  5783.2   81.31  5800.5   81.08
#Mann= 9 ,-1 , 0
  3701.1     .05       0    4777    .033       0  4795.7    .033       0
  4804.8     .12       0  4879.6    .033       0  5028.3     .05       0
  5405.4     .07       0    5560     .05       0  5783.2     .07       0
Bank Sta=4777,4804.8
XS Rating Curve= 0 ,0
Exp/Cntr=0.3,0.1

Type RM Length L Ch R = 1 ,11054   ,748,748,748
BEGIN DESCRIPTION:
Mapping XS db56e624
END DESCRIPTION:
XS GIS Cut Line= 3
      2599825.42     13423831.48      2599916.57     13422568.42
      2599643.12     13421565.78
#Sta/Elev= 30
  3740.7   77.86  3747.2    78.4  3817.4   77.59  3897.6      78    3948   77.45
  4308.6   79.03    4429   77.11  4496.6   73.91  4559.3   71.91  4641.2   70.61
  4662.4   72.29  4689.6   74.73  4769.8   73.87  4772.8      68  5012.8      68
  5016.2      68  5025.3      68  5025.8   70.42  5143.1   76.67  5148.3   76.26
    5188   78.01  5269.7   79.28  5311.2   78.33  5321.9   79.27  5336.6      80
    5527   79.81  5653.2   79.61  5719.1   80.29  5832.4   79.75  6046.3   80.02
#Mann= 11 ,-1 , 0
  3740.7     .05       0  4662.4     .12       0  4772.8    .033       0
  5012.8    .033       0  5016.2    .033       0  5025.3    .033       0
  5025.8     .05       0  5143.1    .035       0  5321.9     .05       0
    5527    .035       0  5719.1     .05       0
Bank Sta=4772.8,5025.3
XS Rating Curve= 0 ,0
Exp/Cntr=0.3,0.1

Type RM Length L Ch R = 1 ,10306   ,511,511,511
BEGIN DESCRIPTION:
Mapping XS 73dd0fdc
END DESCRIPTION:
XS GIS Cut Line= 3
      2600443.41     13423516.51      2600541.57     13422294.98
      2600450.42     13421435.57
#Sta/Elev= 30
  3788.1   77.39    3910   77.26  3940.1   77.99  3988.5   77.22  4122.9   75.87
  4234.3   73.84  4261.1   73.56    4333   70.84  4341.4      68  4431.8      68
  4968.6      68  4978.3      68  5013.6      68  5016.1   70.58  5072.3   73.13
  5114.1    73.5  5126.2   74.51  5174.4   75.06  5244.8   77.38  5305.2   77.73
  5322.8    78.5  5385.6    78.6  5422.3   79.45  5435.9   78.94  5476.1   80.06
  5536.5   80.65  5576.7   80.13  5599.6   80.78  5647.1   79.86  5877.8   80.34
#Mann= 12 ,-1 , 0
  3788.1     .05       0  3988.5     .07       0  4234.3     .05       0
    4333    .035       0  4341.4    .035       0  4431.8    .033       0
  4968.6    .033       0  4978.3    .033       0  5013.6    .033       0
  5072.3     .05       0  5322.8    .035       0  5422.3     .05       0
Bank Sta=4341.4,5013.6
XS Rating Curve= 0 ,0
Exp/Cntr=0.3,0.1

Type RM Length L Ch R = 1 ,9795    ,92,92,92
BEGIN DESCRIPTION:
Mapping XS 5a2c9d57
END DESCRIPTION:
XS GIS Cut Line= 4
       2600730.2     13423593.89      2600888.11     13422975.14
      2600981.56     13422404.77      2600810.91     13421519.32
#Sta/Elev= 30
  3701.8   77.06  3721.3   79.52  3747.8   78.74    3780   77.42  3806.5   77.74
    3826   78.09  3845.1   76.69  3861.7   80.05  3902.5   77.68  4101.9   79.31
  4128.6   78.78  4247.6   78.02  4278.6    75.4  4430.5   70.44  4532.8   71.84
  4680.2   70.74  4766.1   71.61  4877.6   70.53  4887.7   71.08  4915.7   76.08
  4924.9   76.26  4976.8   70.56  4994.7   69.86  4995.2   69.36  5004.5   69.86
  5029.2   71.86  5070.9   76.19  5332.2   79.55  5433.3   80.06  5820.1   79.77
#Mann= 12 ,-1 , 0
  3701.8     .05       0  3747.8     .07       0  3806.5     .05       0
  4101.9    .035       0  4128.6     .05       0  4430.5    .033       0
  4680.2     .12       0  4994.7     .05       0  5004.5     .12       0
  5029.2     .07       0  5332.2    .035       0  5433.3     .05       0
Bank Sta=4994.7,5004.5
XS Rating Curve= 0 ,0
Exp/Cntr=0.3,0.1

Type RM Length L Ch R = 1 ,9703    ,216,216,216
BEGIN DESCRIPTION:
Mapping XS cc3b1042
END DESCRIPTION:
XS GIS Cut Line= 5
      2600801.11     13423606.72      2600990.02     13422959.28
      2600951.82     13422848.17      2601059.46     13422330.81
      2600976.13     13421421.09
#Sta/Elev= 30
  3673.5   76.33  3809.3   77.29  4013.2   78.85  4115.1    79.3  4127.9    79.3
    4319   73.94    4342    71.7  4347.5   67.32  4358.1   66.23  4358.6   65.73
  4367.9   66.23  4423.4   73.48  4464.5   78.14    4505   75.56  4510.1   77.85
  4525.6   76.98  4750.3   75.86  4755.4   77.85  4795.3   75.77  4800.4   78.05
  4845.4   75.89  4850.5   78.13  4900.5   78.47  4973.2   71.42  5023.1   70.56
  5035.6   71.24  5120.2   78.57  5324.2   79.76  5423.5   79.26  5907.4   80.32
#Mann= 15 ,-1 , 0
  3673.5     .05       0  3809.3     .07       0  4013.2    .035       0
  4115.1     .05       0  4127.9     .07       0    4319     .05       0
  4358.1     .05       0  4367.9     .05       0  4423.4     .07       0
  4525.6     .12       0  4973.2      .1       0  5023.1    .035       0
  5035.6     .07       0  5324.2    .035       0  5423.5     .05       0
Bank Sta=4358.1,4367.9
XS Rating Curve= 0 ,0
Exp/Cntr=0.3,0.1

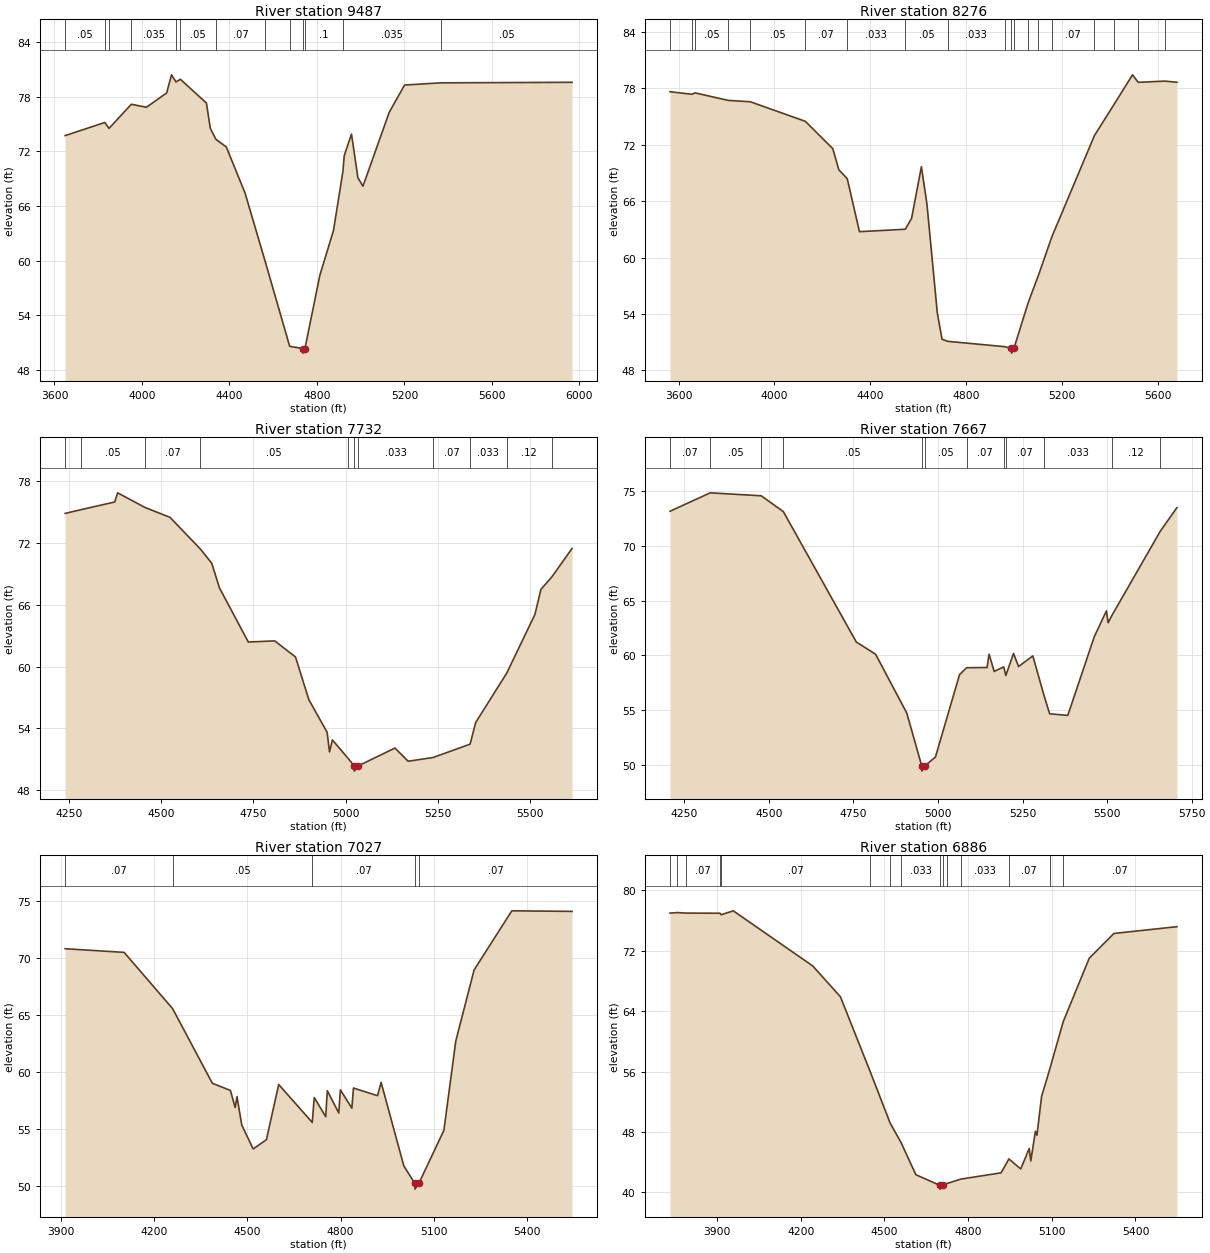
Type RM Length L Ch R = 1 ,9487    ,1211,1211,1211
BEGIN DESCRIPTION:
Mapping XS 806013af
END DESCRIPTION:
XS GIS Cut Line= 3
      2600877.17     13423671.25      2601257.71     13422386.13
      2601283.75     13421409.75
#Sta/Elev= 30
  3648.9   73.74  3830.1   75.18  3849.4   74.53  3951.5   77.18  4020.4   76.85
  4112.9   78.42  4135.2   80.41  4155.6   79.63  4175.8   79.92  4294.8   77.31
  4312.5   74.54  4338.1   73.33  4385.5    72.5  4471.5   67.42  4563.7    59.9
  4675.3   50.62  4735.2   50.37  4735.7   49.87    4745   50.37  4813.1    58.4
  4875.6   63.34  4918.4   69.77  4924.7   71.55  4957.9   73.91  4987.2   69.11
  5010.3   68.19  5130.4    76.3  5200.4   79.29    5367   79.53  5965.9   79.59
#Mann= 13 ,-1 , 0
  3648.9     .05       0  3830.1     .07       0  3849.4     .05       0
  3951.5    .035       0  4155.6     .07       0  4175.8     .05       0
  4338.1     .07       0  4563.7     .12       0  4675.3      .1       0
  4735.2    .035       0    4745      .1       0  4918.4    .035       0
    5367     .05       0
Bank Sta=4735.2,4745
XS Rating Curve= 0 ,0
Exp/Cntr=0.3,0.1

Type RM Length L Ch R = 1 ,8276    ,544,544,544
BEGIN DESCRIPTION:
Mapping XS 99dcaa01
END DESCRIPTION:
XS GIS Cut Line= 3
      2601557.19     13424130.94      2602025.94     13422854.88
      2602012.93     13422099.83
#Sta/Elev= 30
  3564.4   77.65  3655.1   77.38    3669   77.53  3806.5   76.73  3899.5   76.58
  4128.9    74.5  4243.4   71.59  4268.6   69.34  4303.6    68.4  4354.7   62.75
  4545.8   63.01  4572.1   64.17    4613   69.67  4636.1    65.7  4679.3   54.12
  4699.1    51.3  4724.2   51.07    4960   50.51  4988.6   50.32  4989.1   49.82
  4998.9   50.32  5058.7    55.2    5101   58.09  5157.5   62.22  5334.8   72.98
    5415   76.23  5493.8   79.45  5517.6   78.65  5627.8   78.78    5679   78.66
#Mann= 19 ,-1 , 0
  3564.4     .05       0  3655.1     .07       0    3669     .05       0
  3806.5    .035       0  3899.5     .05       0  4128.9     .07       0
  4303.6    .033       0  4545.8     .05       0  4724.2    .033       0
    4960      .1       0  4988.6     .05       0  4998.9      .1       0
  5058.7     .12       0    5101      .1       0  5157.5     .07       0
  5334.8     .12       0    5415     .07       0  5517.6    .035       0
  5627.8     .05       0
Bank Sta=4988.6,4998.9
XS Rating Curve= 0 ,0
Exp/Cntr=0.3,0.1

Type RM Length L Ch R = 1 ,7732    ,65,65,65
BEGIN DESCRIPTION:
Mapping XS de298416
END DESCRIPTION:
XS GIS Cut Line= 4
      2601865.92     13423735.49      2602352.04     13423149.54
      2602443.18     13422904.32       2602412.8      13422554.9
#Sta/Elev= 30
    4240   74.86  4282.4   75.22  4374.4   75.97  4382.2   76.86    4457   75.43
  4524.2   74.48  4606.2   71.42  4637.4   70.02  4658.3   67.63  4736.4   62.38
    4808   62.49  4864.3   60.93  4900.5   56.78    4950   53.62  4956.5   51.71
  4964.3   52.88  5006.8   51.09  5023.3   50.35  5023.8   49.85  5033.7   50.35
  5133.9   52.09  5169.6   50.81    5237   51.17  5337.5   52.47  5352.6   54.57
  5436.7   59.36  5513.2   65.06  5529.4   67.49  5558.8   68.69  5613.7   71.46
#Mann= 11 ,-1 , 0
    4240     .07       0  4282.4     .05       0    4457     .07       0
  4606.2     .05       0  5006.8    .033       0  5023.3     .05       0
  5033.7    .033       0    5237     .07       0  5337.5    .033       0
  5436.7     .12       0  5558.8     .07       0
Bank Sta=5023.3,5033.7
XS Rating Curve= 0 ,0
Exp/Cntr=0.3,0.1

Type RM Length L Ch R = 1 ,7667    ,640,640,640
BEGIN DESCRIPTION:
Mapping XS e572e9d2
END DESCRIPTION:
XS GIS Cut Line= 4
      2601876.76     13423794.09       2602391.1     13423205.96
      2602556.03      13422956.4      2602484.42     13422544.12
#Sta/Elev= 30
  4207.6   73.14  4326.5   74.82  4477.2   74.55  4542.6   73.11  4758.5   61.21
  4815.5    60.1  4907.6   54.74  4951.7   49.94  4952.2   49.44  4962.1   49.94
  4992.5   50.73  5063.7   58.24  5084.5   58.87    5145   58.89    5151   60.11
  5166.1   58.53  5194.3   58.95  5200.6   58.16  5223.2   60.17  5238.3   58.98
  5280.4   59.95  5312.9    56.4  5330.1   54.67  5383.8   54.52    5462   61.69
  5498.1   64.06  5503.1   62.97  5514.1   63.63  5657.5   71.33  5706.5   73.47
#Mann= 12 ,-1 , 0
  4207.6     .07       0  4326.5     .05       0  4477.2     .07       0
  4542.6     .05       0  4951.7     .05       0  4962.1     .05       0
  5084.5     .07       0  5194.3    .033       0  5200.6     .07       0
  5312.9    .033       0  5514.1     .12       0  5657.5     .07       0
Bank Sta=4951.7,4962.1
XS Rating Curve= 0 ,0
Exp/Cntr=0.3,0.1

Type RM Length L Ch R = 1 ,7027    ,141,141,141
BEGIN DESCRIPTION:
Mapping XS 844e1217
END DESCRIPTION:
XS GIS Cut Line= 5
      2601897.39     13423868.94      2602459.89     13423521.72
      2602786.28     13423443.59      2603084.89     13423353.32
      2603378.29     13423221.38
#Sta/Elev= 30
  3914.1   70.85  4103.8   70.53  4259.7   65.59  4387.6   59.03  4445.6    58.4
    4461    56.9  4466.8   57.86  4482.2   55.36  4518.9   53.26  4561.4   54.07
    4601   58.92  4708.9   55.59  4715.3   57.78  4752.2   56.09  4757.3   58.38
  4794.2   56.42  4799.4   58.45  4836.3   56.84  4841.4   58.61  4918.9   57.94
  4930.3   59.11  5003.4   51.77  5038.8   50.23  5039.3   49.73  5051.7   50.23
  5132.3    54.9  5170.6   62.75  5229.5   68.99  5350.8   74.18  5544.4   74.13
#Mann= 5 ,-1 , 0
  3914.1     .07       0  4259.7     .05       0  4708.9     .07       0
  5038.8     .05       0  5051.7     .07       0
Bank Sta=5038.8,5051.7
XS Rating Curve= 0 ,0
Exp/Cntr=0.3,0.1

Type RM Length L Ch R = 1 ,6886    ,879,879,879
BEGIN DESCRIPTION:
Mapping XS 66dcd6b7
END DESCRIPTION:
XS GIS Cut Line= 3
      2601934.81      13424313.2      2602925.13     13423519.87
       2603411.3      13423265.7
#Sta/Elev= 30
  3731.1   76.99  3757.8   77.06  3787.3   76.99  3910.3   76.97  3914.3   76.77
  3957.9   77.29  4242.8   69.99    4342   65.91    4447   56.16  4520.3   49.18
  4559.8   46.57  4612.5   42.34  4698.7   40.93  4699.2   40.43  4711.6   40.93
  4723.1   41.16  4774.1   41.76  4918.2   42.59  4946.1   44.43  4988.6    43.1
    5019   45.81  5024.7   44.17  5041.1    48.1  5046.8   47.56  5063.2    52.7
  5091.7    56.2  5140.9   62.61  5234.2   71.01  5322.5   74.29  5548.6   75.19
#Mann= 15 ,-1 , 0
  3731.1     .07       0  3757.8     .05       0  3787.3     .07       0
  3910.3    .035       0  3914.3     .07       0    4447     .05       0
  4520.3     .07       0  4559.8    .033       0  4698.7     .05       0
  4711.6    .033       0  4723.1     .12       0  4774.1    .033       0
  4946.1     .07       0  5091.7     .12       0  5140.9     .07       0
Bank Sta=4698.7,4711.6
XS Rating Curve= 0 ,0
Exp/Cntr=0.3,0.1

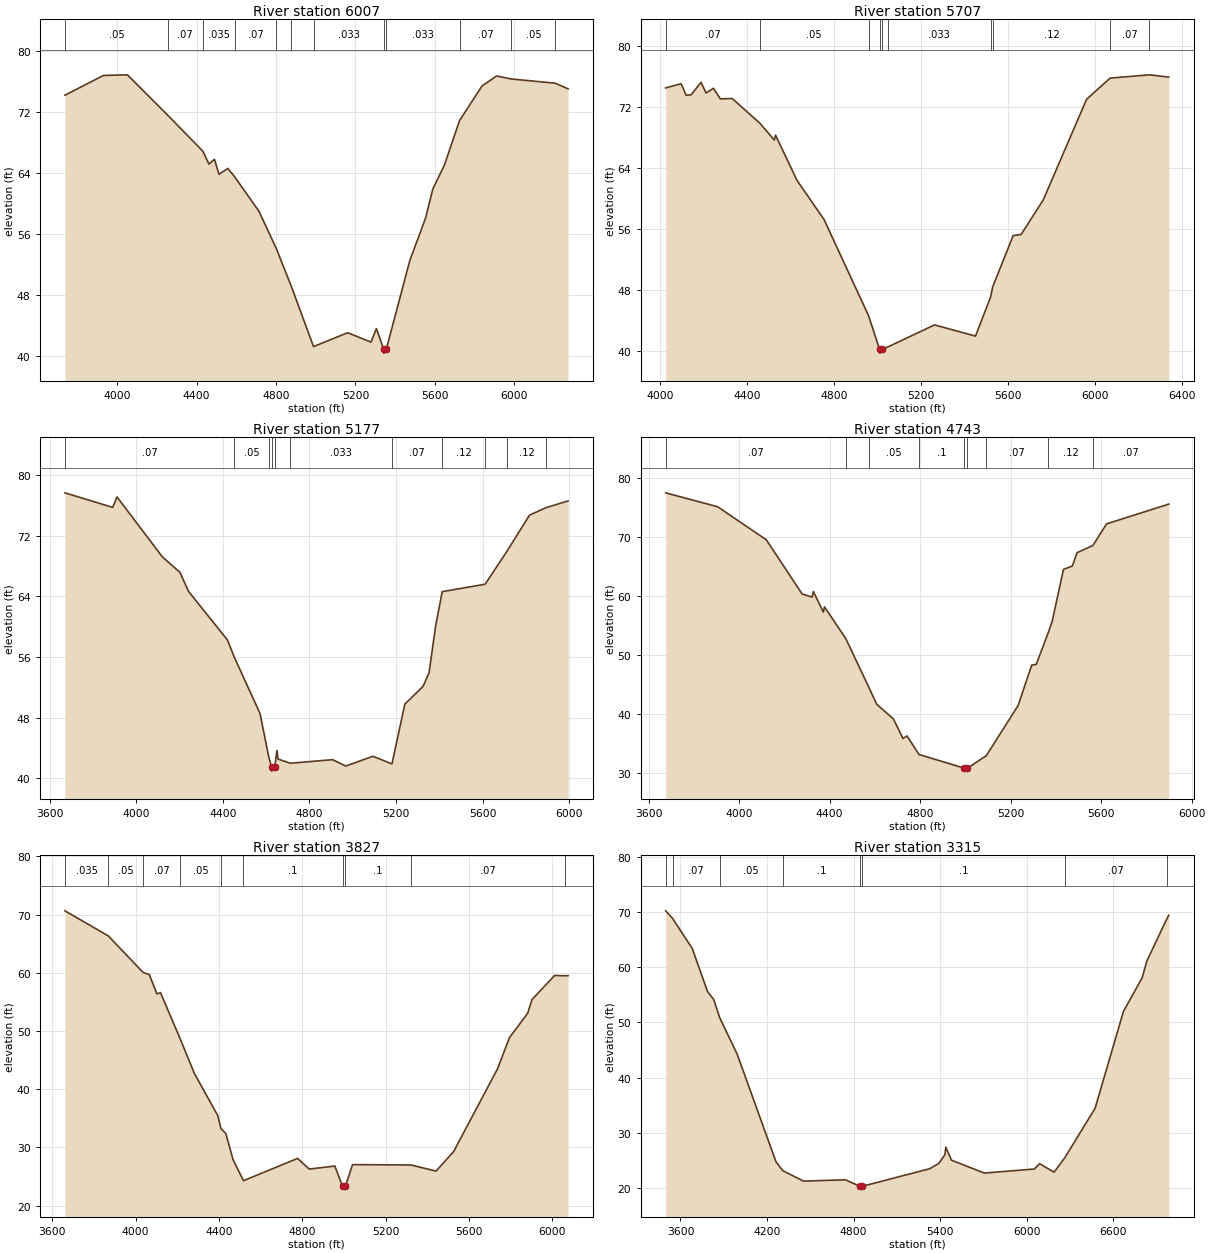
Type RM Length L Ch R = 1 ,6007    ,300,300,300
BEGIN DESCRIPTION:
Mapping XS 6448661d
END DESCRIPTION:
XS GIS Cut Line= 3
      2601843.67     13424794.98      2603041.57     13424196.02
      2603666.56     13423180.42
#Sta/Elev= 30
  3737.9   74.25  3931.5   76.85  4052.4   76.93  4254.9   71.63  4431.7    66.9
  4462.5    65.2  4490.5   65.83  4512.9   63.86  4557.6   64.63  4591.5   63.54
  4714.1   59.01  4800.5   54.17  4877.4   49.12  4988.8   41.22  5160.6   43.04
    5278   41.81  5305.3   43.58    5342   40.86  5342.5   40.36    5355   40.86
  5473.3   52.52  5552.6   58.09  5589.3   61.94  5647.2   65.05  5723.7   70.92
  5836.6   75.46    5910   76.78    5985   76.38  6205.3   75.83  6269.7   75.09
#Mann= 12 ,-1 , 0
  3737.9     .05       0  4254.9     .07       0  4431.7    .035       0
  4591.5     .07       0  4800.5     .05       0  4877.4     .07       0
  4988.8    .033       0    5342    .033       0    5355    .033       0
  5723.7     .07       0    5985     .05       0  6205.3     .07       0
Bank Sta=5342,5355
XS Rating Curve= 0 ,0
Exp/Cntr=0.3,0.1

Type RM Length L Ch R = 1 ,5707    ,530,530,530
BEGIN DESCRIPTION:
Mapping XS d2392824
END DESCRIPTION:
XS GIS Cut Line= 4
      2602346.48     13425060.48       2602889.6     13424808.93
      2603461.31     13423894.19      2603644.24      13423282.5
#Sta/Elev= 30
  4024.4   74.46  4095.7   75.01  4118.6    73.5  4141.5   73.56  4187.3    75.2
  4210.1    73.8  4244.2   74.41  4276.2   73.02  4330.3   73.08    4458   69.84
  4524.2   67.65  4530.2   68.28  4628.6   62.38  4753.6   57.24  4958.2   44.68
  5008.8   40.28  5009.3   39.78  5021.9   40.28  5047.1   40.59  5261.8   43.47
  5450.5   42.01    5520   47.11    5530   48.48  5623.9   55.15  5660.4   55.29
  5762.5   59.82  5961.7   72.97  6070.1   75.74  6251.3   76.17  6340.1   75.87
#Mann= 10 ,-1 , 0
  4024.4     .07       0    4458     .05       0  4958.2     .07       0
  5008.8     .05       0  5021.9     .07       0  5047.1    .033       0
    5520     .07       0    5530     .12       0  6070.1     .07       0
  6251.3     .05       0
Bank Sta=5008.8,5021.9
XS Rating Curve= 0 ,0
Exp/Cntr=0.3,0.1

Type RM Length L Ch R = 1 ,5177    ,434,434,434
BEGIN DESCRIPTION:
Mapping XS aefd4a6b
END DESCRIPTION:
XS GIS Cut Line= 4
      2603564.22     13425775.17      2603615.67     13424826.08
      2603518.48      13424300.1       2603627.3     13423468.45
#Sta/Elev= 30
  3671.1   77.63  3891.6   75.71  3911.6   77.09  4121.9   69.16    4202   67.16
  4242.1   64.63  4422.4   58.21  4452.8      56  4572.6   48.52  4611.9   42.89
  4625.9   41.44  4626.4   40.94  4639.7   41.44  4650.5   43.66  4655.5   42.53
  4712.5   41.98  4907.4   42.45  4968.4   41.61  5094.3    42.9  5181.6   41.89
  5241.2   49.77  5325.2   52.11  5353.2   53.91  5383.5   60.09  5413.9    64.6
  5612.2   65.58  5711.3   69.85  5817.2   74.69  5894.1   75.68  5995.2   76.56
#Mann= 11 ,-1 , 0
  3671.1     .07       0  4452.8     .05       0  4611.9    .035       0
  4625.9    .033       0  4639.7    .035       0  4712.5    .033       0
  5181.6     .07       0  5413.9     .12       0  5612.2     .07       0
  5711.3     .12       0  5894.1     .07       0
Bank Sta=4625.9,4639.7
XS Rating Curve= 0 ,0
Exp/Cntr=0.3,0.1

Type RM Length L Ch R = 1 ,4743    ,916,916,916
BEGIN DESCRIPTION:
Mapping XS 437e3f58
END DESCRIPTION:
XS GIS Cut Line= 4
      2603692.61     13425719.48      2603894.96     13424782.69
       2603874.9      13424430.4      2603809.94     13423520.87
#Sta/Elev= 30
  3675.8   77.53  3905.5   75.17  4120.3   69.58    4279   60.38  4323.2   59.86
  4328.3   60.82  4372.4   57.33  4377.5   58.21    4472   52.82  4572.3   44.68
  4608.5    41.7    4682   39.23  4724.3   35.91  4742.1   36.34  4795.6   33.19
  4995.6   30.88  4996.1   30.38  5009.4   30.88  5092.8   33.01  5233.1   41.49
  5293.2   48.34  5313.3   48.47  5365.4   53.75  5383.5   55.73  5433.6   64.55
  5472.8   65.14  5493.7   67.39  5563.6   68.61  5624.1   72.27  5898.9   75.62
#Mann= 9 ,-1 , 0
  3675.8     .07       0    4472    .035       0  4572.3     .05       0
  4795.6      .1       0  4995.6     .05       0  5009.4      .1       0
  5092.8     .07       0  5365.4     .12       0  5563.6     .07       0
Bank Sta=4995.6,5009.4
XS Rating Curve= 0 ,0
Exp/Cntr=0.3,0.1

Type RM Length L Ch R = 1 ,3827    ,512,512,512
BEGIN DESCRIPTION:
Mapping XS 197661cf
END DESCRIPTION:
XS GIS Cut Line= 4
      2603926.99     13425328.83      2604512.92     13424130.92
      2604551.99     13423974.67      2604044.17     13423206.43
#Sta/Elev= 30
  3660.5   70.65  3868.3   66.35    4036   60.06  4065.5    59.7  4102.1   56.36
  4119.1   56.61  4214.1   48.63  4282.2   42.69  4394.8   35.43  4409.3   33.24
  4432.9   32.38  4467.9   27.86  4517.6   24.28  4777.5   28.11  4833.6   26.27
  4956.1    26.8  4993.2   23.33  4993.7   22.83    5007   23.33  5041.4   27.04
  5321.6   26.98  5442.4   25.93  5526.8   29.29  5737.5   43.51  5794.7   48.86
    5882   53.03  5903.1   55.41  6011.4   59.54  6059.7   59.49    6076   59.51
#Mann= 10 ,-1 , 0
  3660.5    .035       0  3868.3     .05       0    4036     .07       0
  4214.1     .05       0  4409.3     .07       0  4517.6      .1       0
  4993.2     .05       0    5007      .1       0  5321.6     .07       0
  6059.7     .05       0
Bank Sta=4993.2,5007
XS Rating Curve= 0 ,0
Exp/Cntr=0.3,0.1

Type RM Length L Ch R = 1 ,3315    ,0,0,0
BEGIN DESCRIPTION:
TRIB 2-6 TO GUADALUPE RIVER 1.0
END DESCRIPTION:
XS GIS Cut Line= 4
      2603975.02     13425574.98      2604877.24     13424590.74
      2604963.37     13424107.08        2604325.     13422575.01
#Sta/Elev= 30
  3497.3   70.19  3545.1   68.82  3681.3   63.38  3787.4   55.57  3829.9   54.14
  3871.4   50.86  3992.7   44.24  4261.6   24.76  4308.2   23.15  4452.7   21.25
  4743.2   21.49    4844    20.3  4844.5    19.8  4857.8    20.3  5327.6    23.5
    5391   24.48  5432.7   26.08  5438.1   27.41  5477.7   25.04  5705.2   22.71
  6051.8   23.44  6088.1   24.41  6188.9   22.87  6262.1   25.45  6472.7   34.43
  6669.3   51.97  6799.3   58.08  6831.8   61.11  6970.9   68.79  6983.5   69.39
#Mann= 8 ,-1 , 0
  3497.3    .035       0  3545.1     .07       0  3871.4     .05       0
  4308.2      .1       0    4844     .05       0  4857.8      .1       0
  6262.1     .07       0  6970.9    .035       0
Bank Sta=4844,4857.8
XS Rating Curve= 0 ,0
Exp/Cntr=0.3,0.1

Chan Stop Cuts=-1
Use User Specified Reach Order=0
Composite Channel Slope=5