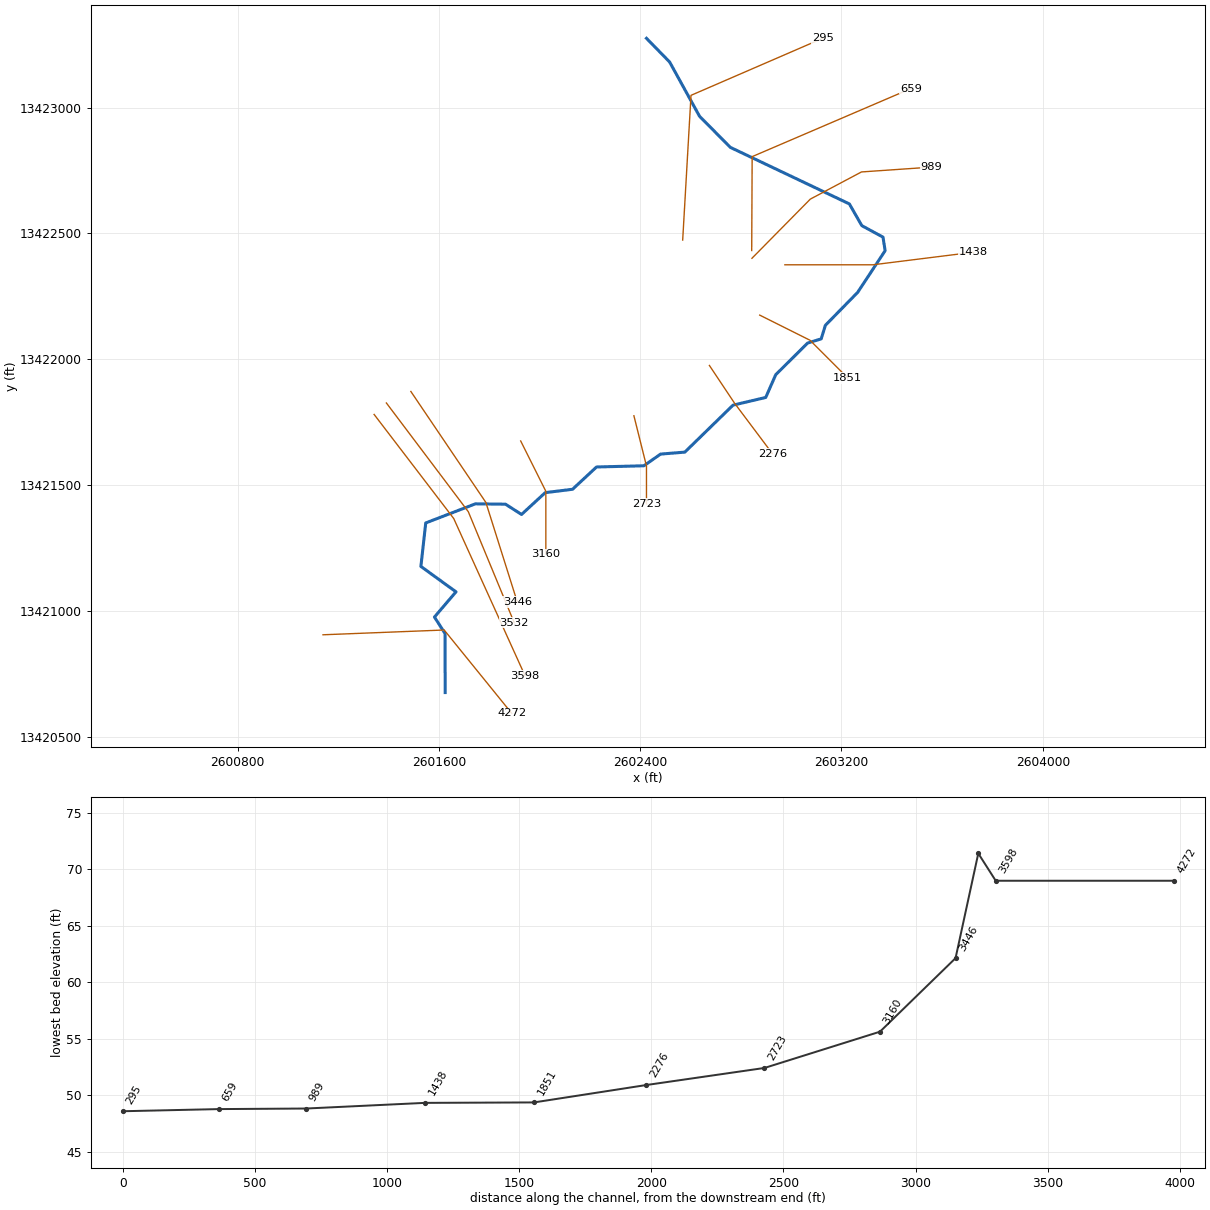
--- TRIB 2_6-1 TO GUADALUPE RIVER.prj (project) ---

Proj Title=TRIB 2_6-1 TO GUADALUPE RIVER Base Level Engineering
Current Plan=p01
Default Exp/Contr=0.3,0.1
English Units
Geom File=g01
Flow File=f01
Plan File=p01
Y Axis Title=Elevation
X Axis Title(PF)=Main Channel Distance
X Axis Title(XS)=Station
BEGIN DESCRIPTION:
TRIB 2_6-1 TO GUADALUPE RIVER
END DESCRIPTION:
DSS Export Rating Curves= 0
DSS Export Rating Curve Sorted= 0
DSS Export Volume Flow Curves= 0
DXF OffsetX= 0
DXF OffsetY= 0
DXF ScaleX= 1
DXF ScaleY= 10

--- TRIB 2_6-1 TO GUADALUPE RIVER.p01 (plan) ---

Plan Title=Multiple Run
Short Identifier=Multiple
Geom File=g01
Flow File=f01
Subcritical Flow
K Sum by GR= 0
Std Step Tol= 0.01
Critical Tol= 0.01
Num of Std Step Trials= 20
Max Error Tol= 0.3
Flow Tol Ratio= 0.001
Split Flow NTrial= 30
Split Flow Tol= 0.02
Split Flow Ratio= 0.02
Log Output Level= 0
Friction Slope Method= 1
Unsteady Friction Slope Method= 2
Unsteady Bridges Friction Slope Method= 1
Parabolic Critical Depth
Global Vel Dist=  1 , 1 , 1
Global Log Level= 0
CheckData=True
Encroach Param= -1, 0, 0, 0
BEGIN DESCRIPTION:
Multiple Run
END DESCRIPTION:

--- TRIB 2_6-1 TO GUADALUPE RIVER.f01 (steady flow) ---

Flow Title=Multiple
Number of Profiles=7
Profile Names=10-year,25-year,50-year,1pct_min,100-year,1pct_plu,500-year
River Rch & RM= TRIB 2_6-1 TO GU,Reach-1,4272
     443     663     845     520    1038    2070    1546
River Rch & RM= TRIB 2_6-1 TO GU,Reach-1,3598
     637     985    1285     810    1615    3223    2522
Boundary for River Rch & Prof#=TRIB 2_6-1 TO GU,Reach-1,1
Up Type=0
Dn Type=3
Dn Slope=0.005
Boundary for River Rch & Prof#=TRIB 2_6-1 TO GU,Reach-1,2
Up Type=0
Dn Type=3
Dn Slope=0.005
Boundary for River Rch & Prof#=TRIB 2_6-1 TO GU,Reach-1,3
Up Type=0
Dn Type=3
Dn Slope=0.005
Boundary for River Rch & Prof#=TRIB 2_6-1 TO GU,Reach-1,4
Up Type=0
Dn Type=3
Dn Slope=0.005
Boundary for River Rch & Prof#=TRIB 2_6-1 TO GU,Reach-1,5
Up Type=0
Dn Type=3
Dn Slope=0.005
Boundary for River Rch & Prof#=TRIB 2_6-1 TO GU,Reach-1,6
Up Type=0
Dn Type=3
Dn Slope=0.005
Boundary for River Rch & Prof#=TRIB 2_6-1 TO GU,Reach-1,7
Up Type=0
Dn Type=3
Dn Slope=0.005

--- TRIB 2_6-1 TO GUADALUPE RIVER.g01 (geometry) ---

Geom Title=Existing Conditions
Program Version=4.10

River Reach=TRIB 2_6-1 TO GU,Reach-1
Reach XY= 30
        2601625.       13420675.      2601624.34     13420909.84
      2601582.34      13420975.1      2601667.99     13421075.21
      2601528.44     13421176.25      2601547.65     13421349.02
      2601745.04     13421424.95      2601864.56     13421423.62
      2601928.41     13421382.81      2602022.57     13421469.45
      2602131.16     13421482.88      2602226.47     13421571.45
       2602414.5     13421576.22      2602480.98     13421622.64
      2602577.43     13421630.52      2602768.83     13421817.14
      2602898.89     13421847.72      2602938.64      13421938.2
      2603065.58     13422064.11      2603119.38     13422080.62
      2603135.89     13422134.42      2603264.22     13422265.32
      2603373.43     13422431.09      2603364.91     13422484.97
      2603280.67     13422530.66      2603231.32     13422616.93
      2602758.32     13422841.64      2602635.78     13422965.32
      2602516.89     13423181.07        2602425.       13423275.

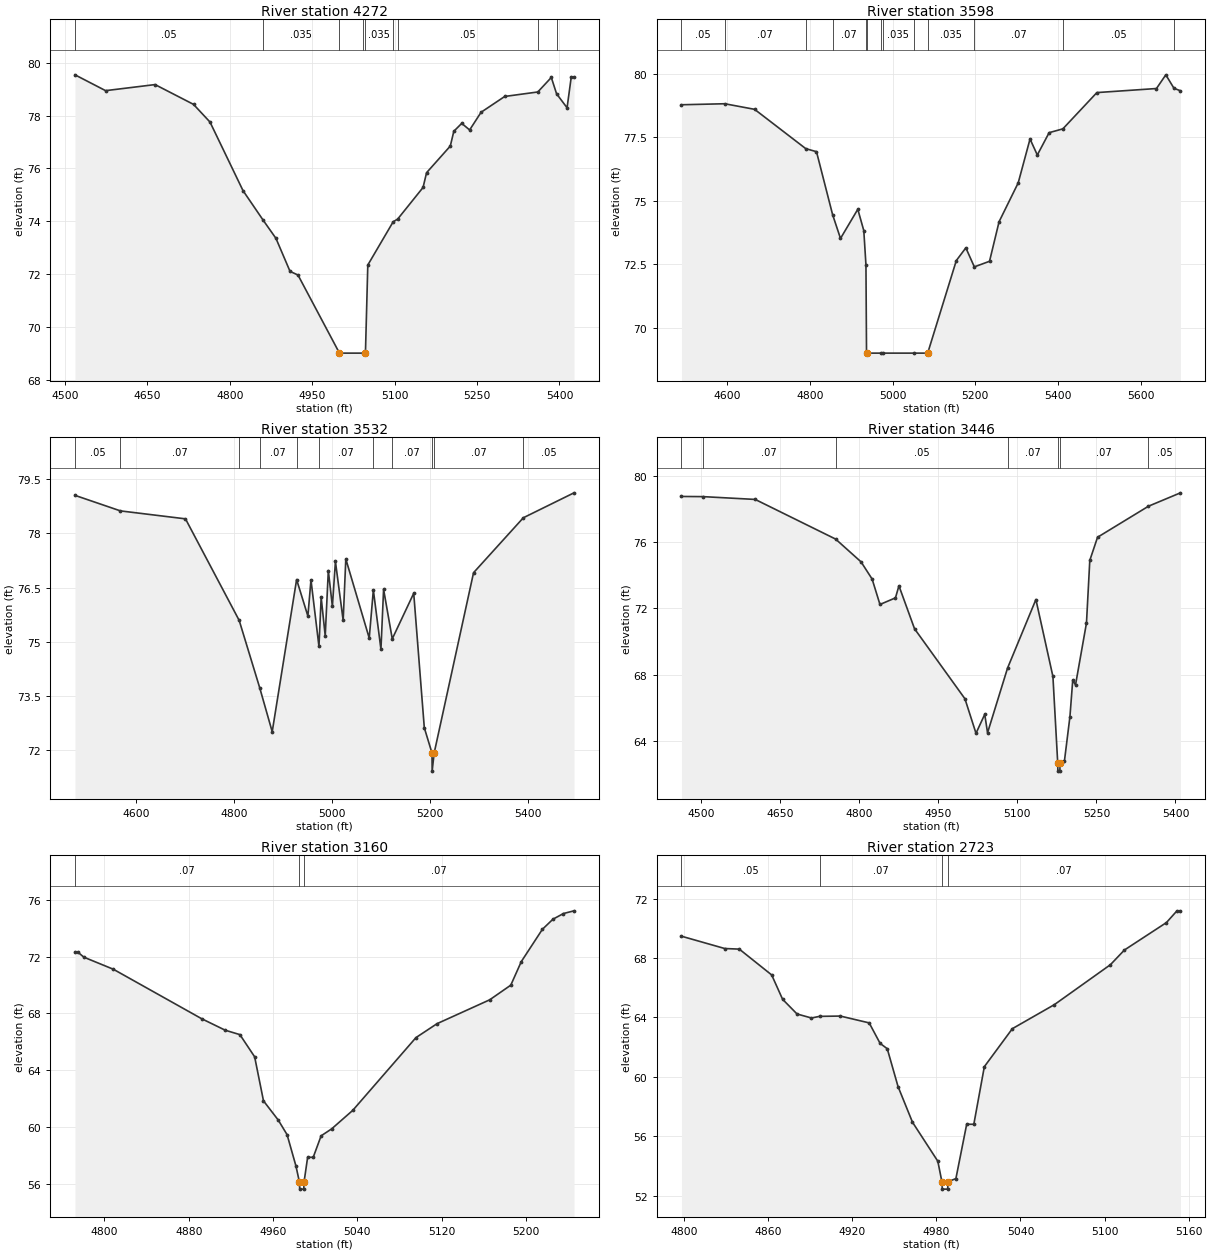
Type RM Length L Ch R = 1 ,4272    ,674,674,674
BEGIN DESCRIPTION:
TRIB 2-6-1 TO GUADALUPE RIVER 9.0
END DESCRIPTION:
XS GIS Cut Line= 3
      2601139.35     13420904.59      2601620.98     13420923.54
      2601889.56     13420592.23
#Sta/Elev= 30
    4518   79.55  4573.7   78.95  4663.8   79.18  4733.8   78.43  4763.8   77.76
  4823.9   75.16  4860.9   74.03  4883.9   73.35  4909.5    72.1    4924   71.96
  4999.5      69  5042.5      69  5046.8      69  5051.1   72.34  5097.3   73.98
  5105.4   74.08  5151.7   75.28  5158.1   75.84  5201.3   76.85  5207.7   77.41
  5222.1   77.71  5236.5   77.46  5257.3   78.13  5300.4   78.73  5360.6    78.9
  5385.2   79.45  5394.8   78.83  5413.9    78.3  5421.5   79.47  5426.5   79.47
#Mann= 9 ,-1 , 0
    4518     .05       0  4860.9    .035       0  4999.5    .035       0
  5042.5    .035       0  5046.8    .035       0  5097.3     .07       0
  5105.4     .05       0  5360.6    .035       0  5394.8     .05       0
Bank Sta=4999.5,5046.8
XS Rating Curve= 0 ,0
Exp/Cntr=0.3,0.1

Type RM Length L Ch R = 1 ,3598    ,66,66,66
BEGIN DESCRIPTION:
Mapping XS e57e481f
END DESCRIPTION:
XS GIS Cut Line= 3
      2601342.55     13421780.25      2601658.96     13421366.49
      2601941.92     13420742.75
#Sta/Elev= 30
    4490   78.79  4594.7   78.83  4666.7   78.61  4790.4   77.06  4816.3   76.94
  4855.2   74.46  4874.3   73.52  4916.1   74.67  4930.6   73.83  4935.8   72.48
  4937.2      69    4972      69  4976.4      69  5051.8      69    5085      69
  5154.2   72.65  5177.2   73.15  5197.7    72.4  5234.4   72.62  5257.5   74.18
  5303.7   75.71  5332.3   77.44  5349.9   76.81  5378.4   77.69  5411.6   77.84
  5493.8   79.27  5637.8   79.43  5660.4   79.97  5680.1   79.44  5695.8   79.34
#Mann= 13 ,-1 , 0
    4490     .05       0  4594.7     .07       0  4790.4     .05       0
  4855.2     .07       0  4935.8    .035       0  4937.2    .035       0
    4972    .035       0  4976.4    .035       0  5051.8    .035       0
    5085    .035       0  5197.7     .07       0  5411.6     .05       0
  5680.1    .035       0
Bank Sta=4937.2,5085
XS Rating Curve= 0 ,0
Exp/Cntr=0.3,0.1

Type RM Length L Ch R = 1 ,3532    ,86,86,86
BEGIN DESCRIPTION:
Mapping XS f9ce4928
END DESCRIPTION:
XS GIS Cut Line= 3
       2601391.2     13421825.93      2601716.77     13421393.87
      2601899.31     13420952.73
#Sta/Elev= 30
  4475.2   79.05    4568   78.62  4700.7    78.4  4810.3   75.59  4852.1   73.73
  4877.7   72.51  4927.5   76.72  4950.5   75.71  4956.8   76.71  4973.1   74.87
  4977.6   76.23  4985.9   75.16  4992.2   76.97  5000.5   75.98  5006.7   77.22
  5022.5   75.59  5027.9   77.29  5075.7    75.1  5084.1   76.43  5099.6   74.79
    5105   76.45  5122.7   75.08  5166.5   76.34  5188.1   72.62  5203.8   71.92
  5204.1   71.42  5208.2   71.92  5288.6   76.91  5390.2   78.43  5493.6   79.12
#Mann= 11 ,-1 , 0
  4475.2     .05       0    4568     .07       0  4810.3     .05       0
  4852.1     .07       0  4927.5     .05       0  4973.1     .07       0
  5084.1    .035       0  5122.7     .07       0  5203.8     .05       0
  5208.2     .07       0  5390.2     .05       0
Bank Sta=5203.8,5208.2
XS Rating Curve= 0 ,0
Exp/Cntr=0.3,0.1

Type RM Length L Ch R = 1 ,3446    ,286,286,286
BEGIN DESCRIPTION:
Mapping XS b9963090
END DESCRIPTION:
XS GIS Cut Line= 3
      2601488.56     13421871.57      2601786.75     13421430.38
      2601911.48     13421034.89
#Sta/Elev= 30
  4462.3   78.78    4503   78.77  4602.3    78.6  4754.9    76.2  4803.2   74.82
  4824.2   73.78  4839.1   72.24  4868.5   72.64  4875.1   73.37  4904.7   70.77
  5000.4   66.53  5021.4   64.44    5038   65.59  5043.3   64.47  5081.3   68.39
  5135.1   72.54  5167.4   67.88  5176.5   62.65  5176.8   62.15  5180.6   62.15
  5180.9   62.65  5189.2   62.75  5199.7   65.45    5205   67.65  5210.3   67.37
  5231.1   71.12  5237.4   74.91  5252.1   76.31  5348.8   78.19  5409.5      79
#Mann= 7 ,-1 , 0
  4462.3     .05       0    4503     .07       0  4754.9     .05       0
  5081.3     .07       0  5176.5     .05       0  5180.9     .07       0
  5348.8     .05       0
Bank Sta=5176.5,5180.9
XS Rating Curve= 0 ,0
Exp/Cntr=0.3,0.1

Type RM Length L Ch R = 1 ,3160    ,437,437,437
BEGIN DESCRIPTION:
TRIB 2-6-1 TO GUADALUPE RIVER 7.0
END DESCRIPTION:
XS GIS Cut Line= 3
      2601924.99     13421675.02        2602025.       13421475.
        2602025.     13421225.03
#Sta/Elev= 30
    4772   72.31  4774.8   72.31  4780.4   71.96  4808.4   71.11  4892.2   67.63
  4914.6   66.82  4928.5   66.51  4942.5   64.95  4950.9   61.85  4964.9    60.5
  4973.3   59.47  4981.7   57.27    4985   56.14  4985.3   55.64  4989.1   55.64
  4989.4   56.14  4992.8   57.88  4998.1   57.88  5005.6   59.39  5015.6   59.88
  5035.6   61.18  5095.6    66.3  5115.6   67.28  5165.6   68.96  5185.6   69.99
  5195.6   71.65  5215.6   73.92  5225.6   74.63  5235.6   75.03  5245.6   75.22
#Mann= 3 ,-1 , 0
    4772     .07       0    4985     .05       0  4989.4     .07       0
Bank Sta=4985,4989.4
XS Rating Curve= 0 ,0
Exp/Cntr=0.3,0.1

Type RM Length L Ch R = 1 ,2723    ,447,447,447
BEGIN DESCRIPTION:
TRIB 2-6-1 TO GUADALUPE RIVER 6.0
END DESCRIPTION:
XS GIS Cut Line= 3
      2602374.99     13421775.02        2602425.       13421575.
        2602425.     13421424.98
#Sta/Elev= 30
    4798   69.47  4828.9   68.64  4839.3    68.6  4862.4   66.86  4870.2   65.22
  4880.5   64.23  4890.8   63.96  4896.6   64.07  4911.4   64.09    4932   63.63
  4939.8   62.25  4944.9   61.89  4952.6   59.34  4962.9   56.94    4981   54.31
  4983.9   52.93  4984.2   52.43    4988   52.43  4988.3   52.93  4993.9   53.14
  5001.6    56.8  5006.7    56.8  5014.2   60.68  5034.2   63.24  5064.2   64.86
  5104.2   67.55  5114.2   68.54  5144.2   70.39  5151.7   71.18  5154.2   71.18
#Mann= 4 ,-1 , 0
    4798     .05       0  4896.6     .07       0  4983.9     .05       0
  4988.3     .07       0
Bank Sta=4983.9,4988.3
XS Rating Curve= 0 ,0
Exp/Cntr=0.3,0.1

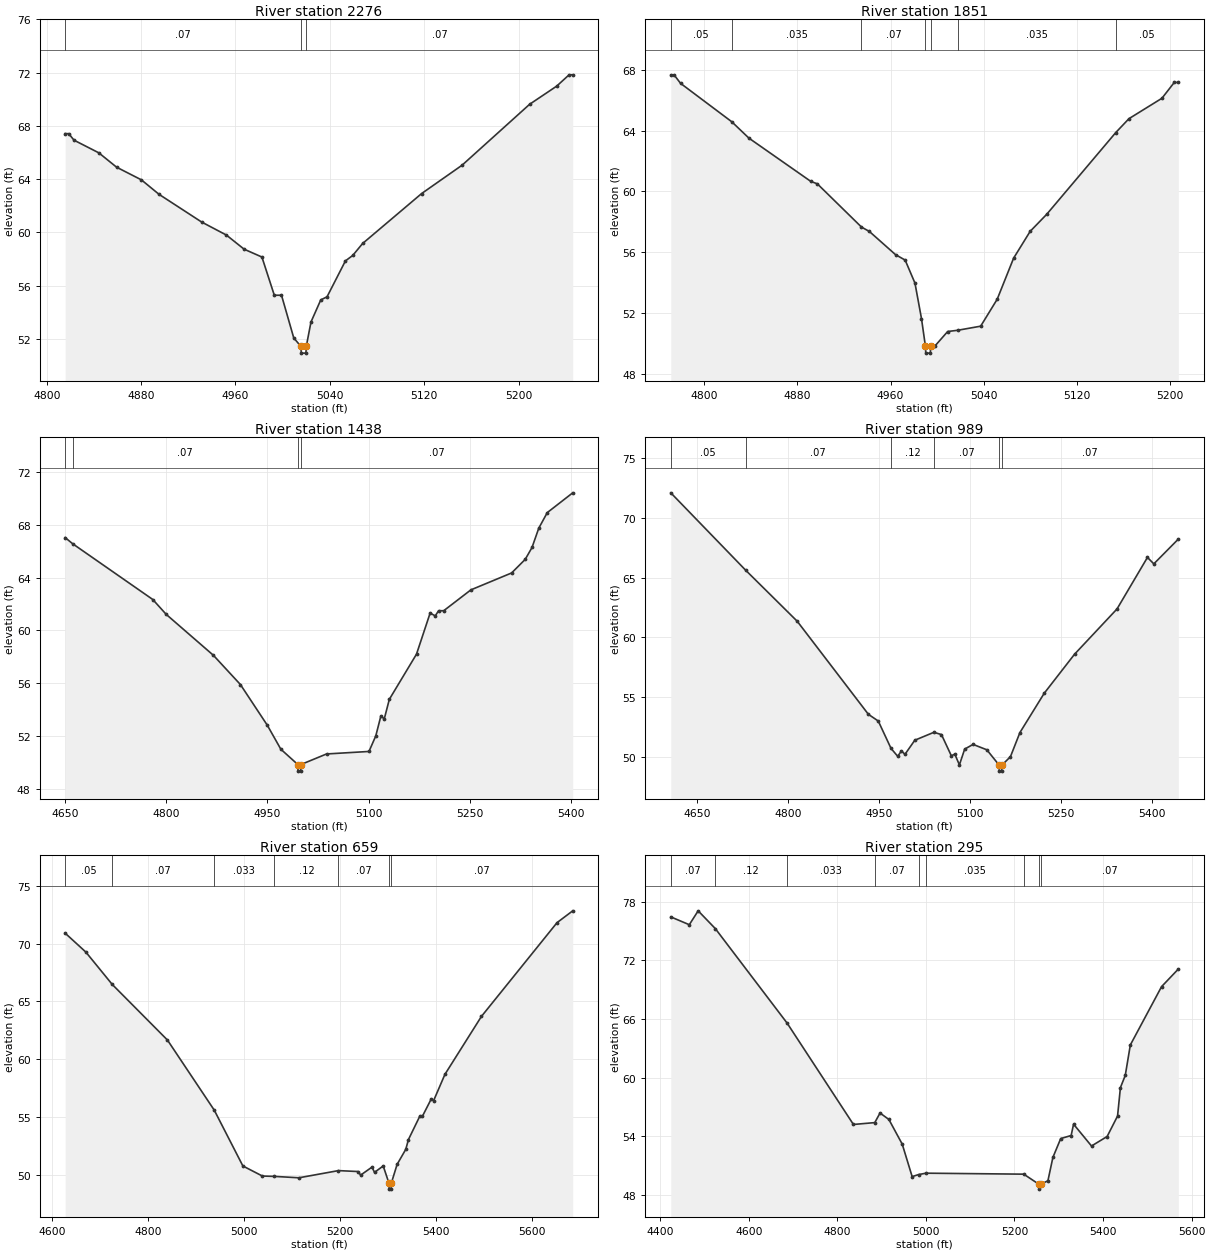
Type RM Length L Ch R = 1 ,2276    ,425,425,425
BEGIN DESCRIPTION:
TRIB 2-6-1 TO GUADALUPE RIVER 5.0
END DESCRIPTION:
XS GIS Cut Line= 3
        2602675.       13421975.        2602775.       13421825.
      2602925.01     13421624.99
#Sta/Elev= 30
  4815.6   67.41  4818.6   67.41  4823.1   66.92  4844.1   65.97  4859.2   64.89
  4880.2   63.94  4895.2   62.85  4931.3   60.77  4952.3   59.79  4967.3   58.73
  4982.4   58.14  4992.9   55.27    4999   55.27  5009.4   52.06  5015.5   51.42
  5015.8   50.92  5019.7   50.92    5020   51.42    5024   53.26  5032.3   54.92
  5037.6   55.15  5053.2   57.85  5059.4   58.26  5067.8   59.16  5117.8   62.91
  5152.1   65.04  5209.4   69.62  5232.3   70.98  5242.8   71.83  5245.9   71.83
#Mann= 3 ,-1 , 0
  4815.6     .07       0  5015.5     .05       0    5020     .07       0
Bank Sta=5015.5,5020
XS Rating Curve= 0 ,0
Exp/Cntr=0.3,0.1

Type RM Length L Ch R = 1 ,1851    ,413,413,413
BEGIN DESCRIPTION:
TRIB 2-6-1 TO GUADALUPE RIVER 4.0
END DESCRIPTION:
XS GIS Cut Line= 3
      2602875.01       13422175.        2603075.       13422075.
      2603224.98     13421925.02
#Sta/Elev= 30
  4771.3   67.66  4774.1   67.66  4779.7    67.1  4823.6   64.58  4838.4    63.5
  4891.5   60.66  4897.1    60.5    4935   57.66  4941.8   57.37  4964.2   55.85
  4972.5   55.49  4980.9   53.98  4986.5   51.65  4989.8   49.88  4990.2   49.38
  4994.1   49.38  4994.4   49.88  4998.4   49.88    5009    50.8  5017.5   50.88
  5037.3   51.15  5051.5   52.92  5065.6   55.62  5079.8   57.38  5093.9   58.49
  5153.3   63.87  5164.6   64.78  5192.9   66.12  5203.5   67.16    5207   67.16
#Mann= 7 ,-1 , 0
  4771.3     .05       0  4823.6    .035       0    4935     .07       0
  4989.8     .05       0  4994.4     .07       0  5017.5    .035       0
  5153.3     .05       0
Bank Sta=4989.8,4994.4
XS Rating Curve= 0 ,0
Exp/Cntr=0.3,0.1

Type RM Length L Ch R = 1 ,1438    ,449,449,449
BEGIN DESCRIPTION:
TRIB 2-6-1 TO GUADALUPE RIVER 3.0
END DESCRIPTION:
XS GIS Cut Line= 3
      2602974.98       13422375.        2603325.       13422375.
      2603724.97       13422425.
#Sta/Elev= 30
  4649.9   67.03  4661.1   66.56  4779.9   62.34  4799.9   61.21  4869.9   58.11
  4909.9    55.9  4949.9   52.81  4969.9      51  4995.1   49.84  4995.5   49.34
  4999.4   49.34  4999.7   49.84  5037.7   50.64  5100.7   50.83  5110.8   52.01
  5118.3   53.51  5123.4    53.3  5130.9   54.78  5171.2    58.2  5191.4   61.31
    5199    61.1    5204   61.49  5211.6   61.49  5251.9   63.07  5312.3   64.35
  5332.5   65.38  5342.6   66.28  5352.6   67.74  5365.2   68.92    5403   70.42
#Mann= 4 ,-1 , 0
  4649.9     .05       0  4661.1     .07       0  4995.1     .05       0
  4999.7     .07       0
Bank Sta=4995.1,4999.7
XS Rating Curve= 0 ,0
Exp/Cntr=0.3,0.1

Type RM Length L Ch R = 1 ,989     ,330,330,330
BEGIN DESCRIPTION:
Mapping XS ba6c6239
END DESCRIPTION:
XS GIS Cut Line= 4
      2602844.04      13422400.8      2603076.04     13422635.98
      2603279.42     13422744.02      2603555.91     13422763.09
#Sta/Elev= 30
  4606.2   72.07  4729.6   65.62  4814.9   61.35  4932.4   53.58  4948.7   53.02
  4969.7   50.74  4980.7   50.08    4987   50.53  4992.7   50.24    5009   51.42
  5040.5   52.08    5053   51.89  5069.3   50.12    5075   50.26  5082.6   49.36
  5091.3   50.68  5105.2   51.07  5127.9   50.62  5148.2   49.34  5148.5   48.84
  5152.5   48.84  5152.8   49.34  5166.9   50.05  5182.5   52.06  5222.6   55.34
  5272.7    58.6  5342.8   62.38    5393   66.68  5403.5   66.14    5444   68.21
#Mann= 6 ,-1 , 0
  4606.2     .05       0  4729.6     .07       0  4969.7     .12       0
  5040.5     .07       0  5148.2     .05       0  5152.8     .07       0
Bank Sta=5148.2,5152.8
XS Rating Curve= 0 ,0
Exp/Cntr=0.3,0.1

Type RM Length L Ch R = 1 ,659     ,364,364,364
BEGIN DESCRIPTION:
TRIB 2-6-1 TO GUADALUPE RIVER 2.0
END DESCRIPTION:
XS GIS Cut Line= 3
      2602843.17     13422431.72      2602844.93     13422804.82
      2603475.04     13423075.02
#Sta/Elev= 30
  4626.9    70.9  4670.2   69.26  4725.1   66.47  4840.2   61.67  4937.9   55.61
  4997.6   50.79  5038.3   49.92  5063.2   49.89  5114.5   49.77    5197   50.39
  5237.8   50.31  5243.2      50  5266.8   50.69  5272.2   50.24  5290.3   50.79
  5302.4   49.29  5302.7   48.79  5306.7   48.79  5307.1   49.29  5319.3   50.93
  5337.4   52.23  5342.9   53.07  5366.5   55.08  5371.9   55.07    5390   56.54
  5395.5   56.44  5419.1   58.71  5495.2   63.71  5652.9   71.81  5685.6   72.83
#Mann= 7 ,-1 , 0
  4626.9     .05       0  4725.1     .07       0  4937.9    .033       0
  5063.2     .12       0    5197     .07       0  5302.4    .033       0
  5307.1     .07       0
Bank Sta=5302.4,5307.1
XS Rating Curve= 0 ,0
Exp/Cntr=0.3,0.1

Type RM Length L Ch R = 1 ,295     ,0,0,0
BEGIN DESCRIPTION:
TRIB 2-6-1 TO GUADALUPE RIVER 1.0
END DESCRIPTION:
XS GIS Cut Line= 3
      2602568.86      13422473.3      2602601.94     13423048.44
      2603124.98     13423274.99
#Sta/Elev= 30
  4423.9   76.43  4465.7   75.63  4485.7   77.05  4524.5   75.23  4686.6   65.57
  4836.3   55.21  4884.5    55.4  4896.4   56.38  4916.4   55.72  4946.5    53.2
  4968.9   49.88  4983.5   50.09  5000.3   50.23  5220.9   50.13  5255.1    49.1
  5255.5    48.6  5259.8    49.1  5275.5   49.46  5286.7   51.84  5304.4   53.77
  5327.9   54.08  5333.4   55.24  5373.9   53.01  5409.2   53.98  5432.7   56.07
  5439.2   58.98  5450.1   60.22  5461.6   63.34  5532.1    69.3    5570    71.1
#Mann= 9 ,-1 , 0
  4423.9     .07       0  4524.5     .12       0  4686.6    .033       0
  4884.5     .07       0  4983.5    .033       0  5000.3    .035       0
  5220.9     .07       0  5255.1    .033       0  5259.8     .07       0
Bank Sta=5255.1,5259.8
XS Rating Curve= 0 ,0
Exp/Cntr=0.3,0.1

Chan Stop Cuts=-1
Use User Specified Reach Order=0
Composite Channel Slope=5