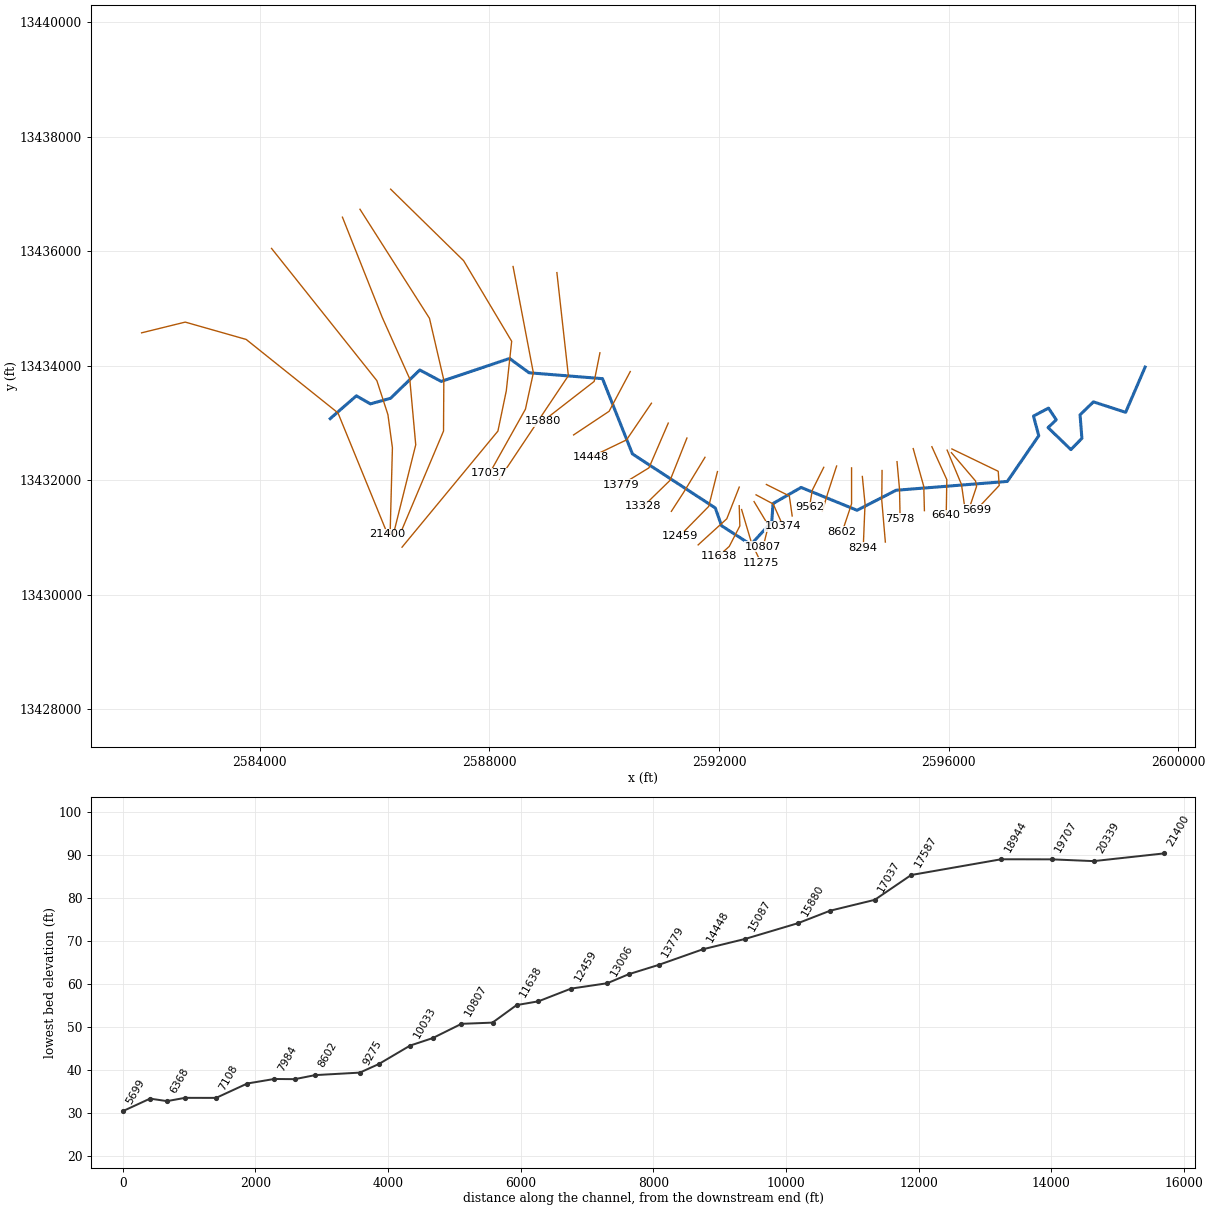
--- TRIB 2_8 TO GUADALUPE RIVER.prj (project) ---

Proj Title=TRIB 2_8 TO GUADALUPE RIVER Base Level Engineering
Current Plan=p01
Default Exp/Contr=0.3,0.1
English Units
Geom File=g01
Flow File=f01
Plan File=p01
Y Axis Title=Elevation
X Axis Title(PF)=Main Channel Distance
X Axis Title(XS)=Station
BEGIN DESCRIPTION:
TRIB 2_8 TO GUADALUPE RIVER
END DESCRIPTION:
DSS Export Rating Curves= 0
DSS Export Rating Curve Sorted= 0
DSS Export Volume Flow Curves= 0
DXF OffsetX= 0
DXF OffsetY= 0
DXF ScaleX= 1
DXF ScaleY= 10

--- TRIB 2_8 TO GUADALUPE RIVER.p01 (plan) ---

Plan Title=Multiple Run
Short Identifier=Multiple
Geom File=g01
Flow File=f01
Subcritical Flow
K Sum by GR= 0
Std Step Tol= 0.01
Critical Tol= 0.01
Num of Std Step Trials= 20
Max Error Tol= 0.3
Flow Tol Ratio= 0.001
Split Flow NTrial= 30
Split Flow Tol= 0.02
Split Flow Ratio= 0.02
Log Output Level= 0
Friction Slope Method= 1
Unsteady Friction Slope Method= 2
Unsteady Bridges Friction Slope Method= 1
Parabolic Critical Depth
Global Vel Dist=  1 , 1 , 1
Global Log Level= 0
CheckData=True
Encroach Param= -1, 0, 0, 0
BEGIN DESCRIPTION:
Multiple Run
END DESCRIPTION:

--- TRIB 2_8 TO GUADALUPE RIVER.f01 (steady flow) ---

Flow Title=Multiple
Number of Profiles=7
Profile Names=10-year,25-year,50-year,1pct_min,100-year,1pct_plu,500-year
River Rch & RM= TRIB 2_8 TO GUAD,Reach-1,21400
     377     553     696     423     843    1683    1224
River Rch & RM= TRIB 2_8 TO GUAD,Reach-1,20339
     463     691     879     540    1077    2149    1596
River Rch & RM= TRIB 2_8 TO GUAD,Reach-1,17037
     612     933    1205     751    1499    2990    2290
River Rch & RM= TRIB 2_8 TO GUAD,Reach-1,15087
     709    1094    1425     895    1786    3564    2774
River Rch & RM= TRIB 2_8 TO GUAD,Reach-1,14448
     910    1429    1884    1198    2390    4769    3803
River Rch & RM= TRIB 2_8 TO GUAD,Reach-1,11275
    1183    1893    2527    1625    3242    6469    5282
River Rch & RM= TRIB 2_8 TO GUAD,Reach-1,9562
    1407    2271    3049    1973    3936    7853    6485
Boundary for River Rch & Prof#=TRIB 2_8 TO GUAD,Reach-1,1
Up Type=0
Dn Type=3
Dn Slope=0.005
Boundary for River Rch & Prof#=TRIB 2_8 TO GUAD,Reach-1,2
Up Type=0
Dn Type=3
Dn Slope=0.005
Boundary for River Rch & Prof#=TRIB 2_8 TO GUAD,Reach-1,3
Up Type=0
Dn Type=3
Dn Slope=0.005
Boundary for River Rch & Prof#=TRIB 2_8 TO GUAD,Reach-1,4
Up Type=0
Dn Type=3
Dn Slope=0.005
Boundary for River Rch & Prof#=TRIB 2_8 TO GUAD,Reach-1,5
Up Type=0
Dn Type=3
Dn Slope=0.005
Boundary for River Rch & Prof#=TRIB 2_8 TO GUAD,Reach-1,6
Up Type=0
Dn Type=3
Dn Slope=0.005
Boundary for River Rch & Prof#=TRIB 2_8 TO GUAD,Reach-1,7
Up Type=0
Dn Type=3
Dn Slope=0.005

--- TRIB 2_8 TO GUADALUPE RIVER.g01 (geometry) ---

Geom Title=Existing Conditions
Program Version=4.10

River Reach=TRIB 2_8 TO GUAD,Reach-1
Reach XY= 30
        2585225.       13433075.      2585681.04     13433473.39
       2585924.9     13433332.33       2586277.3     13433430.83
      2586785.62      13433924.4      2587159.53     13433724.99
        2588350.     13434125.41      2588690.82     13433875.66
      2589969.29     13433773.11      2590491.43     13432458.23
      2591935.05     13431514.95      2592044.43     13431204.36
      2592555.06     13430874.73      2592919.19     13431272.71
      2592941.24     13431592.23      2593431.11      13431873.2
      2594404.87     13431474.61      2595085.29     13431824.03
      2597023.75     13431978.45      2597571.53      13432776.5
      2597479.65     13433119.74      2597741.67     13433258.81
      2597875.71     13433054.86      2597733.76     13432918.16
      2598131.67     13432533.95      2598323.04     13432730.89
       2598291.3      13433141.7       2598524.9     13433367.68
      2599085.07     13433185.03        2599425.       13433975.

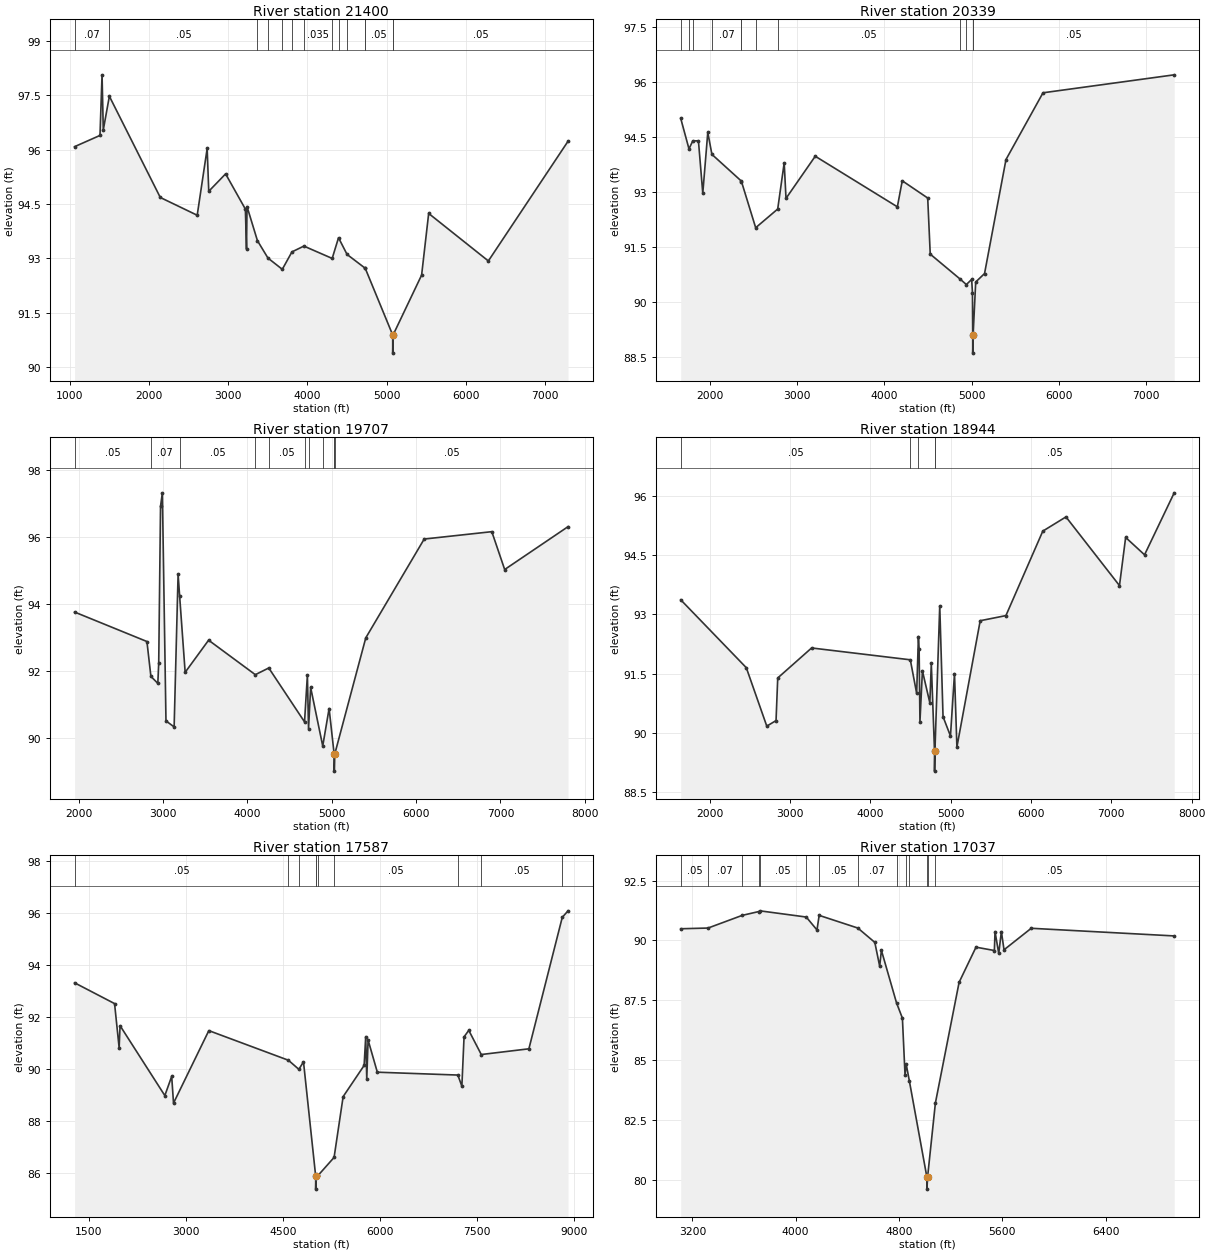
Type RM Length L Ch R = 1 ,21400   ,1061,1061,1061
BEGIN DESCRIPTION:
TRIB 2-8 TO GUADALUPE RIVER 30.0
END DESCRIPTION:
XS GIS Cut Line= 5
       2581938.4     13434573.22      2582698.47     13434760.75
      2583760.42     13434458.23      2585359.95     13433175.19
      2586225.83     13431053.58
#Sta/Elev= 30
  1062.4   96.08  1383.1   96.39  1409.1   98.06  1424.6   96.54  1501.3   97.47
  2144.2   94.68  2610.2   94.19  2735.9   96.03    2756   94.85  2968.6   95.33
  3218.2   94.36  3232.6   93.26    3239   94.43  3370.4   93.49  3503.3   93.01
  3684.3    92.7  3806.1   93.18  3956.8   93.34  4314.2      93  4394.1   93.57
  4501.9   93.11  4730.6   92.73    4731   92.73    5078   90.89  5078.4   90.39
  5082.7   90.89    5443   92.54  5532.1   94.24  6285.5   92.93  7291.5   96.23
#Mann= 14 ,-1 , 0
  1062.4     .07       0  1501.3     .05       0  3370.4    .035       0
  3503.3     .05       0  3684.3    .035       0  3806.1     .05       0
  3956.8    .035       0  4314.2     .05       0  4394.1    .035       0
  4501.9     .05       0  4730.6    .035       0    4731     .05       0
    5078     .05       0  5082.7     .05       0
Bank Sta=5078,5082.7
XS Rating Curve= 0 ,0
Exp/Cntr=0.3,0.1

Type RM Length L Ch R = 1 ,20339   ,632,632,632
BEGIN DESCRIPTION:
Mapping XS ca2b2ca5
END DESCRIPTION:
XS GIS Cut Line= 5
      2584202.83     13436047.44      2586038.13     13433738.11
      2586230.84     13433144.36      2586308.96     13432566.24
      2586269.22     13431073.09
#Sta/Elev= 30
  1668.6      95    1763   94.17  1806.8   94.39  1871.3   94.39    1921   92.96
  1978.3   94.62  2025.7   94.02  2363.7   93.29    2364   93.28  2526.8   92.02
  2779.1   92.53  2853.3   93.79  2874.1   92.82    3209   93.97  4149.3   92.59
  4205.4    93.3  4496.9   92.83  4525.8    91.3  4867.9   90.62  4939.4   90.47
  5000.2   90.61  5009.3   90.25  5012.2    89.1  5012.5    88.6    5017    89.1
  5046.5   90.54  5147.7   90.77  5393.4   93.88  5817.2    95.7  7319.7   96.19
#Mann= 12 ,-1 , 0
  1668.6     .05       0    1763     .07       0  1806.8     .05       0
  2025.7     .07       0  2363.7     .05       0    2364     .07       0
  2526.8      .1       0  2779.1     .05       0  4867.9      .1       0
  4939.4     .05       0  5012.2     .05       0    5017     .05       0
Bank Sta=5012.2,5017
XS Rating Curve= 0 ,0
Exp/Cntr=0.3,0.1

Type RM Length L Ch R = 1 ,19707   ,763,763,763
BEGIN DESCRIPTION:
Mapping XS add3a021
END DESCRIPTION:
XS GIS Cut Line= 5
      2585438.28      13436592.7      2586131.88     13434842.28
      2586611.04     13433769.36      2586715.21     13432618.32
      2586319.13     13431027.52
#Sta/Elev= 30
  1949.1   93.76  2807.1   92.88  2854.2   91.84  2936.3   91.63    2947   92.24
  2968.5   96.92  2990.3   97.32    3033   90.51  3129.8   90.33  3176.8   94.89
  3195.3   94.23  3260.5   91.96  3538.6   92.92  4092.8   91.89  4252.3   92.09
  4676.5   90.48  4710.4   91.88    4724   90.28  4748.9   91.51  4892.4   89.76
    4968   90.88  5026.3   89.55    5029   89.51  5029.3   89.01  5033.9   89.51
    5403   92.99  6095.8   95.94  6897.8   96.16  7050.4   95.03  7802.1   96.31
#Mann= 11 ,-1 , 0
  1949.1     .05       0  2854.2     .07       0  3195.3     .05       0
  4092.8     .07       0  4252.3     .05       0  4676.5    .035       0
    4724     .05       0  4892.4      .1       0  5026.3     .05       0
    5029     .05       0  5033.9     .05       0
Bank Sta=5029,5033.9
XS Rating Curve= 0 ,0
Exp/Cntr=0.3,0.1

Type RM Length L Ch R = 1 ,18944   ,1357,1357,1357
BEGIN DESCRIPTION:
Mapping XS 68824560
END DESCRIPTION:
XS GIS Cut Line= 5
      2585743.82     13436731.22      2586954.79     13434826.66
      2587204.79     13433748.53      2587199.59     13432857.91
      2586467.45     13431118.31
#Sta/Elev= 30
  1641.2   93.37  2457.2   91.65  2712.1   90.17  2827.3   90.31  2848.4   91.39
  3270.1   92.15  4498.7   91.85  4577.4      91  4599.3   92.44  4608.2   92.12
  4618.4   90.28  4649.2   91.57  4741.6   90.76  4759.7   91.76  4799.8   89.53
  4800.2   89.03  4804.8   89.53  4864.8   93.22  4905.8   90.41  4998.2   89.92
  5048.4    91.5  5078.4   89.64  5368.4   92.84  5688.4   92.97  6147.5   95.11
  6435.8   95.47  7101.8   93.73  7178.5   94.95  7413.8   94.51  7782.9   96.08
#Mann= 5 ,-1 , 0
  1641.2     .05       0  4498.7    .035       0  4599.3     .05       0
  4799.8     .05       0  4804.8     .05       0
Bank Sta=4799.8,4804.8
XS Rating Curve= 0 ,0
Exp/Cntr=0.3,0.1

Type RM Length L Ch R = 1 ,17587   ,550,550,550
BEGIN DESCRIPTION:
Mapping XS a0585d08
END DESCRIPTION:
XS GIS Cut Line= 6
      2586277.54     13437082.49       2587549.7     13435833.24
      2588387.09     13434425.61      2588293.34     13433561.03
       2588147.5     13432857.91      2586476.55     13430830.17
#Sta/Elev= 30
  1276.9   93.31  1895.6   92.51  1966.3   90.81  1980.5   91.66  2673.5   88.97
  2779.5   89.71  2807.8   88.68  3354.2   91.47  4585.6   90.33  4747.5   89.98
  4819.1   90.27  5007.6   85.87    5008   85.37  5012.7   85.87  5046.1    85.9
  5292.5   86.59  5432.6   88.93  5757.4   90.13  5781.9   91.24  5798.2    89.6
  5818.7   91.11  5961.6   89.87  7207.9   89.76  7269.9   89.33  7303.7   91.23
  7376.8   91.48  7570.1   90.55  8307.1   90.77  8823.6   95.83    8913   96.08
#Mann= 10 ,-1 , 0
  1276.9     .05       0  4585.6    .035       0  4747.5     .05       0
  5007.6     .05       0  5012.7     .05       0  5046.1    .033       0
  5292.5     .05       0  7207.9     .07       0  7570.1     .05       0
  8823.6     .07       0
Bank Sta=5007.6,5012.7
XS Rating Curve= 0 ,0
Exp/Cntr=0.3,0.1

Type RM Length L Ch R = 1 ,17037   ,672,672,672
BEGIN DESCRIPTION:
TRIB 2-8 TO GUADALUPE RIVER 26.0
END DESCRIPTION:
XS GIS Cut Line= 4
      2588411.38     13435731.64      2588764.86     13433874.89
      2588626.92       13433240.      2588001.66     13432120.47
#Sta/Elev= 30
  3109.9   90.49  3321.4   90.52  3586.2   91.05  3714.6   91.21  3722.9   91.24
  4082.1   90.98  4165.2   90.44    4182   91.05  4481.6   90.52  4613.1   89.92
  4650.9   88.92    4664   89.59  4781.3   87.39  4826.8   86.75  4847.2   84.37
  4856.4   84.82  4881.2   84.11  5016.5    80.1  5016.9    79.6  5021.7    80.1
  5082.3    83.2    5266   88.25  5396.8   89.72  5539.1   89.58  5544.2   90.37
    5573   89.46  5593.4   90.37  5613.9   89.61  5824.7   90.51    6932   90.19
#Mann= 14 ,-1 , 0
  3109.9     .05       0  3321.4     .07       0  3586.2     .05       0
  3714.6     .07       0  3722.9     .05       0  4082.1    .035       0
    4182     .05       0  4481.6     .07       0  4781.3    .035       0
  4856.4     .07       0  4881.2    .035       0  5016.5    .035       0
  5021.7    .035       0  5082.3     .05       0
Bank Sta=5016.5,5021.7
XS Rating Curve= 0 ,0
Exp/Cntr=0.3,0.1

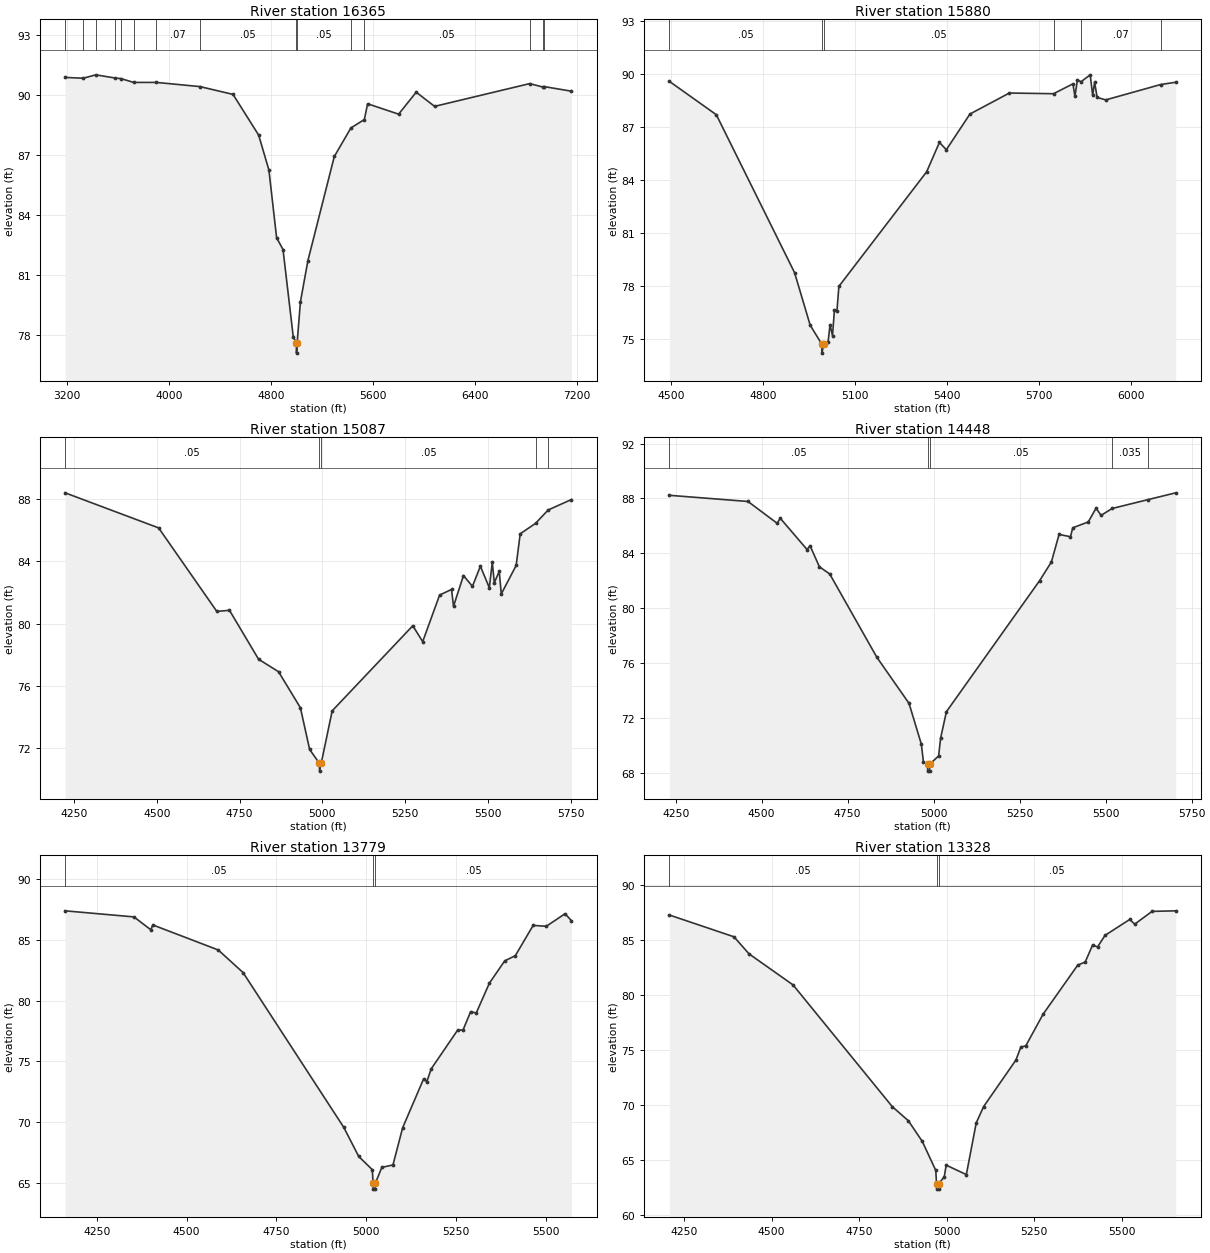
Type RM Length L Ch R = 1 ,16365   ,485,485,485
BEGIN DESCRIPTION:
TRIB 2-8 TO GUADALUPE RIVER 25.0
END DESCRIPTION:
XS GIS Cut Line= 3
        2589175.     13435624.96        2589375.       13433825.
      2588174.98     13432024.97
#Sta/Elev= 30
  3184.1   90.89  3326.2   90.85  3425.1   91.02  3577.1   90.86    3623   90.83
    3722   90.64  3901.2   90.64  4243.1   90.43  4502.1   90.04  4703.4      88
  4783.8   86.25  4844.2   82.86  4894.5   82.27    4975   77.89    5000   77.58
  5000.4   77.08  5005.3   77.58  5031.2   79.65  5089.8   81.71  5297.1   86.93
  5427.6   88.36  5532.9   88.78  5558.5   89.57  5801.9   89.05  5940.1   90.15
  6084.3   89.44  6830.9   90.58  6932.8   90.41    6945   90.43  7158.5    90.2
#Mann= 15 ,-1 , 0
  3184.1     .07       0  3326.2     .05       0  3425.1    .035       0
  3577.1     .05       0    3623     .07       0    3722     .05       0
  3901.2     .07       0  4243.1     .05       0    5000     .05       0
  5005.3     .05       0  5427.6    .035       0  5532.9     .05       0
  6830.9     .07       0  6932.8     .05       0    6945     .07       0
Bank Sta=5000,5005.3
XS Rating Curve= 0 ,0
Exp/Cntr=0.3,0.1

Type RM Length L Ch R = 1 ,15880   ,793,793,793
BEGIN DESCRIPTION:
TRIB 2-8 TO GUADALUPE RIVER 24.0
END DESCRIPTION:
XS GIS Cut Line= 3
        2589925.     13434224.98        2589825.       13433725.
      2588924.97     13433024.98
#Sta/Elev= 30
  4495.3   89.57  4648.3   87.68  4903.2   78.74  4954.2   75.76  4992.3   74.68
  4992.7   74.18  4997.6   74.68  5012.4   74.79  5018.8   75.79  5026.9   75.17
  5033.2   76.64  5041.4   76.57  5047.7   77.96  5333.7   84.45  5375.3   86.11
  5397.9    85.7  5474.8   87.72  5603.3   88.91  5747.1   88.87  5810.5   89.43
  5816.9   88.72    5825   89.65    5837   89.55  5866.7   89.94  5874.8   88.78
  5881.1   89.52  5889.3   88.66  5917.3   88.52  6096.2   89.39  6145.4   89.52
#Mann= 6 ,-1 , 0
  4495.3     .05       0  4992.3     .05       0  4997.6     .05       0
  5747.1    .035       0    5837     .07       0  6096.2     .05       0
Bank Sta=4992.3,4997.6
XS Rating Curve= 0 ,0
Exp/Cntr=0.3,0.1

Type RM Length L Ch R = 1 ,15087   ,639,639,639
BEGIN DESCRIPTION:
Mapping XS 35a076ef
END DESCRIPTION:
XS GIS Cut Line= 3
      2590453.59     13433897.41      2590084.68       13433203.
      2589466.16     13432790.65
#Sta/Elev= 30
  4222.8    88.4  4505.3   86.15  4681.1   80.79  4719.4   80.86  4807.3   77.72
  4867.6   76.92  4933.6   74.61  4961.6   71.93  4991.1   71.04  4991.5   70.54
  4996.5   71.04  5029.7   74.41  5273.2   79.87  5303.1   78.85  5354.2   81.84
  5390.2    82.2  5396.2   81.12  5426.3   83.09  5453.4    82.4  5477.4   83.69
  5504.4   82.31  5513.4   83.95  5519.4   82.63  5534.4   83.36  5540.5   81.91
  5585.5   83.74  5597.7   85.77    5644   86.44  5682.2    87.3  5752.5   87.97
#Mann= 5 ,-1 , 0
  4222.8     .05       0  4991.1     .05       0  4996.5     .05       0
    5644    .035       0  5682.2     .05       0
Bank Sta=4991.1,4996.5
XS Rating Curve= 0 ,0
Exp/Cntr=0.3,0.1

Type RM Length L Ch R = 1 ,14448   ,669,669,669
BEGIN DESCRIPTION:
Mapping XS 0ddaa103
END DESCRIPTION:
XS GIS Cut Line= 3
      2590822.55     13433344.09       2590388.5     13432703.86
      2589759.55     13432400.23
#Sta/Elev= 30
  4231.8   88.23  4460.3   87.78  4545.1   86.19    4554   86.56  4631.9   84.28
  4640.8   84.55  4667.9   83.02  4697.8    82.5  4834.8   76.43  4928.4   73.07
  4964.3   70.09  4970.4   68.78  4982.2   68.63  4982.7   68.13    4988   68.13
  4988.5   68.63  5014.5   69.24  5020.3   70.54  5037.1   72.46  5308.3   82.02
  5342.3   83.37  5364.6   85.38  5397.8   85.21  5404.3   85.86  5449.5   86.29
  5472.1   87.29  5486.7   86.77  5519.1   87.27    5624   87.92  5703.7   88.41
#Mann= 5 ,-1 , 0
  4231.8     .05       0  4982.2     .05       0  4988.5     .05       0
  5519.1    .035       0    5624     .05       0
Bank Sta=4982.2,4988.5
XS Rating Curve= 0 ,0
Exp/Cntr=0.3,0.1

Type RM Length L Ch R = 1 ,13779   ,451,451,451
BEGIN DESCRIPTION:
Mapping XS c66588e8
END DESCRIPTION:
XS GIS Cut Line= 3
      2591115.51     13432996.86      2590779.13     13432215.58
      2590301.67      13431922.6
#Sta/Elev= 30
  4161.3   87.39  4353.1   86.89  4400.1   85.83  4405.6   86.23  4587.9   84.17
  4657.2   82.31  4937.8   69.57  4979.4   67.18  5017.3   66.09  5019.4   64.99
  5019.9   64.49  5025.3   64.49  5025.8   64.99  5043.9   66.28  5074.8   66.48
  5101.9   69.55  5159.9   73.54  5169.3   73.34  5181.2   74.38  5254.7   77.56
  5270.1   77.59  5291.4    79.1  5306.8   78.98  5343.5   81.44  5386.1   83.27
  5415.7    83.7  5465.4   86.19  5502.1   86.12  5554.3   87.15  5572.1   86.58
#Mann= 3 ,-1 , 0
  4161.3     .05       0  5019.4     .05       0  5025.8     .05       0
Bank Sta=5019.4,5025.8
XS Rating Curve= 0 ,0
Exp/Cntr=0.3,0.1

Type RM Length L Ch R = 1 ,13328   ,322,322,322
BEGIN DESCRIPTION:
Mapping XS 32e0f523
END DESCRIPTION:
XS GIS Cut Line= 3
      2591441.03     13432736.45      2591148.05     13431998.57
       2590681.5     13431542.86
#Sta/Elev= 30
  4208.3   87.23  4392.8   85.25  4435.8    83.7  4561.5   80.88  4844.7   69.83
  4890.8   68.54  4930.7   66.66  4969.1   64.03  4971.3   62.83  4971.8   62.33
  4977.3   62.33  4977.8   62.83  4993.4   63.45  4998.8   64.51  5056.4   63.65
  5084.7   68.35  5105.8   69.83  5197.9   74.05    5212   75.23  5226.2   75.35
  5275.6   78.22  5374.6   82.68  5395.9   82.96    5417    84.5  5431.2   84.33
  5452.5   85.38  5523.2   86.83  5537.3    86.4  5586.8   87.56  5654.4   87.61
#Mann= 3 ,-1 , 0
  4208.3     .05       0  4971.3     .05       0  4977.8     .05       0
Bank Sta=4971.3,4977.8
XS Rating Curve= 0 ,0
Exp/Cntr=0.3,0.1

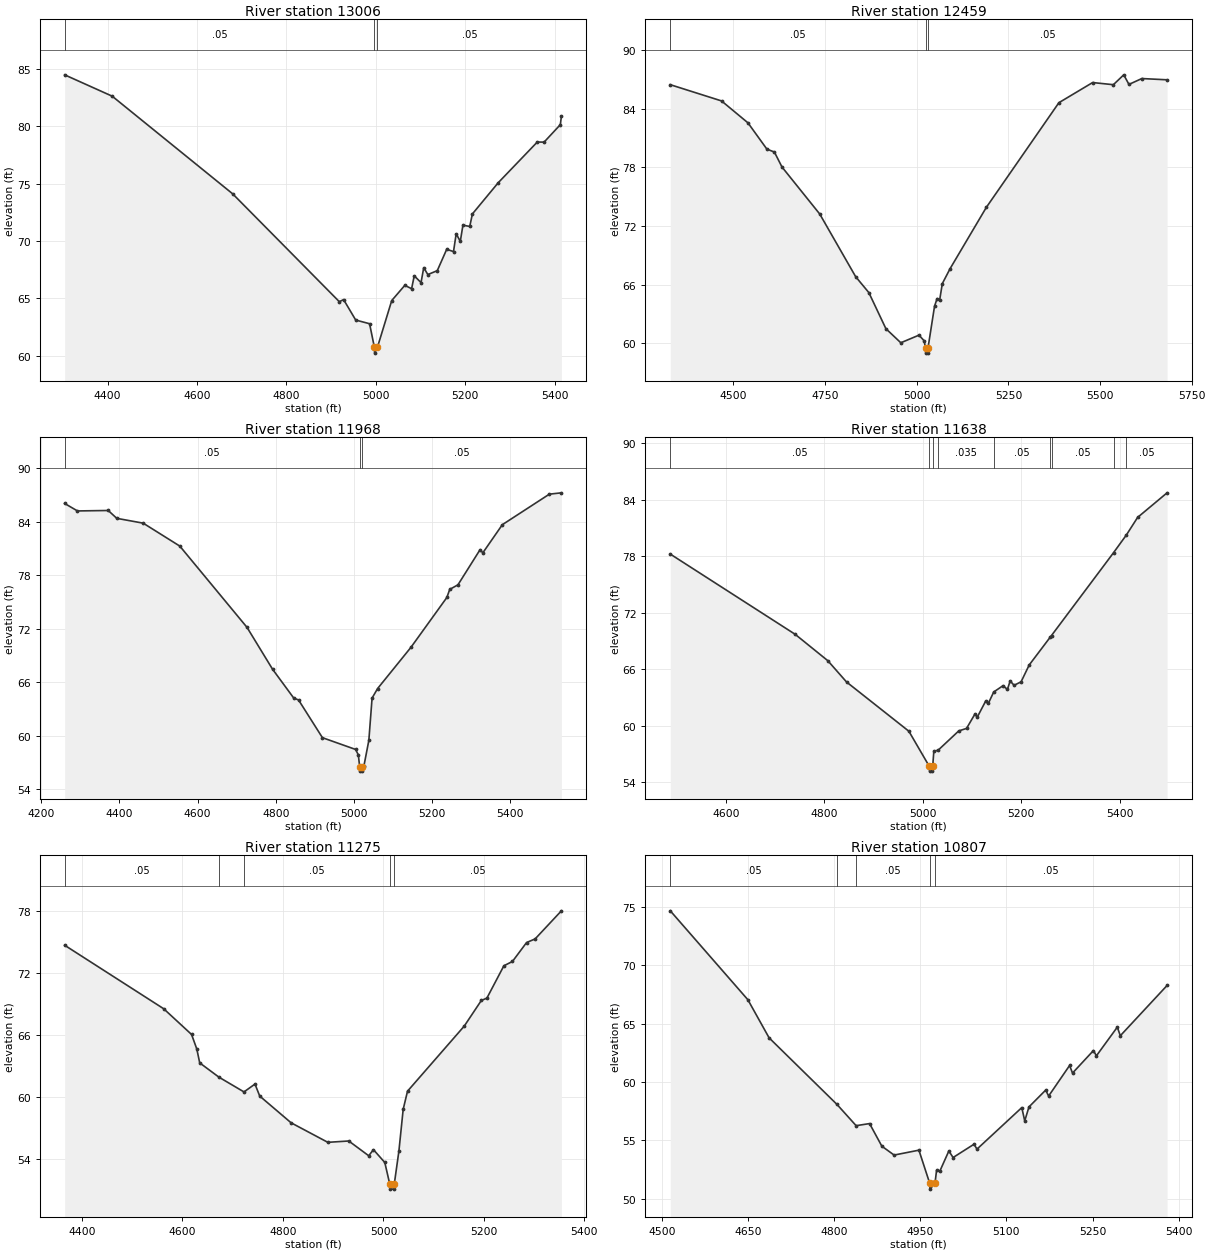
Type RM Length L Ch R = 1 ,13006   ,547,547,547
BEGIN DESCRIPTION:
Mapping XS 57f2bf35
END DESCRIPTION:
XS GIS Cut Line= 3
      2591755.71     13432400.07      2591386.77     13431792.41
      2591169.86      13431456.2
#Sta/Elev= 30
  4303.8   84.47  4410.2   82.61  4679.6   74.11  4918.1   64.72  4927.7    64.9
  4954.8   63.12  4985.8    62.8  4996.6   60.74  4997.1   60.24  5003.3   60.74
  5035.4   64.82  5064.6   66.14  5079.8   65.85  5085.7   66.97  5100.9   66.38
  5106.9   67.68  5116.1   67.08  5137.2   67.42  5158.3   69.28  5173.5   69.08
  5179.5   70.63  5188.7   69.97  5194.6   71.38  5209.8   71.27  5215.8   72.36
  5273.4   75.07  5360.9   78.62  5376.1   78.61  5412.4   80.13  5414.8   80.86
#Mann= 3 ,-1 , 0
  4303.8     .05       0  4996.6     .05       0  5003.3     .05       0
Bank Sta=4996.6,5003.3
XS Rating Curve= 0 ,0
Exp/Cntr=0.3,0.1

Type RM Length L Ch R = 1 ,12459   ,491,491,491
BEGIN DESCRIPTION:
Mapping XS 28485217
END DESCRIPTION:
XS GIS Cut Line= 3
       2591972.7     13432150.48      2591820.79     13431542.84
       2591310.8     13431021.99
#Sta/Elev= 30
  4327.6   86.45  4467.4   84.79  4539.4   82.55  4591.1   79.86  4611.6   79.56
  4632.3   78.03  4735.3   73.22  4833.3   66.81  4869.3   65.18  4915.8   61.49
  4956.5   60.05  5006.1   60.83  5020.2   60.25  5023.9   59.49  5024.4   58.99
  5030.1   58.99  5030.6   59.49  5048.5   63.79  5055.5   64.57  5062.7   64.47
  5069.7    66.1  5090.9   67.63  5189.8    73.9  5387.8   84.61  5479.8   86.67
  5536.4   86.45  5564.7   87.46  5578.9   86.48  5614.1   87.08  5682.9   86.95
#Mann= 3 ,-1 , 0
  4327.6     .05       0  5023.9     .05       0  5030.6     .05       0
Bank Sta=5023.9,5030.6
XS Rating Curve= 0 ,0
Exp/Cntr=0.3,0.1

Type RM Length L Ch R = 1 ,11968   ,330,330,330
BEGIN DESCRIPTION:
Mapping XS 0670e92e
END DESCRIPTION:
XS GIS Cut Line= 3
      2592352.48     13431879.21      2592135.46     13431325.83
      2591636.34      13430870.1
#Sta/Elev= 30
  4260.1   86.04  4292.9    85.2  4371.6   85.25  4393.5   84.37    4461   83.83
  4554.6   81.26  4726.5   72.15  4791.8   67.46  4846.1   64.22  4858.2   64.02
  4919.3   59.79  5004.1   58.47  5011.2   57.86  5014.5   56.54    5015   56.04
  5020.8   56.04  5021.3   56.54  5025.4   56.62    5038   59.48  5046.3   64.23
  5060.5    65.3  5145.6   69.91  5237.5    75.5  5244.9   76.41  5265.9   76.92
  5322.6   80.87  5329.4    80.5  5379.4   83.66  5499.6   87.08  5530.4   87.23
#Mann= 3 ,-1 , 0
  4260.1     .05       0  5014.5     .05       0  5021.3     .05       0
Bank Sta=5014.5,5021.3
XS Rating Curve= 0 ,0
Exp/Cntr=0.3,0.1

Type RM Length L Ch R = 1 ,11638   ,363,363,363
BEGIN DESCRIPTION:
Mapping XS 00f050b7
END DESCRIPTION:
XS GIS Cut Line= 4
      2592351.96     13431554.96      2592363.25     13431201.22
      2592178.86     13430843.73       2591990.7     13430674.39
#Sta/Elev= 30
  4486.9   78.22  4740.5    69.7    4807   66.89    4845   64.63  4971.6    59.4
  5013.2   55.66  5013.7   55.16  5019.5   55.16    5020   55.66  5022.3   57.25
  5031.4    57.4  5072.9   59.43  5088.8    59.7  5105.3   61.18    5111   60.94
  5127.5   62.59  5133.1   62.36    5144   63.57  5162.9   64.24  5171.8   63.84
  5177.4   64.74  5185.4   64.28  5199.6   64.65  5216.1   66.44  5258.6   69.38
  5261.4   69.57  5387.6   78.38  5413.5   80.25  5436.4   82.12  5496.2   84.73
#Mann= 9 ,-1 , 0
  4486.9     .05       0  5013.2     .05       0    5020     .05       0
  5031.4    .035       0    5144     .05       0  5258.6    .035       0
  5261.4     .05       0  5387.6    .035       0  5413.5     .05       0
Bank Sta=5013.2,5020
XS Rating Curve= 0 ,0
Exp/Cntr=0.3,0.1

Type RM Length L Ch R = 1 ,11275   ,468,468,468
BEGIN DESCRIPTION:
Mapping XS b6d115ed
END DESCRIPTION:
XS GIS Cut Line= 3
      2592393.35     13431487.21      2592566.45     13430903.94
      2592732.03     13430561.48
#Sta/Elev= 30
  4365.4    74.7  4562.6   68.55  4618.1   66.06  4628.5   64.65  4634.3   63.31
  4672.5   61.93  4722.4    60.5  4744.3   61.26  4753.7    60.1  4816.2   57.51
  4889.3   55.62    4931   55.75  4970.7   54.32  4980.1   54.91  5002.7   53.67
  5012.5   51.59    5013   51.09  5021.1   51.09  5021.6   51.59  5030.8   54.79
  5039.3   58.82  5047.9   60.57  5160.8   66.87  5194.8   69.35  5205.9   69.58
  5239.7   72.71  5256.8   73.13  5284.9   74.96  5301.9   75.31  5354.2   78.03
#Mann= 5 ,-1 , 0
  4365.4     .05       0  4672.5    .035       0  4722.4     .05       0
  5012.5     .05       0  5021.6     .05       0
Bank Sta=5012.5,5021.6
XS Rating Curve= 0 ,0
Exp/Cntr=0.3,0.1

Type RM Length L Ch R = 1 ,10807   ,433,433,433
BEGIN DESCRIPTION:
Mapping XS 8db05ab8
END DESCRIPTION:
XS GIS Cut Line= 3
      2592610.74     13431626.15      2592860.72     13431209.51
      2592770.46      13430841.5
#Sta/Elev= 30
  4514.9   74.67  4649.9   67.05  4686.9   63.78  4805.1   58.07  4838.4   56.25
  4861.8   56.43  4883.2   54.49  4904.5   53.73  4947.7   54.15  4966.5   51.31
    4967   50.81  4975.7   51.31  4978.4   52.41  4984.2   52.36  4999.8   54.08
  5007.2   53.52  5043.6   54.66  5048.8   54.24  5126.8    57.8  5131.9   56.66
  5139.3   57.86  5168.4    59.3  5173.5   58.79    5210   61.41  5215.1   60.76
  5251.5   62.69  5256.7   62.24  5293.1    64.7  5298.3   63.96  5379.7   68.27
#Mann= 5 ,-1 , 0
  4514.9     .05       0  4805.1    .035       0  4838.4     .05       0
  4966.5     .05       0  4975.7     .05       0
Bank Sta=4966.5,4975.7
XS Rating Curve= 0 ,0
Exp/Cntr=0.3,0.1

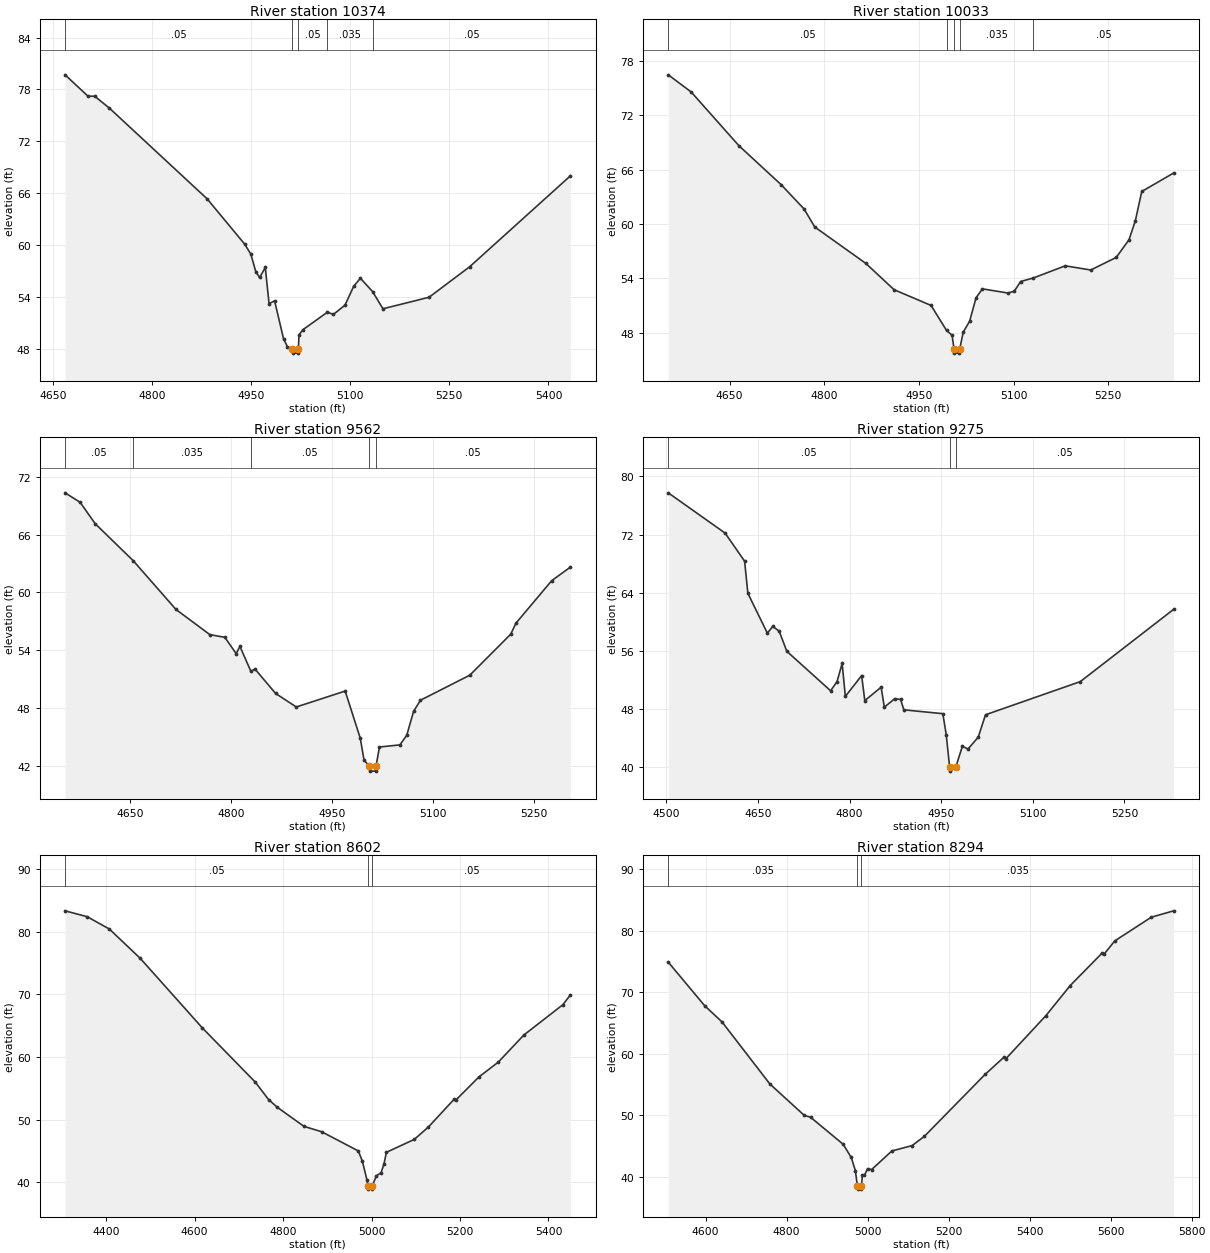
Type RM Length L Ch R = 1 ,10374   ,341,341,341
BEGIN DESCRIPTION:
Mapping XS 71c3392c
END DESCRIPTION:
XS GIS Cut Line= 3
      2592645.44     13431744.23      2592944.06     13431584.51
      2593117.66     13431195.65
#Sta/Elev= 30
  4668.7   79.69  4703.4   77.22  4713.6   77.21  4735.9   75.83  4883.7   65.34
  4940.4   60.11  4949.7   58.96  4957.4   56.88  4963.1   56.25  4971.6   57.41
  4977.3   53.22  4985.7   53.55  4999.2   49.16  5005.1   48.25  5012.5      48
    5013    47.5  5021.2    47.5  5021.7      48  5022.6   49.61  5028.7   50.22
  5065.7   52.24  5074.5   51.97  5092.2   53.05  5105.4   55.24  5115.5   56.16
    5134   54.61  5149.6   52.63  5219.3   53.96  5280.6   57.48  5433.2   68.01
#Mann= 5 ,-1 , 0
  4668.7     .05       0  5012.5     .05       0  5021.7     .05       0
  5065.7    .035       0    5134     .05       0
Bank Sta=5012.5,5021.7
XS Rating Curve= 0 ,0
Exp/Cntr=0.3,0.1

Type RM Length L Ch R = 1 ,10033   ,471,471,471
BEGIN DESCRIPTION:
TRIB 2-8 TO GUADALUPE RIVER 11.0
END DESCRIPTION:
XS GIS Cut Line= 3
      2592825.02     13431924.99        2593225.       13431725.
      2593274.99     13431375.04
#Sta/Elev= 30
  4552.8   76.46  4589.1   74.57  4664.6   68.65  4731.7   64.34    4768   61.66
  4784.8   59.68  4865.8   55.66  4910.5   52.76  4969.2   51.02  4993.7   48.26
  5002.5   47.73  5005.5   46.26    5006   45.76  5014.2   45.76  5014.7   46.26
  5020.2   48.09  5030.3   49.28  5040.4   51.86  5050.5   52.85  5090.9   52.39
    5101   52.59  5111.1   53.66  5131.2   54.05  5181.8   55.39  5222.2   54.93
  5262.6   56.32  5282.8   58.27  5292.9   60.38    5303   63.59  5353.5   65.63
#Mann= 5 ,-1 , 0
  4552.8     .05       0  4993.7    .035       0  5005.5    .035       0
  5014.7    .035       0  5131.2     .05       0
Bank Sta=5005.5,5014.7
XS Rating Curve= 0 ,0
Exp/Cntr=0.3,0.1

Type RM Length L Ch R = 1 ,9562    ,287,287,287
BEGIN DESCRIPTION:
TRIB 2-8 TO GUADALUPE RIVER 10.0
END DESCRIPTION:
XS GIS Cut Line= 3
      2593825.02     13432225.03        2593625.       13431825.
        2593575.     13431524.99
#Sta/Elev= 30
  4553.1   70.33  4575.5   69.35  4597.9   67.13  4654.5   63.29    4718   58.24
  4768.4   55.63  4790.7   55.35  4807.5   53.66  4813.1   54.41  4829.5   51.81
  4835.4   52.07  4866.2   49.53  4896.9   48.13  4969.6   49.78    4992    44.9
  4997.6   42.64  5005.6   41.98  5006.1   41.48  5014.9   41.48  5015.4   41.98
  5020.6   43.98    5051    44.2  5061.2   45.21  5071.3   47.67  5081.5   48.83
    5155   51.43  5215.8   55.68  5223.4   56.81  5276.6   61.22  5304.5   62.63
#Mann= 5 ,-1 , 0
  4553.1     .05       0  4654.5    .035       0  4829.5     .05       0
  5005.6     .05       0  5015.4     .05       0
Bank Sta=5005.6,5015.4
XS Rating Curve= 0 ,0
Exp/Cntr=0.3,0.1

Type RM Length L Ch R = 1 ,9275    ,673,673,673
BEGIN DESCRIPTION:
Mapping XS 30d3cd97
END DESCRIPTION:
XS GIS Cut Line= 3
       2594049.1     13432247.71      2593897.18     13431781.12
      2593800.43     13431458.61
#Sta/Elev= 30
  4503.1   77.75  4596.2   72.21  4628.1   68.35  4633.4   63.94  4665.3   58.46
  4674.2   59.37  4684.7   58.73  4697.2   55.96  4768.9   50.53  4779.4   51.79
  4787.8   54.29    4793   49.75  4819.7   52.62  4824.9   49.18  4851.6   51.02
  4856.9   48.28    4874   49.45  4883.5   49.33  4888.8   47.91  4952.6   47.38
  4958.2    44.5  4963.8   39.98  4964.3   39.48  4973.6   39.98  4984.6   42.89
  4993.8   42.52  5010.6   44.15  5022.5   47.23  5177.7   51.79  5330.5   61.73
#Mann= 3 ,-1 , 0
  4503.1     .05       0  4963.8     .05       0  4973.6     .05       0
Bank Sta=4963.8,4973.6
XS Rating Curve= 0 ,0
Exp/Cntr=0.3,0.1

Type RM Length L Ch R = 1 ,8602    ,308,308,308
BEGIN DESCRIPTION:
Mapping XS a0011f45
END DESCRIPTION:
XS GIS Cut Line= 3
      2594309.51     13432215.14      2594309.51     13431585.81
      2594147.17     13431098.78
#Sta/Elev= 30
    4307   83.31  4357.1   82.37  4407.1   80.41  4477.1   75.72  4617.1   64.65
  4737.1   55.98  4767.1    53.2  4787.1   51.95  4847.1   48.92  4887.1   48.06
  4970.2   44.99  4979.3   43.35  4989.9   40.29  4991.6    39.4  4992.1    38.9
    5001    38.9  5001.5    39.4    5011   41.03  5021.5   41.51  5028.2   42.92
  5033.5   44.77  5096.7   46.84  5128.4    48.8  5186.3   53.21  5191.6   53.18
  5242.9   56.81  5286.5   59.16  5344.4   63.49  5432.6   68.33  5449.7    69.9
#Mann= 3 ,-1 , 0
    4307     .05       0  4991.6     .05       0  5001.5     .05       0
Bank Sta=4991.6,5001.5
XS Rating Curve= 0 ,0
Exp/Cntr=0.3,0.1

Type RM Length L Ch R = 1 ,8294    ,310,310,310
BEGIN DESCRIPTION:
Mapping XS 0ead8fb6
END DESCRIPTION:
XS GIS Cut Line= 3
      2594497.36     13432064.67      2594544.23      13431585.5
      2594512.98      13430819.9
#Sta/Elev= 30
  4507.8    74.9  4597.9   67.79  4640.4   65.18  4758.7   55.07  4843.6   49.96
  4859.1   49.66  4939.5   45.27  4959.6   43.11  4969.7   40.99  4974.8   38.46
  4975.3   37.96  4984.2   37.96  4984.7   38.46    4987   40.18    4992   40.18
  4999.8   41.29  5009.8   41.14  5059.8   44.17  5109.9   45.05  5139.9   46.54
    5290   56.63  5336.7   59.44  5341.7   59.21  5440.1   66.19  5500.2   71.09
  5579.4   76.41  5584.4   76.26  5610.3   78.36  5700.3   82.21  5755.5   83.25
#Mann= 3 ,-1 , 0
  4507.8    .035       0  4974.8    .035       0  4984.7    .035       0
Bank Sta=4974.8,4984.7
XS Rating Curve= 0 ,0
Exp/Cntr=0.3,0.1

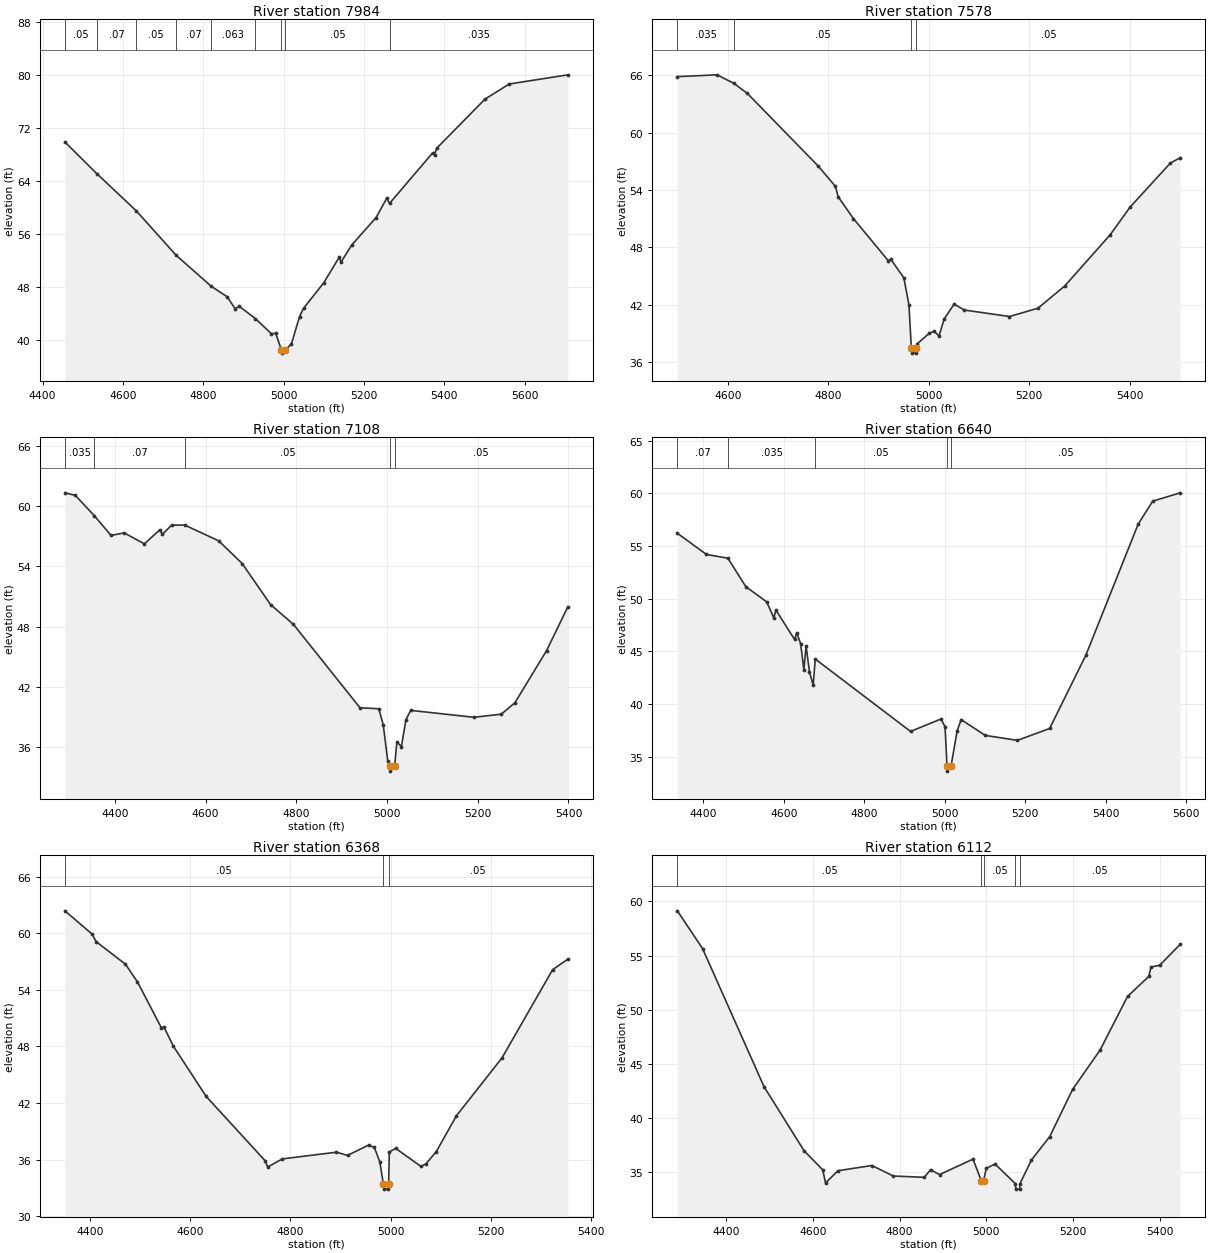
Type RM Length L Ch R = 1 ,7984    ,406,406,406
BEGIN DESCRIPTION:
Mapping XS 85628849
END DESCRIPTION:
XS GIS Cut Line= 3
      2594841.11     13432168.79       2594835.9       13431648.
      2594898.35     13430919.39
#Sta/Elev= 30
  4455.7   69.92    4535   65.14  4633.6    59.5  4732.3   52.81  4820.3   48.09
  4859.5   46.53  4879.5   44.71  4889.5   45.09  4929.7   43.23  4969.5   40.95
  4980.5   40.98  4994.6    38.5  4995.1      38  5004.6    38.5  5019.6   39.39
  5039.7   43.51  5049.8   44.78    5100   48.63  5138.4   52.48  5143.4    51.8
  5170.2   54.38  5230.4    58.5  5257.1   61.44  5263.8   60.63  5370.9   68.26
  5375.9   67.98    5381   68.96  5501.4    76.4  5561.7   78.69  5707.8   80.08
#Mann= 9 ,-1 , 0
  4455.7     .05       0    4535     .07       0  4633.6     .05       0
  4732.3     .07       0  4820.3    .063       0  4929.7     .05       0
  4994.6     .05       0  5004.6     .05       0  5263.8    .035       0
Bank Sta=4994.6,5004.6
XS Rating Curve= 0 ,0
Exp/Cntr=0.3,0.1

Type RM Length L Ch R = 1 ,7578    ,470,470,470
BEGIN DESCRIPTION:
Mapping XS f932d272
END DESCRIPTION:
XS GIS Cut Line= 3
      2595101.61     13432323.66      2595145.01     13431846.23
      2595155.86     13431325.34
#Sta/Elev= 30
  4499.8   65.87  4578.8   66.06  4612.5   65.16    4639   64.12  4779.6   56.54
  4814.1    54.4  4819.8    53.3  4849.9   51.03  4919.5   46.61  4924.5   46.76
  4950.3   44.83  4960.4   42.03  4965.3   37.45  4965.8   36.95  4974.9   36.95
  4975.4   37.45  4977.3   37.94  5000.4   39.01  5010.4   39.24  5020.4   38.75
  5030.4   40.51  5050.4   42.08  5070.5   41.46  5160.5   40.78  5217.1   41.65
  5270.5   43.98  5360.5   49.31  5400.5   52.23  5480.5   56.83  5500.2   57.39
#Mann= 4 ,-1 , 0
  4499.8    .035       0  4612.5     .05       0  4965.3     .05       0
  4975.4     .05       0
Bank Sta=4965.3,4975.4
XS Rating Curve= 0 ,0
Exp/Cntr=0.3,0.1

Type RM Length L Ch R = 1 ,7108    ,468,468,468
BEGIN DESCRIPTION:
Mapping XS 3ab90475
END DESCRIPTION:
XS GIS Cut Line= 3
      2595383.72     13432551.54      2595568.19     13431889.63
        2595579.      13431468.2
#Sta/Elev= 30
    4290   61.32  4312.9   61.07    4355   59.03  4391.6   57.08  4420.6   57.33
  4465.2   56.24  4499.4   57.65  4504.6   57.18  4525.2    58.1    4554   58.11
    4629   56.54  4680.8   54.28  4743.2    50.2  4793.8   48.22  4940.4   39.92
  4981.9   39.82  4991.8    38.2  5001.8   34.57  5006.7   34.11  5007.2   33.61
  5016.8   34.11  5021.8   36.51  5031.8   36.06  5041.8   38.74  5052.3   39.66
  5191.8   38.97  5251.9   39.28  5281.9   40.41  5351.9   45.62  5398.7   49.97
#Mann= 5 ,-1 , 0
    4290    .035       0    4355     .07       0    4554     .05       0
  5006.7     .05       0  5016.8     .05       0
Bank Sta=5006.7,5016.8
XS Rating Curve= 0 ,0
Exp/Cntr=0.3,0.1

Type RM Length L Ch R = 1 ,6640    ,272,272,272
BEGIN DESCRIPTION:
Mapping XS 70d0f83a
END DESCRIPTION:
XS GIS Cut Line= 3
      2595709.25     13432584.07      2595969.67     13432008.99
      2595958.82     13431390.48
#Sta/Elev= 30
  4335.2    56.2  4407.6   54.19  4460.8   53.83  4505.5   51.13  4557.2   49.69
  4574.8   48.18  4580.3    48.9  4626.5   46.12    4632   46.76  4641.6   45.71
  4649.6   43.25  4655.1    45.5  4663.5   43.07  4672.7   41.77    4678   44.26
  4914.7   37.39  4990.5   38.57  5000.5   37.83  5005.4   34.12  5005.9   33.62
  5015.5   34.12  5030.5   37.44  5040.5   38.51  5100.5   37.01  5180.5   36.54
  5260.5   37.67  5350.5   44.63  5480.6   57.08  5516.6   59.25  5585.1   60.04
#Mann= 5 ,-1 , 0
  4335.2     .07       0  4460.8    .035       0    4678     .05       0
  5005.4     .05       0  5015.5     .05       0
Bank Sta=5005.4,5015.5
XS Rating Curve= 0 ,0
Exp/Cntr=0.3,0.1

Type RM Length L Ch R = 1 ,6368    ,256,256,256
BEGIN DESCRIPTION:
TRIB 2-8 TO GUADALUPE RIVER 3.0
END DESCRIPTION:
XS GIS Cut Line= 3
        2595975.     13432525.01        2596225.       13431925.
      2596275.01     13431574.96
#Sta/Elev= 30
  4349.9    62.4  4404.1   59.93  4412.2   59.13  4470.7   56.73  4494.5   54.87
  4542.2      50  4547.6   50.06    4566   48.06  4631.6   42.71  4749.1   35.89
  4754.5   35.21  4783.8   36.07  4891.6   36.78  4913.8   36.44    4956   37.54
  4967.4   37.28  4978.2   35.77  4985.5   33.36    4986   32.86  4995.3   32.86
  4995.8   33.36  4997.2   36.81    5010   37.18  5060.5   35.27  5070.6   35.56
  5090.8   36.83  5131.2   40.65  5222.1   46.79  5323.2   56.16  5353.5   57.27
#Mann= 3 ,-1 , 0
  4349.9     .05       0  4985.5     .05       0  4995.8     .05       0
Bank Sta=4985.5,4995.8
XS Rating Curve= 0 ,0
Exp/Cntr=0.3,0.1

Type RM Length L Ch R = 1 ,6112    ,413,413,413
BEGIN DESCRIPTION:
Mapping XS 5bf8ea66
END DESCRIPTION:
XS GIS Cut Line= 4
      2596049.27     13432480.51      2596470.24     13431985.75
      2596487.61     13431890.26      2596357.47     13431499.85
#Sta/Elev= 30
  4288.2   59.13  4346.2   55.65  4487.9   42.89  4580.1   36.98    4623   35.22
  4629.5   34.01  4658.1   35.14  4736.1   35.62  4785.5   34.65  4856.9   34.53
  4871.2   35.23    4892   34.78  4969.1   36.21  4988.3    34.2  4993.4    34.2
  4999.6   35.36  5019.9   35.75  5066.9   33.94  5067.4   33.44  5076.7   33.44
  5077.2   33.94  5103.7   36.13  5145.8   38.29  5198.5   42.65  5261.8   46.28
    5325   51.23  5373.8   53.07  5379.1   53.95  5398.8    54.1  5446.4   56.04
#Mann= 5 ,-1 , 0
  4288.2     .05       0  4988.3     .05       0  4993.4     .05       0
  5066.9     .05       0  5077.2     .05       0
Bank Sta=4988.3,4993.4
XS Rating Curve= 0 ,0
Exp/Cntr=0.3,0.1

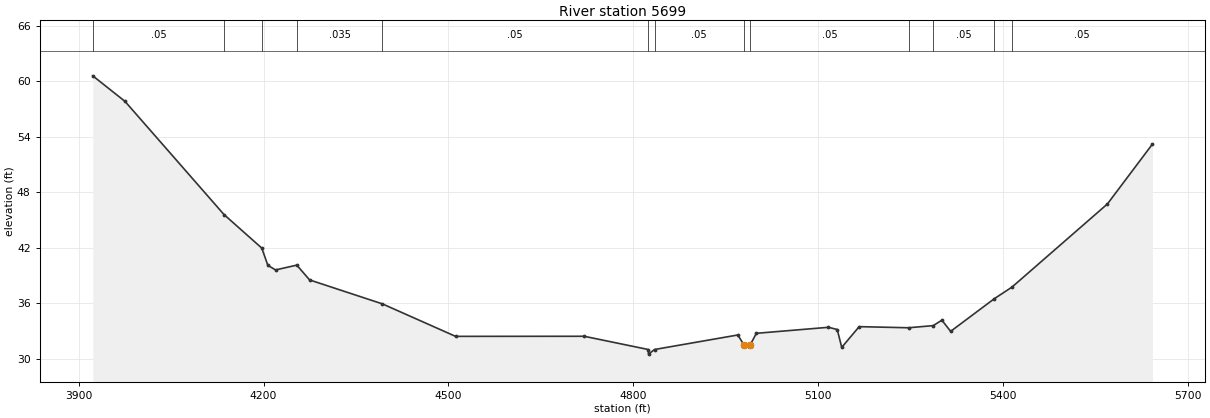
Type RM Length L Ch R = 1 ,5699    ,0,0,0
BEGIN DESCRIPTION:
TRIB 2-8 TO GUADALUPE RIVER 2.0
END DESCRIPTION:
XS GIS Cut Line= 4
      2596057.95     13432545.63      2596865.21     13432155.02
      2596882.57     13431907.62      2596488.82     13431487.91
#Sta/Elev= 30
  3922.7   60.59    3975   57.83  4135.7    45.6  4197.1   41.97  4206.9   40.11
  4219.4   39.61  4253.9   40.13  4274.7   38.53  4392.9   35.94  4511.7   32.43
  4720.5   32.44  4824.4   31.01  4824.9   30.51  4834.7   31.01  4969.9   32.58
  4979.9    31.5  4989.9    31.5    5000   32.76  5117.1   33.41  5131.3   33.17
  5138.6   31.24  5166.9   33.48    5247   33.36  5287.1   33.59  5301.2   34.18
  5315.4   32.97  5386.5   36.51  5414.9   37.75  5569.9   46.74    5643   53.21
#Mann= 13 ,-1 , 0
  3922.7     .05       0  4135.7    .035       0  4197.1     .05       0
  4253.9    .035       0  4392.9     .05       0  4824.4     .05       0
  4834.7     .05       0  4979.9     .05       0  4989.9     .05       0
    5247    .035       0  5287.1     .05       0  5386.5     .07       0
  5414.9     .05       0
Bank Sta=4979.9,4989.9
XS Rating Curve= 0 ,0
Exp/Cntr=0.3,0.1