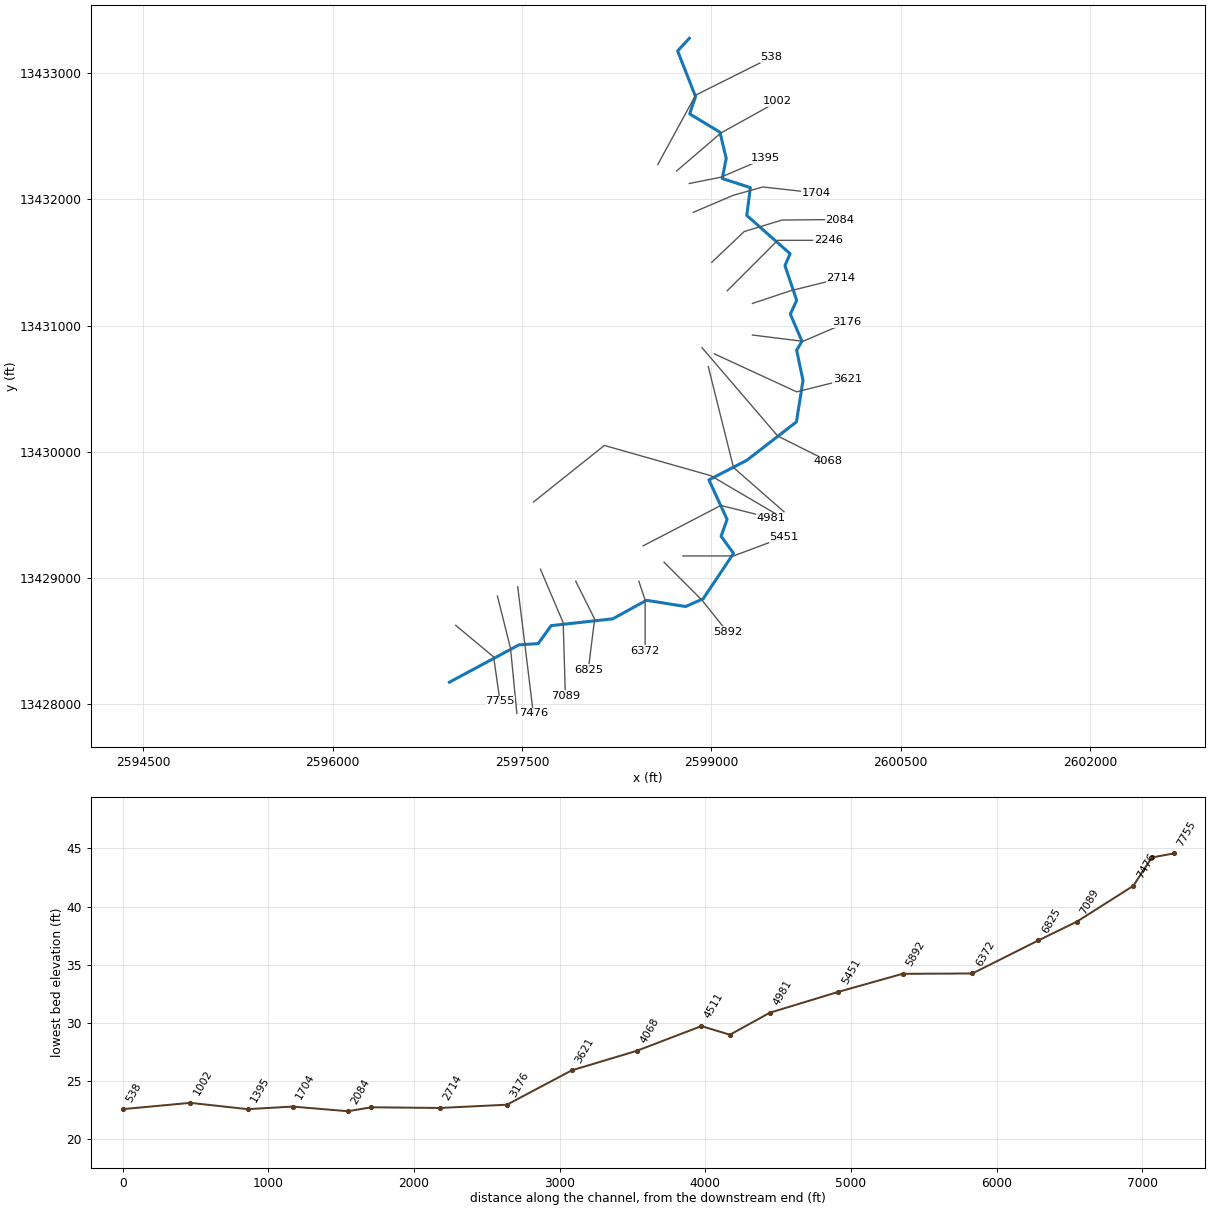
--- TRIB 2_8-1 TO GUADALUPE RIVER.prj (project) ---

Proj Title=TRIB 2_8-1 TO GUADALUPE RIVER Base Level Engineering
Current Plan=p01
Default Exp/Contr=0.3,0.1
English Units
Geom File=g01
Flow File=f01
Plan File=p01
Y Axis Title=Elevation
X Axis Title(PF)=Main Channel Distance
X Axis Title(XS)=Station
BEGIN DESCRIPTION:
TRIB 2_8-1 TO GUADALUPE RIVER
END DESCRIPTION:
DSS Export Rating Curves= 0
DSS Export Rating Curve Sorted= 0
DSS Export Volume Flow Curves= 0
DXF OffsetX= 0
DXF OffsetY= 0
DXF ScaleX= 1
DXF ScaleY= 10

--- TRIB 2_8-1 TO GUADALUPE RIVER.p01 (plan) ---

Plan Title=Multiple Run
Short Identifier=Multiple
Geom File=g01
Flow File=f01
Subcritical Flow
K Sum by GR= 0
Std Step Tol= 0.01
Critical Tol= 0.01
Num of Std Step Trials= 20
Max Error Tol= 0.3
Flow Tol Ratio= 0.001
Split Flow NTrial= 30
Split Flow Tol= 0.02
Split Flow Ratio= 0.02
Log Output Level= 0
Friction Slope Method= 1
Unsteady Friction Slope Method= 2
Unsteady Bridges Friction Slope Method= 1
Parabolic Critical Depth
Global Vel Dist=  1 , 1 , 1
Global Log Level= 0
CheckData=True
Encroach Param= -1, 0, 0, 0
BEGIN DESCRIPTION:
Multiple Run
END DESCRIPTION:

--- TRIB 2_8-1 TO GUADALUPE RIVER.f01 (steady flow) ---

Flow Title=Multiple
Number of Profiles=7
Profile Names=10-year,25-year,50-year,1pct_min,100-year,1pct_plu,500-year
River Rch & RM= TRIB 2_8-1 TO GU,Reach-1,7755
     661    1034    1360     865    1726    3444    2746
River Rch & RM= TRIB 2_8-1 TO GU,Reach-1,7604
     819    1298    1724    1106    2207    4403    3574
River Rch & RM= TRIB 2_8-1 TO GU,Reach-1,5451
     974    1555    2074    1336    2665    5317    4347
Boundary for River Rch & Prof#=TRIB 2_8-1 TO GU,Reach-1,1
Up Type=0
Dn Type=3
Dn Slope=0.005
Boundary for River Rch & Prof#=TRIB 2_8-1 TO GU,Reach-1,2
Up Type=0
Dn Type=3
Dn Slope=0.005
Boundary for River Rch & Prof#=TRIB 2_8-1 TO GU,Reach-1,3
Up Type=0
Dn Type=3
Dn Slope=0.005
Boundary for River Rch & Prof#=TRIB 2_8-1 TO GU,Reach-1,4
Up Type=0
Dn Type=3
Dn Slope=0.005
Boundary for River Rch & Prof#=TRIB 2_8-1 TO GU,Reach-1,5
Up Type=0
Dn Type=3
Dn Slope=0.005
Boundary for River Rch & Prof#=TRIB 2_8-1 TO GU,Reach-1,6
Up Type=0
Dn Type=3
Dn Slope=0.005
Boundary for River Rch & Prof#=TRIB 2_8-1 TO GU,Reach-1,7
Up Type=0
Dn Type=3
Dn Slope=0.005

--- TRIB 2_8-1 TO GUADALUPE RIVER.g01 (geometry) ---

Geom Title=Existing Conditions
Program Version=4.10

River Reach=TRIB 2_8-1 TO GU,Reach-1
Reach XY= 30
        2596925.       13428175.      2597476.56     13428471.24
       2597627.7     13428480.36      2597730.68     13428623.01
      2598219.14     13428677.07       2598485.5     13428823.78
      2598795.05      13428774.4      2598934.71     13428835.75
      2599175.37      13429195.2      2599076.63     13429331.04
      2599124.25     13429464.31      2598980.08     13429777.31
      2599281.05     13429933.16      2599673.38     13430236.81
       2599725.5     13430564.83      2599675.02     13430804.95
      2599717.44       13430875.       2599625.1      13431090.4
      2599675.39       13431200.      2599582.59     13431475.01
      2599623.34     13431568.95      2599279.99     13431872.45
       2599308.6     13432092.61       2599086.1     13432164.68
      2599117.22      13432324.9       2599067.3     13432531.48
      2598828.04     13432676.42      2598874.23     13432814.31
      2598732.22     13433175.11        2598825.       13433275.

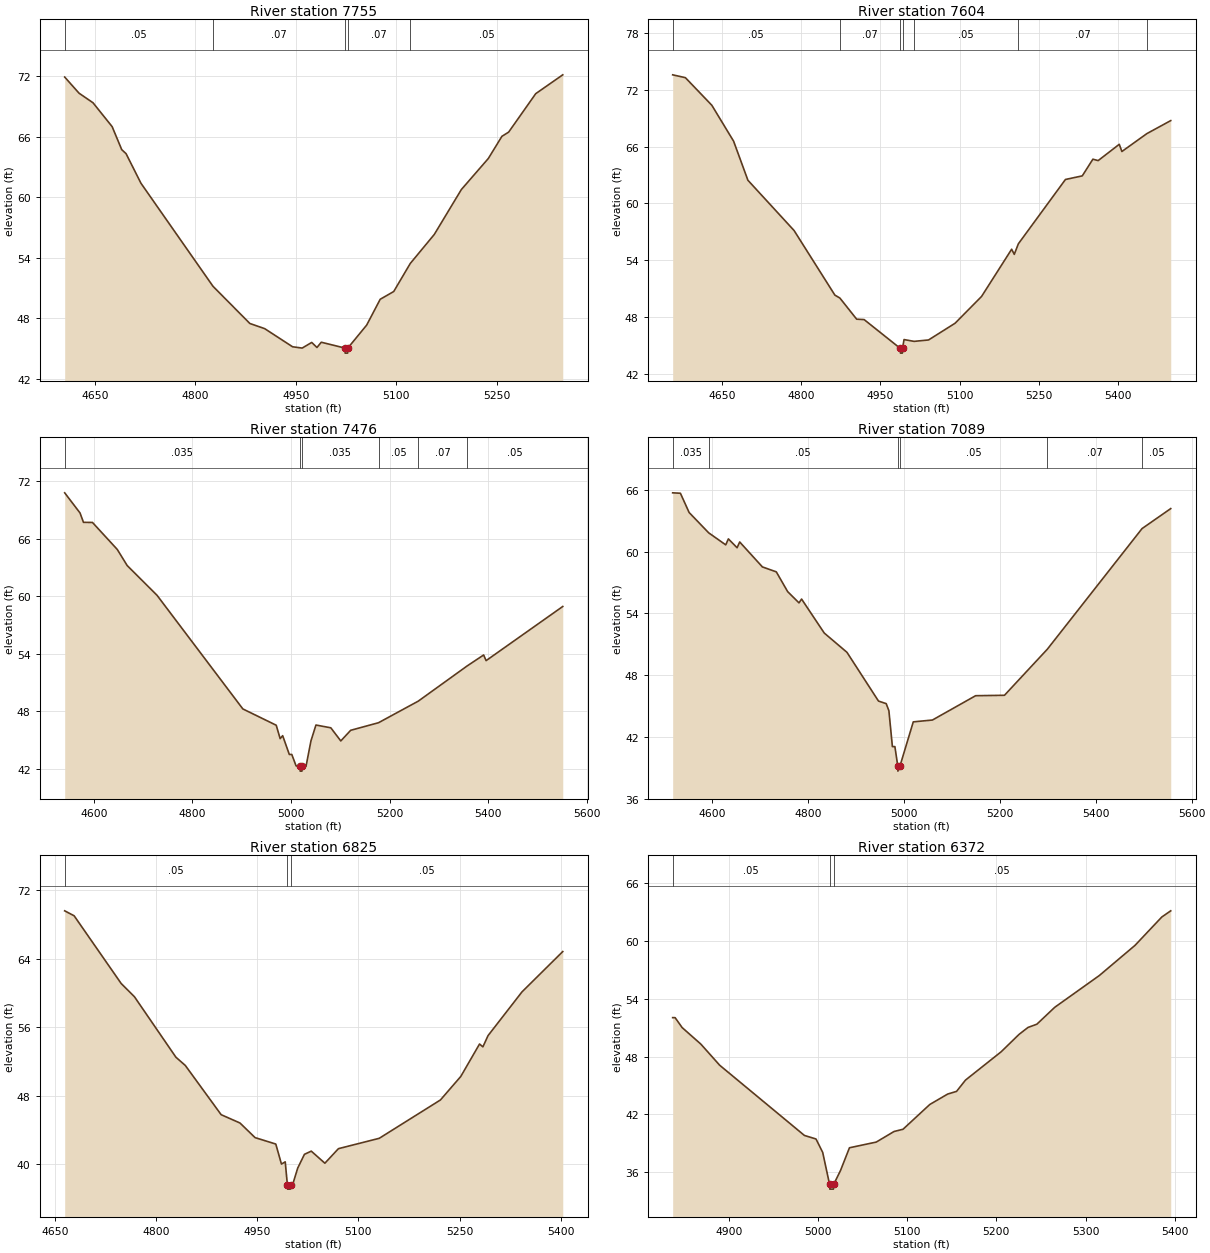
Type RM Length L Ch R = 1 ,7755    ,151,151,151
BEGIN DESCRIPTION:
TRIB 2-8-1 TO GUADALUPE RIVER 17.0
END DESCRIPTION:
XS GIS Cut Line= 3
      2596975.03     13428624.98        2597275.       13428375.
        2597325.     13428025.03
#Sta/Elev= 30
  4604.8   71.94  4626.2   70.34  4647.1   69.39  4675.7   67.02    4690   64.74
  4696.5   64.34  4718.7   61.41  4826.3   51.19  4881.4    47.5  4903.5   46.99
  4945.2   45.19  4959.5   45.06  4973.8   45.62  4981.6   45.12  4988.1   45.64
  5023.5   45.06  5023.8   44.56  5027.4   44.56  5027.7   45.06  5055.9   47.34
  5076.1    49.9  5096.3   50.67    5121   53.45  5156.9   56.33  5197.3   60.78
  5237.7   63.87  5257.9   66.06    5268   66.48  5308.4   70.29  5348.8   72.16
#Mann= 5 ,-1 , 0
  4604.8     .05       0  4826.3     .07       0  5023.5     .05       0
  5027.7     .07       0    5121     .05       0
Bank Sta=5023.5,5027.7
XS Rating Curve= 0 ,0
Exp/Cntr=0.3,0.1

Type RM Length L Ch R = 1 ,7604    ,128,128,128
BEGIN DESCRIPTION:
Mapping XS e581a98a
END DESCRIPTION:
XS GIS Cut Line= 3
      2597305.09     13428857.02      2597409.25     13428440.39
      2597458.97     13427928.05
#Sta/Elev= 30
  4556.2   73.57  4580.3   73.27  4630.4   70.36  4671.7   66.57  4698.8   62.45
  4786.4   57.14  4863.7   50.33  4873.2   50.02    4905   47.79  4919.1   47.75
  4987.7   44.71    4988   44.21  4991.6   44.21  4991.9   44.71  4994.8   45.64
  5013.8   45.45  5041.3    45.6  5091.5   47.36  5141.8   50.19  5198.8   55.17
  5203.8   54.63  5211.5   55.74  5300.8   62.53  5332.7   62.91  5352.8   64.67
  5362.8   64.52  5402.8   66.24  5407.8   65.48  5455.2   67.37  5500.4   68.74
#Mann= 7 ,-1 , 0
  4556.2     .05       0  4873.2     .07       0  4987.7     .05       0
  4991.9     .07       0  5013.8     .05       0  5211.5     .07       0
  5455.2    .035       0
Bank Sta=4987.7,4991.9
XS Rating Curve= 0 ,0
Exp/Cntr=0.3,0.1

Type RM Length L Ch R = 1 ,7476    ,387,387,387
BEGIN DESCRIPTION:
Mapping XS cbfa3538
END DESCRIPTION:
XS GIS Cut Line= 3
      2597465.67     13428930.84      2597522.09     13428477.28
      2597589.13     13427928.01
#Sta/Elev= 30
    4541   70.81  4572.1   68.71  4579.1   67.73  4597.3   67.72  4647.7    64.9
  4667.8   63.22  4728.3   60.12  4902.4   48.26  4970.1   46.56  4978.1   45.16
  4983.2   45.47  4996.7   43.51  5001.7   43.51  5010.4   42.32  5018.4   42.27
  5018.7   41.77  5022.3   41.77  5022.6   42.27  5030.6   42.28  5040.6   44.93
  5050.7   46.58  5080.9   46.29  5101.1   44.92  5121.2   46.03  5177.6   46.82
  5258.2   49.07  5357.3   52.74  5390.9   53.89  5395.9    53.3  5551.4   58.95
#Mann= 6 ,-1 , 0
    4541    .035       0  5018.4    .035       0  5022.6    .035       0
  5177.6     .05       0  5258.2     .07       0  5357.3     .05       0
Bank Sta=5018.4,5022.6
XS Rating Curve= 0 ,0
Exp/Cntr=0.3,0.1

Type RM Length L Ch R = 1 ,7089    ,264,264,264
BEGIN DESCRIPTION:
Mapping XS fcd31f98
END DESCRIPTION:
XS GIS Cut Line= 3
      2597645.79     13429069.73      2597825.91     13428646.55
      2597843.23     13428068.52
#Sta/Elev= 30
  4518.2   65.71  4534.3   65.67  4552.5    63.8  4593.2   61.83  4628.8   60.66
  4634.3   61.24  4652.5   60.38  4657.9   60.94  4705.2   58.52  4734.2   58.04
  4757.9   56.12  4781.5   55.03  4786.9    55.4  4834.2    52.1  4881.5   50.23
  4947.2    45.5  4963.3   45.25  4968.9   44.56  4976.2   41.08  4981.4   41.08
  4987.4    39.2  4987.7    38.7    4992    39.2  5019.7   43.48  5059.7   43.66
  5149.7   46.02  5209.8   46.06  5299.3   50.54  5496.6   62.24  5556.4   64.18
#Mann= 6 ,-1 , 0
  4518.2    .035       0  4593.2     .05       0  4987.4     .05       0
    4992     .05       0  5299.3     .07       0  5496.6     .05       0
Bank Sta=4987.4,4992
XS Rating Curve= 0 ,0
Exp/Cntr=0.3,0.1

Type RM Length L Ch R = 1 ,6825    ,453,453,453
BEGIN DESCRIPTION:
TRIB 2-8-1 TO GUADALUPE RIVER 15.0
END DESCRIPTION:
XS GIS Cut Line= 3
      2597925.01     13428974.98        2598075.       13428675.
        2598025.     13428275.01
#Sta/Elev= 30
  4664.6   69.62  4678.6   69.04  4748.4   61.12    4768   59.58  4829.5   52.51
  4843.5   51.54  4896.6   45.79  4924.5   44.82  4946.9   43.11  4977.6   42.36
    4986   40.02  4991.6   40.28  4994.8   37.59  4995.2   37.09  4999.2   37.09
  4999.5   37.59  5002.5   37.59  5010.1   39.55  5020.1   41.16  5030.2   41.53
  5050.4   40.12  5070.5   41.82    5131   43.03  5221.7   47.51  5251.9   50.26
  5279.7   54.05  5284.7   53.72  5292.3   55.03  5342.6   60.14  5403.1   64.86
#Mann= 3 ,-1 , 0
  4664.6     .05       0  4994.8     .05       0  4999.5     .05       0
Bank Sta=4994.8,4999.5
XS Rating Curve= 0 ,0
Exp/Cntr=0.3,0.1

Type RM Length L Ch R = 1 ,6372    ,480,480,480
BEGIN DESCRIPTION:
TRIB 2-8-1 TO GUADALUPE RIVER 14.0
END DESCRIPTION:
XS GIS Cut Line= 3
      2598424.99     13428975.02        2598475.       13428825.
        2598475.     13428425.03
#Sta/Elev= 30
  4837.3   52.04    4840   52.04  4847.9   51.01  4868.9   49.29    4890    47.1
  4984.9   39.82  4997.9   39.45  5005.4   38.06  5013.1   34.75  5013.4   34.25
  5017.4   34.25  5017.8   34.75  5025.4   36.19  5035.4   38.54  5065.4   39.13
  5085.4   40.23  5095.4   40.46  5125.4   43.03  5145.4   44.11  5155.4   44.39
  5165.4   45.56  5205.4    48.5  5225.4    50.3  5235.4   51.02  5245.4   51.36
  5265.4   53.11  5315.4   56.41  5355.4   59.54  5385.4   62.48  5395.4   63.12
#Mann= 3 ,-1 , 0
  4837.3     .05       0  5013.1     .05       0  5017.8     .05       0
Bank Sta=5013.1,5017.8
XS Rating Curve= 0 ,0
Exp/Cntr=0.3,0.1

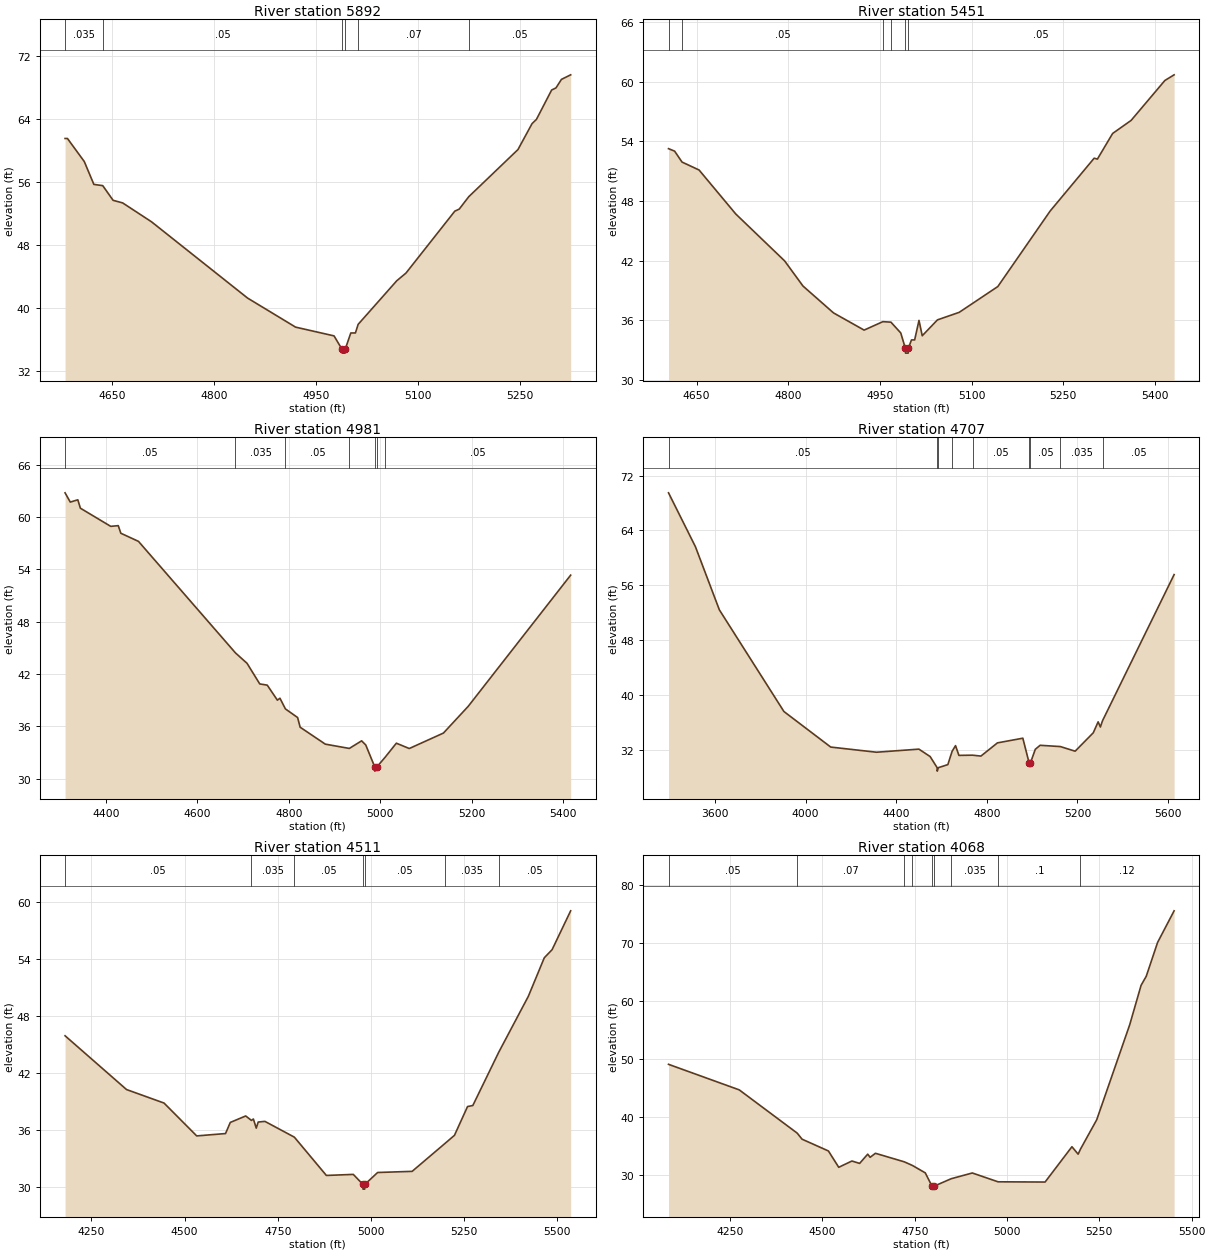
Type RM Length L Ch R = 1 ,5892    ,441,441,441
BEGIN DESCRIPTION:
TRIB 2-8-1 TO GUADALUPE RIVER 13.0
END DESCRIPTION:
XS GIS Cut Line= 3
        2598625.       13429125.        2598925.       13428825.
      2599124.99     13428575.01
#Sta/Elev= 30
  4580.5   61.47    4584   61.47  4608.8   58.54  4622.9   55.64    4636   55.48
  4651.2   53.62  4665.3   53.29  4707.8   50.89  4849.2   41.21  4919.9   37.52
  4976.5   36.41  4988.2   34.72  4988.6   34.22  4992.7   34.22    4993   34.72
  5001.2   36.78    5008   36.78    5012   37.87  5068.8    43.4  5082.4   44.38
  5154.4   52.25  5160.8    52.5  5174.9   54.08  5247.3   60.06  5268.1   63.36
  5274.5   63.89  5296.9   67.62  5303.3   67.89  5311.3   68.97  5324.9   69.55
#Mann= 6 ,-1 , 0
  4580.5    .035       0    4636     .05       0  4988.2     .05       0
    4993     .05       0    5012     .07       0  5174.9     .05       0
Bank Sta=4988.2,4993
XS Rating Curve= 0 ,0
Exp/Cntr=0.3,0.1

Type RM Length L Ch R = 1 ,5451    ,470,470,470
BEGIN DESCRIPTION:
TRIB 2-8-1 TO GUADALUPE RIVER 12.0
END DESCRIPTION:
XS GIS Cut Line= 3
        2598775.       13429175.        2599175.       13429175.
        2599575.       13429325.
#Sta/Elev= 30
  4604.2   53.27  4614.2   53.02  4626.3   51.92  4654.2   51.12  4714.2   46.69
  4794.2   41.96  4824.2   39.43  4874.2   36.72  4924.2   34.99  4954.9   35.84
  4968.1   35.79  4984.2    34.7  4991.6   33.17    4992   32.67  4996.3   32.67
  4996.7   33.17  5001.7      34  5006.9      34    5014   35.97  5019.3   34.42
  5044.2   36.02  5079.8   36.78    5143   39.38  5228.5   46.98  5300.6   52.31
  5305.9   52.22  5330.8    54.8  5361.1   56.12  5416.3   60.14  5431.4   60.71
#Mann= 6 ,-1 , 0
  4604.2    .035       0  4626.3     .05       0  4954.9    .035       0
  4968.1     .05       0  4991.6     .05       0  4996.7     .05       0
Bank Sta=4991.6,4996.7
XS Rating Curve= 0 ,0
Exp/Cntr=0.3,0.1

Type RM Length L Ch R = 1 ,4981    ,274,274,274
BEGIN DESCRIPTION:
TRIB 2-8-1 TO GUADALUPE RIVER 11.0
END DESCRIPTION:
XS GIS Cut Line= 3
       2598459.2     13429255.08        2599075.       13429575.
      2599475.05     13429474.99
#Sta/Elev= 30
  4310.6   62.76    4322    61.7  4338.5   61.96  4344.1      61  4410.5   58.92
    4427      59  4432.6   58.13  4471.2    57.2  4683.5   44.42  4708.8   43.23
  4736.6   40.87    4753   40.73  4775.2   39.01  4780.8   39.23  4792.7   38.01
  4819.4   37.02    4825   35.91  4880.1   33.97  4932.6   33.48  4959.5   34.35
  4968.6   33.87  4988.1   31.38  4988.5   30.88  4993.2   31.38  5010.6   32.45
  5035.5   34.08  5063.8   33.47  5138.5   35.24  5192.7    38.3  5416.9   53.33
#Mann= 7 ,-1 , 0
  4310.6     .05       0  4683.5    .035       0  4792.7     .05       0
  4932.6    .035       0  4988.1    .035       0  4993.2    .035       0
  5010.6     .05       0
Bank Sta=4988.1,4993.2
XS Rating Curve= 0 ,0
Exp/Cntr=0.3,0.1

Type RM Length L Ch R = 1 ,4707    ,196,196,196
BEGIN DESCRIPTION:
Mapping XS 669df807
END DESCRIPTION:
XS GIS Cut Line= 4
      2597591.14     13429602.67      2598152.16     13430050.29
      2598995.62     13429810.62      2599545.09      13429487.7
#Sta/Elev= 30
  3395.1   69.48  3513.9   61.64  3619.6   52.45  3904.6   37.66  4111.2   32.49
  4313.3   31.74  4500.4   32.19    4550   31.11    4581   29.49  4581.4   28.99
  4586.1   29.49  4628.2   29.94  4646.8   31.86  4662.1    32.7  4677.1   31.28
    4737   31.31  4774.2   31.18  4847.1    33.1  4959.2   33.78  4986.7   30.22
  4992.8   30.19  5014.3   32.17  5035.7   32.75  5125.2   32.56  5190.1   31.89
  5270.2   34.57  5291.6   36.16  5301.5   35.41  5311.1   36.33    5627   57.58
#Mann= 9 ,-1 , 0
  3395.1     .05       0    4581     .05       0  4586.1     .05       0
  4646.8    .035       0    4737     .05       0  4986.7     .05       0
  4992.8     .05       0  5125.2    .035       0  5311.1     .05       0
Bank Sta=4986.7,4992.8
XS Rating Curve= 0 ,0
Exp/Cntr=0.3,0.1

Type RM Length L Ch R = 1 ,4511    ,443,443,443
BEGIN DESCRIPTION:
TRIB 2-8-1 TO GUADALUPE RIVER 10.0
END DESCRIPTION:
XS GIS Cut Line= 3
        2598975.     13430675.01        2599175.       13429875.
      2599574.97     13429525.03
#Sta/Elev= 30
  4179.6   45.87  4344.5   40.21    4445   38.79  4532.7   35.33    4610   35.58
  4622.8   36.75  4664.1   37.43  4679.5   36.96  4684.7   37.11  4692.4   36.15
  4697.6   36.79  4715.6   36.86  4794.6    35.2  4880.5   31.17  4952.7   31.28
  4978.4   30.23  4978.8   29.73  4983.3   29.73  4983.7   30.23    5018   31.48
  5110.5    31.6  5197.5    34.5    5224   35.39  5259.1   38.42  5273.3   38.53
  5342.7   44.13  5422.3   50.03    5465   54.08  5485.9   54.93  5535.7   59.02
#Mann= 7 ,-1 , 0
  4179.6     .05       0  4679.5    .035       0  4794.6     .05       0
  4978.4     .05       0  4983.7     .05       0  5197.5    .035       0
  5342.7     .05       0
Bank Sta=4978.4,4983.7
XS Rating Curve= 0 ,0
Exp/Cntr=0.3,0.1

Type RM Length L Ch R = 1 ,4068    ,447,447,447
BEGIN DESCRIPTION:
TRIB 2-8-1 TO GUADALUPE RIVER 9.0
END DESCRIPTION:
XS GIS Cut Line= 3
      2598925.02     13430824.97        2599525.       13430125.
      2599924.97     13429925.01
#Sta/Elev= 30
  4083.4    49.1  4274.9    44.7  4431.9   37.25    4445   36.21  4516.4   34.18
  4544.3   31.37    4580   32.45  4600.9   32.04  4622.8   33.63  4629.4   33.09
  4643.7   33.78  4721.9   32.31    4744   31.68  4778.7   30.41  4796.9   28.11
  4797.3   27.61  4802.2   28.11  4848.8    29.4    4906   30.39  4975.8   28.87
  5103.1   28.83  5175.8   34.91  5192.6   33.63    5199    34.5  5242.9   39.55
  5332.3   55.92  5363.1   62.71  5377.1   64.27  5407.8   70.09  5452.5   75.53
#Mann= 9 ,-1 , 0
  4083.4     .05       0  4431.9     .07       0  4721.9     .05       0
    4744     .07       0  4796.9     .05       0  4802.2     .07       0
  4848.8    .035       0  4975.8      .1       0    5199     .12       0
Bank Sta=4796.9,4802.2
XS Rating Curve= 0 ,0
Exp/Cntr=0.3,0.1

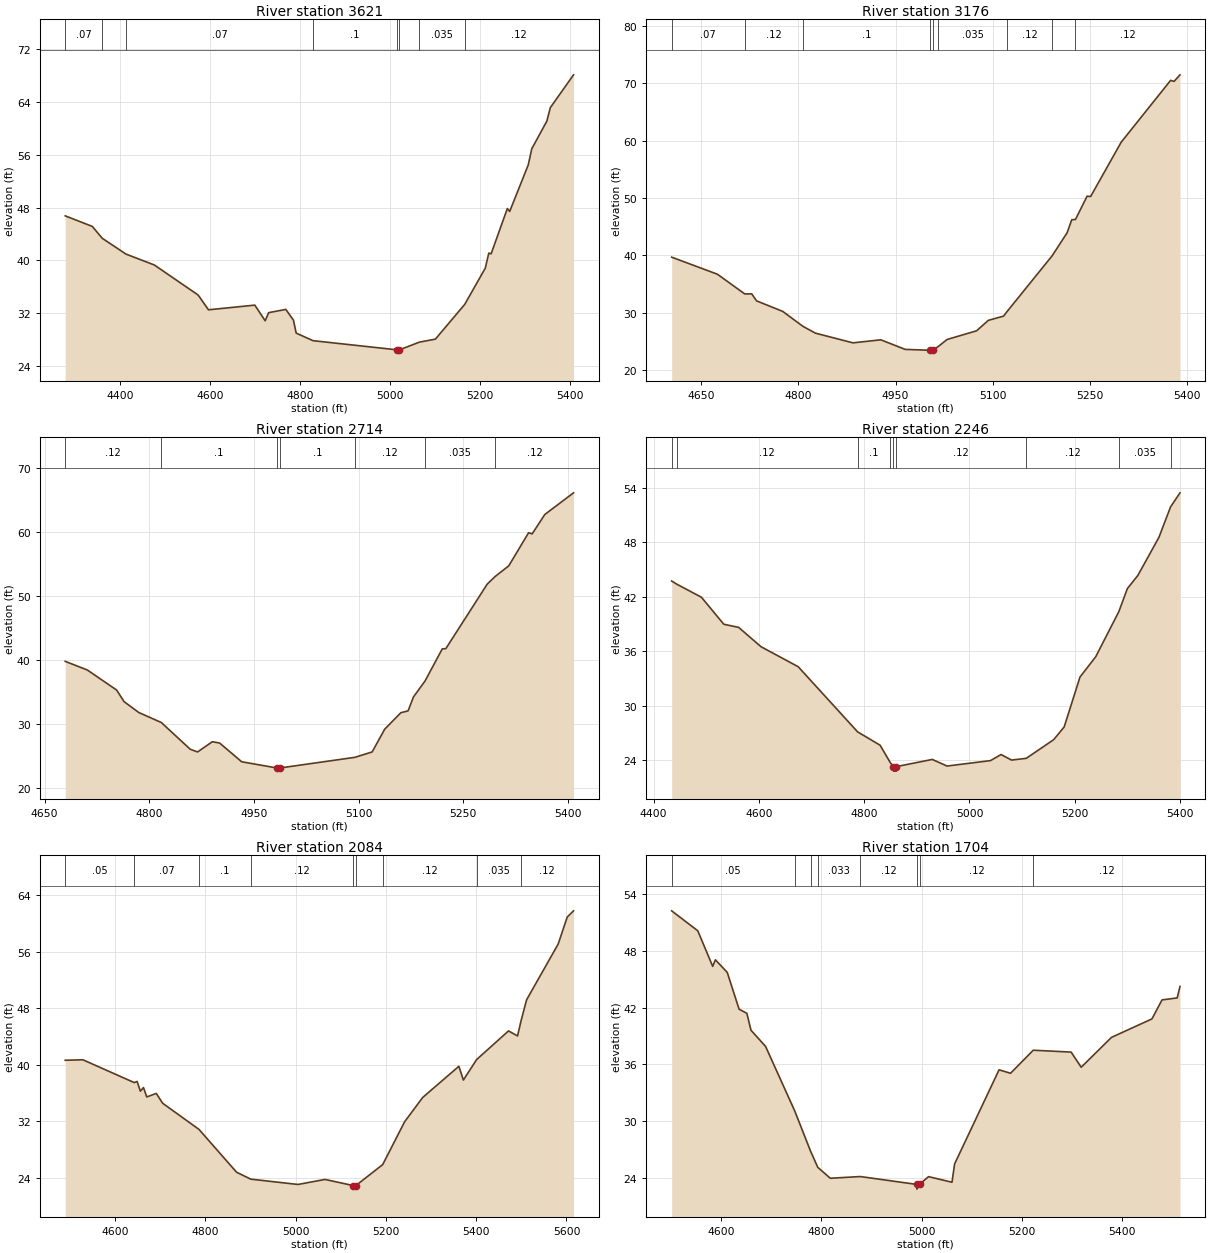
Type RM Length L Ch R = 1 ,3621    ,445,445,445
BEGIN DESCRIPTION:
TRIB 2-8-1 TO GUADALUPE RIVER 8.0
END DESCRIPTION:
XS GIS Cut Line= 3
      2599024.98     13430775.01        2599675.       13430475.
      2600074.98       13430575.
#Sta/Elev= 30
  4278.7   46.75  4338.8   45.15  4360.9   43.35  4413.6   40.95  4476.5    39.3
  4573.8   34.74  4596.7    32.5  4699.5   33.21  4722.5   30.84  4730.3   32.07
  4768.4   32.56  4785.3   30.93  4791.3   28.97  4828.6   27.82  5015.1   26.43
  5015.6   25.93  5020.5   26.43    5065    27.6  5100.3   28.05  5165.6   33.34
  5211.1   38.83  5218.8    41.1    5224   40.99    5260   47.86  5265.2   47.42
  5306.4   54.48  5314.2   56.92  5347.7   61.12  5355.4   63.16  5406.9   68.14
#Mann= 8 ,-1 , 0
  4278.7     .07       0  4360.9     .05       0  4413.6     .07       0
  4828.6      .1       0  5015.1     .05       0  5020.5      .1       0
    5065    .035       0  5165.6     .12       0
Bank Sta=5015.1,5020.5
XS Rating Curve= 0 ,0
Exp/Cntr=0.3,0.1

Type RM Length L Ch R = 1 ,3176    ,462,462,462
BEGIN DESCRIPTION:
TRIB 2-8-1 TO GUADALUPE RIVER 7.0
END DESCRIPTION:
XS GIS Cut Line= 3
      2599325.04       13430925.        2599725.       13430875.
      2600075.04     13431025.02
#Sta/Elev= 30
  4604.7    39.7  4675.2   36.73  4717.5   33.29  4728.1   33.31  4735.7   32.08
    4776   30.25  4807.1   27.65  4826.4   26.46  4884.3   24.77  4927.2    25.3
  4964.9   23.63  5002.6   23.48    5003   22.98    5008   23.48  5016.1   24.16
  5029.5   25.36  5074.9   26.87    5093   28.69  5116.6   29.43  5121.7   30.19
  5191.5   39.95  5214.5   43.95  5221.7   46.22  5227.4   46.27  5245.3   50.32
  5250.8   50.27  5297.9   59.73  5374.1    70.5  5379.5   70.33  5388.6   71.47
#Mann= 9 ,-1 , 0
  4604.7     .07       0  4717.5     .12       0  4807.1      .1       0
  5002.6     .05       0    5008      .1       0  5016.1    .035       0
  5121.7     .12       0  5191.5    .035       0  5227.4     .12       0
Bank Sta=5002.6,5008
XS Rating Curve= 0 ,0
Exp/Cntr=0.3,0.1

Type RM Length L Ch R = 1 ,2714    ,468,468,468
BEGIN DESCRIPTION:
TRIB 2-8-1 TO GUADALUPE RIVER 6.0
END DESCRIPTION:
XS GIS Cut Line= 3
      2599325.04     13431175.01        2599625.       13431275.
        2600025.       13431375.
#Sta/Elev= 30
  4679.6   39.81  4711.2   38.47  4753.3   35.34  4763.9   33.54    4785   31.84
  4817.3   30.28  4858.8   26.11  4869.3   25.69  4890.4   27.28  4900.9   27.08
  4932.5   24.16  4982.5    23.2  4982.9    22.7    4988    23.2  5094.7   24.85
  5119.5   25.69  5137.5   29.24  5160.7   31.81    5171   32.09  5178.7   34.26
  5195.3   36.75    5220   41.76  5225.1   41.79  5284.4   51.85  5295.9   53.05
  5315.3    54.7  5343.7   59.86  5348.8   59.68  5366.9    62.7  5408.1   66.08
#Mann= 7 ,-1 , 0
  4679.6     .12       0  4817.3      .1       0  4982.5     .05       0
    4988      .1       0  5094.7     .12       0  5195.3    .035       0
  5295.9     .12       0
Bank Sta=4982.5,4988
XS Rating Curve= 0 ,0
Exp/Cntr=0.3,0.1

Type RM Length L Ch R = 1 ,2246    ,162,162,162
BEGIN DESCRIPTION:
TRIB 2-8-1 TO GUADALUPE RIVER 5.0
END DESCRIPTION:
XS GIS Cut Line= 3
      2599125.02     13431275.02        2599525.       13431675.
      2599925.04       13431675.
#Sta/Elev= 30
  4434.3   43.74    4444   43.39  4490.8   41.95  4533.3   38.97  4561.6   38.62
    4604   36.49  4674.7   34.28  4787.6   27.09  4830.3   25.62  4849.7   23.69
  4855.7   23.26  4856.2   22.76  4860.9   22.76  4861.3   23.26  4929.3   24.05
  4957.5   23.32    5040   23.92    5060   24.59    5080   23.98  5107.9   24.17
    5160   26.23    5180   27.64    5210   33.14    5240   35.39  5283.8   40.36
    5300    42.9    5320   44.36    5360   48.56  5382.1   51.92    5400   53.47
#Mann= 9 ,-1 , 0
  4434.3     .07       0    4444     .12       0  4787.6      .1       0
  4849.7     .12       0  4855.7     .05       0  4861.3     .12       0
  5107.9     .12       0  5283.8    .035       0  5382.1     .12       0
Bank Sta=4855.7,4861.3
XS Rating Curve= 0 ,0
Exp/Cntr=0.3,0.1

Type RM Length L Ch R = 1 ,2084    ,380,380,380
BEGIN DESCRIPTION:
Mapping XS d05b025c
END DESCRIPTION:
XS GIS Cut Line= 4
      2599003.41     13431501.35      2599259.51     13431744.43
      2599558.99     13431835.57      2600019.04     13431839.91
#Sta/Elev= 30
  4489.4   40.65  4528.5   40.72  4642.4   37.49  4648.7   37.65  4655.9   36.28
  4662.8   36.79  4670.1   35.46  4691.2   35.96  4705.3   34.57  4785.8   30.87
  4869.1   24.81  4900.6   23.83    5005   23.08  5065.1   23.79  5127.7   22.92
  5128.1   22.42  5133.3   22.92  5192.8   25.89  5241.5   31.96  5281.5   35.39
  5361.6    39.8  5371.6   37.85  5400.9   40.75  5471.6    44.8  5491.6   44.09
  5499.2    46.2  5511.6    49.2  5581.6   57.09  5601.6   60.91  5615.6   61.79
#Mann= 9 ,-1 , 0
  4489.4     .05       0  4642.4     .07       0  4785.8      .1       0
  4900.6     .12       0  5127.7     .05       0  5133.3     .12       0
  5192.8     .12       0  5400.9    .035       0  5499.2     .12       0
Bank Sta=5127.7,5133.3
XS Rating Curve= 0 ,0
Exp/Cntr=0.3,0.1

Type RM Length L Ch R = 1 ,1704    ,309,309,309
BEGIN DESCRIPTION:
Mapping XS 10f83edf
END DESCRIPTION:
XS GIS Cut Line= 4
      2598857.19       13431897.      2599174.87      13432032.4
      2599406.64     13432097.51      2599830.59     13432050.69
#Sta/Elev= 30
  4502.2   52.25  4554.2   50.14  4583.9   46.38  4589.3   47.07  4612.9   45.74
  4636.5   41.85    4652   41.41  4660.2   39.62  4689.2   37.92  4747.5   31.07
    4779   26.82  4793.3   25.12  4818.2   23.97    4878   24.15  4990.2   23.32
  4990.7   22.82  4995.9   23.32  5013.9   24.14  5060.6   23.55  5065.8   25.48
  5154.4   35.44  5177.2   35.07  5222.5   37.51  5297.9   37.31    5318   35.71
  5378.4   38.87  5458.9   40.82    5479   42.83  5509.2   43.04  5514.8   44.25
#Mann= 8 ,-1 , 0
  4502.2     .05       0  4747.5     .07       0    4779      .1       0
  4793.3    .033       0    4878     .12       0  4990.2     .05       0
  4995.9     .12       0  5222.5     .12       0
Bank Sta=4990.2,4995.9
XS Rating Curve= 0 ,0
Exp/Cntr=0.3,0.1

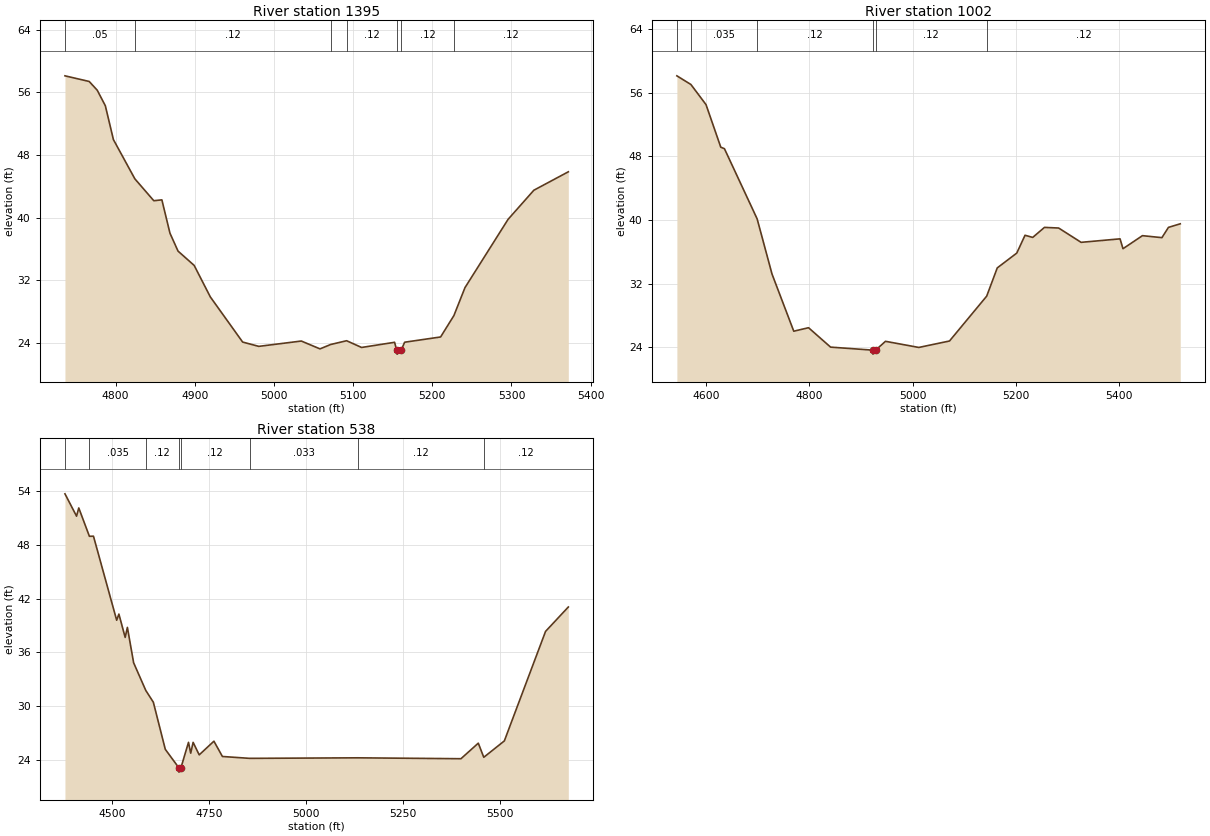
Type RM Length L Ch R = 1 ,1395    ,393,393,393
BEGIN DESCRIPTION:
TRIB 2-8-1 TO GUADALUPE RIVER 3.0
END DESCRIPTION:
XS GIS Cut Line= 3
      2598824.99       13432125.        2599075.       13432175.
      2599424.95     13432324.98
#Sta/Elev= 30
  4736.1   58.12  4766.7    57.4  4776.9   56.28  4787.1    54.3  4797.3   49.98
  4824.4   44.97  4848.3   42.18  4858.5   42.29  4868.7   38.04  4878.9   35.75
  4899.3   33.92  4919.7    29.9  4960.5   24.14  4980.9   23.59  5034.6   24.27
  5058.2   23.27  5071.7   23.83  5091.8   24.31  5110.7   23.45  5152.4   24.11
    5155    23.1  5155.5    22.6  5160.7    23.1  5165.1   24.12  5210.5   24.79
  5227.3   27.52  5241.3   31.09  5295.7    39.8  5328.3   43.52  5371.8   45.87
#Mann= 7 ,-1 , 0
  4736.1     .05       0  4824.4     .12       0  5071.7    .033       0
  5091.8     .12       0    5155     .05       0  5160.7     .12       0
  5227.3     .12       0
Bank Sta=5155,5160.7
XS Rating Curve= 0 ,0
Exp/Cntr=0.3,0.1

Type RM Length L Ch R = 1 ,1002    ,464,464,464
BEGIN DESCRIPTION:
TRIB 2-8-1 TO GUADALUPE RIVER 2.0
END DESCRIPTION:
XS GIS Cut Line= 3
      2598725.01       13432225.        2599075.       13432525.
      2599525.04     13432775.02
#Sta/Elev= 30
    4543   58.12  4570.2   57.03  4599.5    54.5  4628.1   49.15  4635.2   48.96
  4698.6   40.14  4727.4   33.21  4769.6   26.02  4798.2   26.46    4841   24.02
  4922.6   23.64  4923.1   23.14  4928.3   23.64  4947.4   24.75    5012   23.98
  5071.5   24.79  5143.6   30.43  5164.1   33.98  5201.9   35.84  5217.9   38.08
  5232.8   37.81  5255.6   39.07  5283.1   38.99  5326.6   37.19  5402.1   37.63
  5407.8   36.39  5445.5   38.03  5483.3   37.78  5495.9   39.07  5518.8   39.52
#Mann= 6 ,-1 , 0
    4543     .05       0  4570.2    .035       0  4698.6     .12       0
  4922.6     .05       0  4928.3     .12       0  5143.6     .12       0
Bank Sta=4922.6,4928.3
XS Rating Curve= 0 ,0
Exp/Cntr=0.3,0.1

Type RM Length L Ch R = 1 ,538     ,0,0,0
BEGIN DESCRIPTION:
TRIB 2-8-1 TO GUADALUPE RIVER 1.0
END DESCRIPTION:
XS GIS Cut Line= 3
      2598575.02     13432275.04        2598875.       13432825.
      2599475.02     13433125.01
#Sta/Elev= 30
  4378.6   53.73  4408.5   51.23  4414.2   52.15  4441.6   48.98  4452.1   48.99
  4511.9   39.59  4517.6   40.28  4533.8   37.67  4539.5   38.79  4555.6   34.83
    4587   31.73  4606.4   30.42  4637.2   25.15  4671.9    23.1  4672.3    22.6
  4677.6    23.1    4697   25.93  4702.7   24.72  4708.9   25.93  4724.6   24.53
  4762.5   26.06  4784.4   24.35  4854.4   24.14  5132.9    24.2  5399.2    24.1
  5443.9   25.84    5458   24.26    5511   26.09  5617.2   38.34  5675.9   41.07
#Mann= 8 ,-1 , 0
  4378.6     .05       0  4441.6    .035       0    4587     .12       0
  4671.9    .033       0  4677.6     .12       0  4854.4    .033       0
  5132.9     .12       0    5458     .12       0
Bank Sta=4671.9,4677.6
XS Rating Curve= 0 ,0
Exp/Cntr=0.3,0.1

Chan Stop Cuts=-1
Use User Specified Reach Order=0
Composite Channel Slope=5