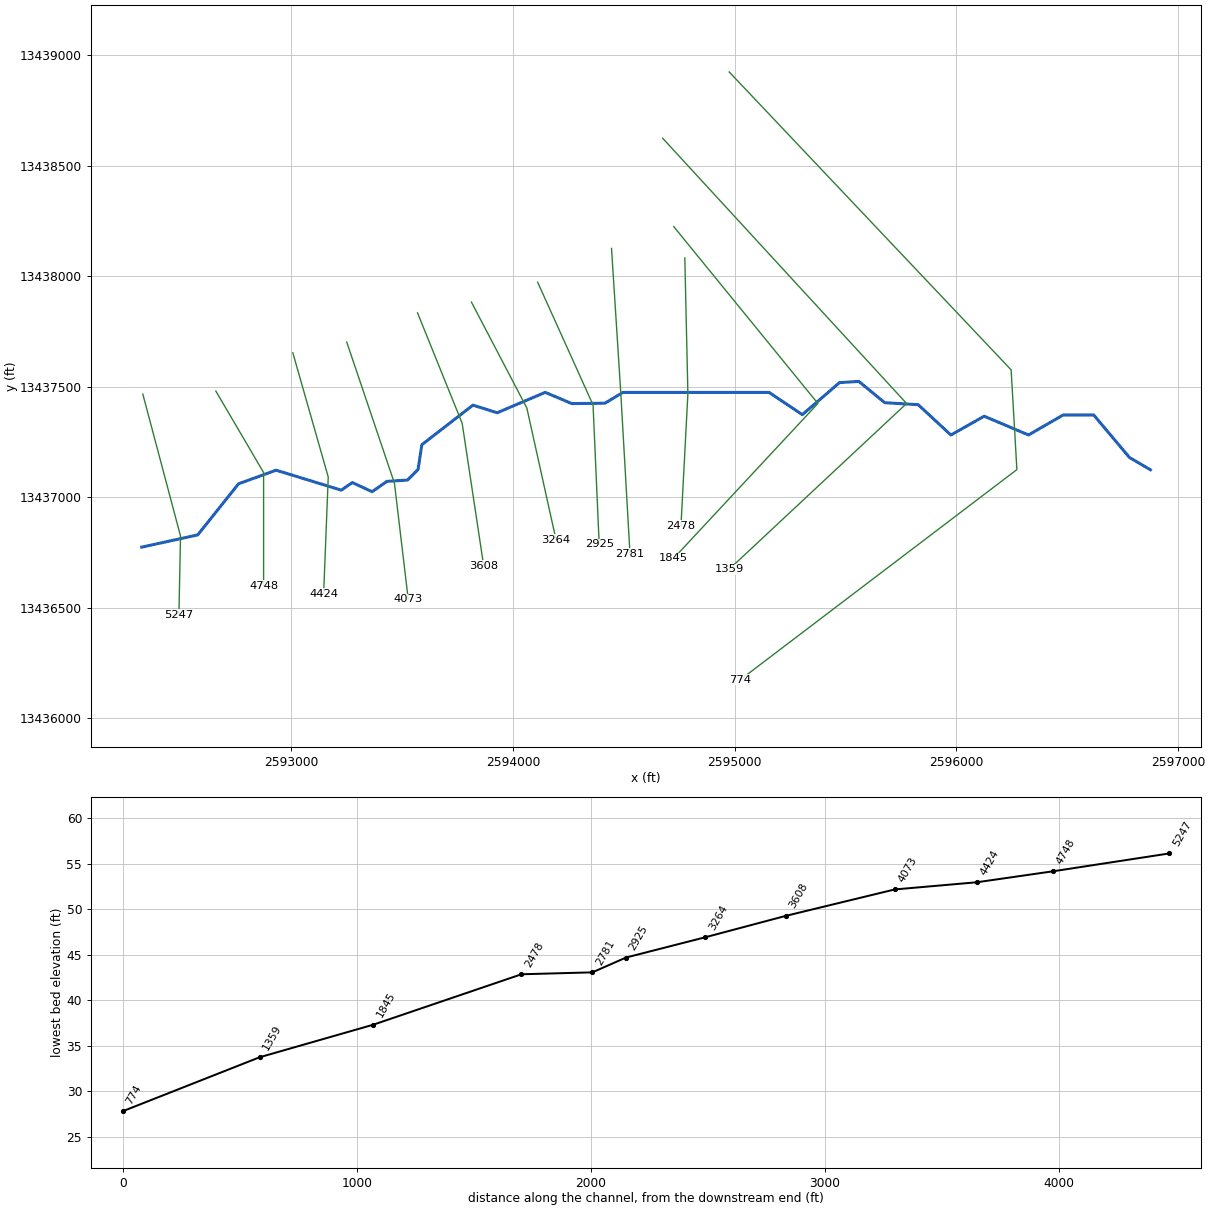
--- TRIB 2_9 TO GUADALUPE RIVER.prj (project) ---

Proj Title=TRIB 2_9 TO GUADALUPE RIVER Base Level Engineering
Current Plan=p01
Default Exp/Contr=0.3,0.1
English Units
Geom File=g01
Flow File=f01
Plan File=p01
Y Axis Title=Elevation
X Axis Title(PF)=Main Channel Distance
X Axis Title(XS)=Station
BEGIN DESCRIPTION:
TRIB 2_9 TO GUADALUPE RIVER
END DESCRIPTION:
DSS Export Rating Curves= 0
DSS Export Rating Curve Sorted= 0
DSS Export Volume Flow Curves= 0
DXF OffsetX= 0
DXF OffsetY= 0
DXF ScaleX= 1
DXF ScaleY= 10

--- TRIB 2_9 TO GUADALUPE RIVER.p01 (plan) ---

Plan Title=Multiple Run
Short Identifier=Multiple
Geom File=g01
Flow File=f01
Subcritical Flow
K Sum by GR= 0
Std Step Tol= 0.01
Critical Tol= 0.01
Num of Std Step Trials= 20
Max Error Tol= 0.3
Flow Tol Ratio= 0.001
Split Flow NTrial= 30
Split Flow Tol= 0.02
Split Flow Ratio= 0.02
Log Output Level= 0
Friction Slope Method= 1
Unsteady Friction Slope Method= 2
Unsteady Bridges Friction Slope Method= 1
Parabolic Critical Depth
Global Vel Dist=  1 , 1 , 1
Global Log Level= 0
CheckData=True
Encroach Param= -1, 0, 0, 0
BEGIN DESCRIPTION:
Multiple Run
END DESCRIPTION:

--- TRIB 2_9 TO GUADALUPE RIVER.f01 (steady flow) ---

Flow Title=Multiple
Number of Profiles=7
Profile Names=10-year,25-year,50-year,1pct_min,100-year,1pct_plu,500-year
River Rch & RM= TRIB 2_9 TO GUAD,Reach-1,5247
     583     899    1170     736    1469    2932    2288
River Rch & RM= TRIB 2_9 TO GUAD,Reach-1,4748
     803    1269    1680    1075    2146    4282    3458
Boundary for River Rch & Prof#=TRIB 2_9 TO GUAD,Reach-1,1
Up Type=0
Dn Type=3
Dn Slope=0.005
Boundary for River Rch & Prof#=TRIB 2_9 TO GUAD,Reach-1,2
Up Type=0
Dn Type=3
Dn Slope=0.005
Boundary for River Rch & Prof#=TRIB 2_9 TO GUAD,Reach-1,3
Up Type=0
Dn Type=3
Dn Slope=0.005
Boundary for River Rch & Prof#=TRIB 2_9 TO GUAD,Reach-1,4
Up Type=0
Dn Type=3
Dn Slope=0.005
Boundary for River Rch & Prof#=TRIB 2_9 TO GUAD,Reach-1,5
Up Type=0
Dn Type=3
Dn Slope=0.005
Boundary for River Rch & Prof#=TRIB 2_9 TO GUAD,Reach-1,6
Up Type=0
Dn Type=3
Dn Slope=0.005
Boundary for River Rch & Prof#=TRIB 2_9 TO GUAD,Reach-1,7
Up Type=0
Dn Type=3
Dn Slope=0.005

--- TRIB 2_9 TO GUADALUPE RIVER.g01 (geometry) ---

Geom Title=Existing Conditions
Program Version=4.10

River Reach=TRIB 2_9 TO GUAD,Reach-1
Reach XY= 30
        2592325.       13436775.      2592577.67     13436830.42
      2592761.69      13437061.6      2592931.12     13437123.18
       2593225.1     13437032.79      2593274.92     13437067.17
      2593364.29     13437025.81      2593430.97     13437072.62
      2593523.75     13437078.51      2593571.49     13437126.25
      2593588.39     13437238.33      2593818.96     13437417.48
      2593928.29      13437383.1      2594145.18     13437475.28
      2594264.81     13437424.55      2594414.49     13437426.22
      2594495.03     13437474.93      2595155.02     13437475.04
      2595304.84     13437374.53      2595472.57      13437519.6
      2595559.78     13437524.76      2595676.47     13437428.56
      2595827.45     13437419.53      2595974.91     13437282.29
      2596124.99     13437367.47      2596325.01     13437282.53
      2596480.93     13437372.77      2596619.14     13437372.95
      2596780.51     13437180.44        2596875.       13437125.

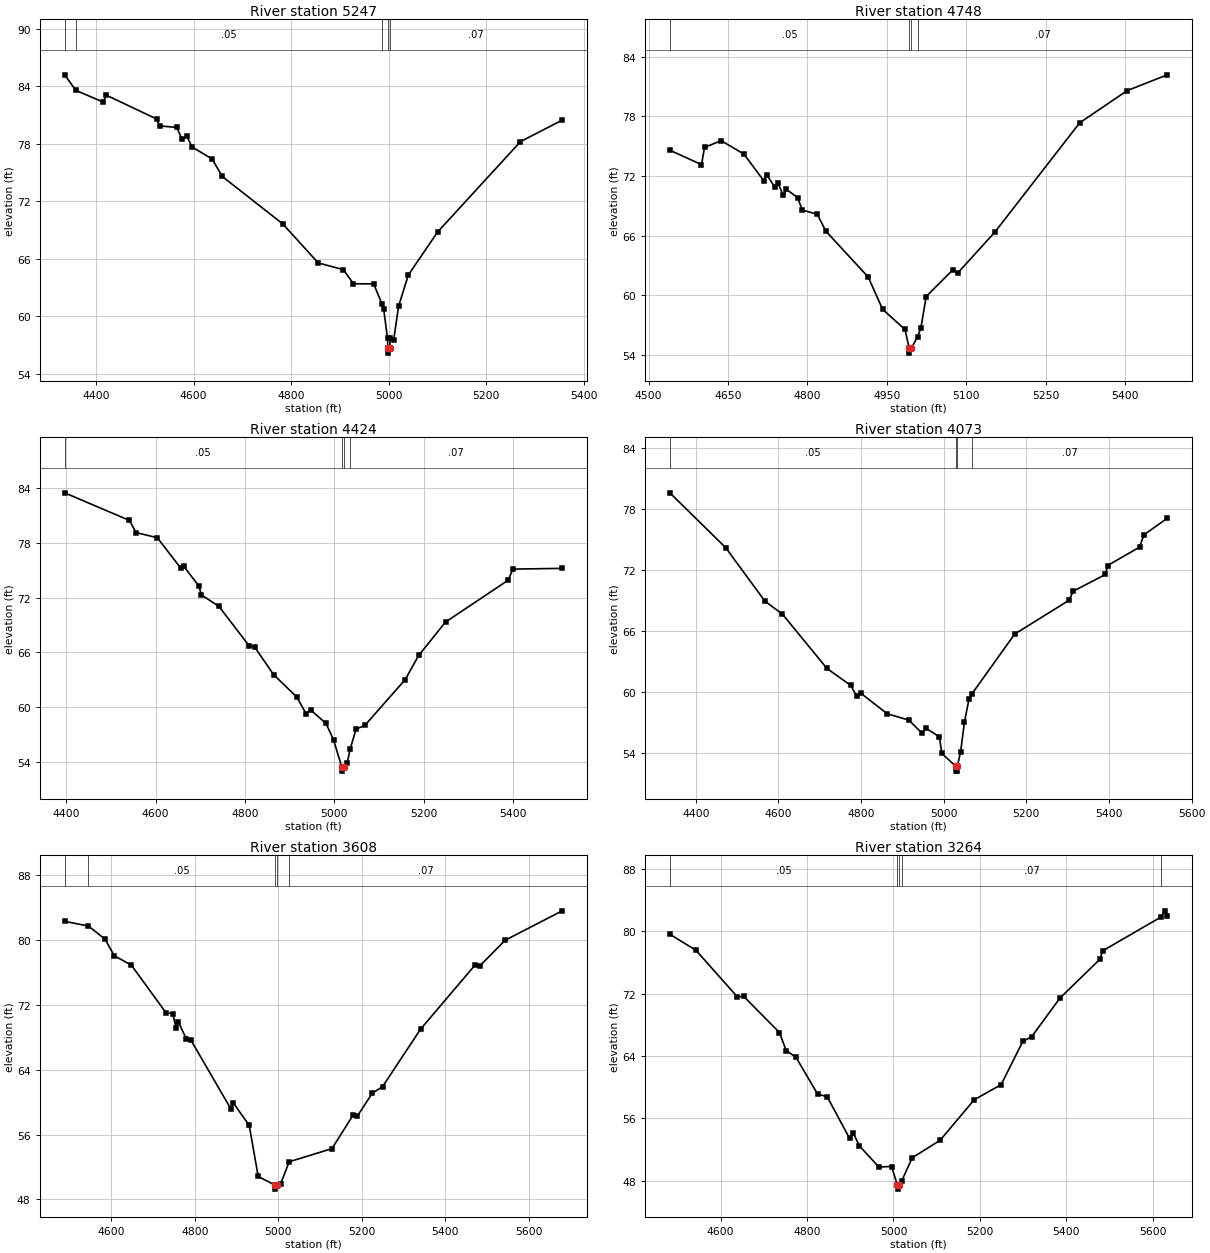
Type RM Length L Ch R = 1 ,5247    ,499,499,499
BEGIN DESCRIPTION:
TRIB 2-9 TO GUADALUPE RIVER 5.0
END DESCRIPTION:
XS GIS Cut Line= 3
      2592329.95     13437467.36      2592500.01     13436824.99
      2592492.72     13436469.57
#Sta/Elev= 30
  4335.5   85.18  4358.3   83.56  4414.7   82.33  4420.7   83.06  4524.1   80.57
  4530.2   79.85  4565.2   79.69  4575.9   78.48  4586.2   78.76  4596.6   77.65
  4637.9   76.39  4658.6   74.57  4782.8   69.61  4855.2   65.55  4906.9   64.84
  4927.6   63.37    4969   63.36    4986   61.27  4989.6    60.7  4997.4   57.67
  4997.9   56.63  4998.1   56.13  5002.1   56.63  5002.8   57.67    5010   57.48
    5020   61.01    5040   64.28    5100   68.77    5270   78.21  5355.5   80.45
#Mann= 5 ,-1 , 0
  4335.5    .035       0  4358.3     .05       0    4986     .07       0
  4997.9     .05       0  5002.1     .07       0
Bank Sta=4997.9,5002.1
XS Rating Curve= 0 ,0
Exp/Cntr=0.3,0.1

Type RM Length L Ch R = 1 ,4748    ,324,324,324
BEGIN DESCRIPTION:
Mapping XS 0032ea20
END DESCRIPTION:
XS GIS Cut Line= 3
      2592659.36     13437480.87      2592874.65     13437112.78
      2592874.65     13436599.41
#Sta/Elev= 30
  4540.3   74.59  4600.1   73.14  4605.9   74.88  4637.3   75.55  4680.3    74.2
  4717.5   71.53  4723.3   72.13  4738.9   70.85  4744.7   71.25  4754.6   70.04
  4760.4   70.66  4781.9    69.8  4790.4   68.57  4819.1   68.13  4834.8   66.45
    4915   61.82  4942.2   58.57  4984.5   56.54  4992.4   54.66  4992.7   54.16
  4996.7   54.66  5008.4   55.83  5014.5   56.68  5024.5   59.86  5074.5   62.52
  5084.5   62.25  5154.5   66.36  5314.5   77.35  5404.5    80.6  5480.1   82.18
#Mann= 4 ,-1 , 0
  4540.3     .05       0  4992.4     .05       0  4996.7     .05       0
  5008.4     .07       0
Bank Sta=4992.4,4996.7
XS Rating Curve= 0 ,0
Exp/Cntr=0.3,0.1

Type RM Length L Ch R = 1 ,4424    ,351,351,351
BEGIN DESCRIPTION:
Mapping XS 64fb5b17
END DESCRIPTION:
XS GIS Cut Line= 3
      2593006.61     13437654.42      2593166.32     13437091.95
      2593145.49     13436564.17
#Sta/Elev= 30
  4396.7    83.5  4541.6   80.47  4556.4   79.14    4604   78.57    4656   75.26
  4663.3   75.43  4697.2   73.25  4702.4    72.3  4741.5   71.05  4809.3   66.72
  4822.3   66.53  4863.9   63.56  4915.9   61.09  4936.7   59.27  4947.1   59.66
  4981.4   58.19  4998.4   56.36  5016.2   53.46  5016.5   52.96  5020.5   53.46
  5028.4   53.81  5035.4   55.39  5048.4   57.56  5068.4   57.99  5158.5   63.01
  5188.5   65.65  5248.6   69.32  5388.7   73.91  5399.4   75.13  5509.6   75.21
#Mann= 4 ,-1 , 0
  4396.7     .05       0  5016.2     .05       0  5020.5     .05       0
  5035.4     .07       0
Bank Sta=5016.2,5020.5
XS Rating Curve= 0 ,0
Exp/Cntr=0.3,0.1

Type RM Length L Ch R = 1 ,4073    ,465,465,465
BEGIN DESCRIPTION:
Mapping XS 48f75928
END DESCRIPTION:
XS GIS Cut Line= 3
      2593249.67     13437703.02      2593464.93     13437064.17
      2593527.22     13436538.19
#Sta/Elev= 30
  4337.4   79.58  4472.5   74.18  4567.5   68.91  4609.7   67.64  4717.4   62.29
  4775.1   60.61  4789.1   59.58  4799.6   59.84  4862.9   57.83  4915.7   57.19
  4947.3   55.92  4957.9   56.37  4989.6   55.55  4995.5   53.91  5028.6   52.67
  5028.9   52.17  5032.8   52.17  5033.1   52.67  5040.9   54.05  5050.3   57.03
  5061.1   59.23  5067.8   59.75  5171.8   65.67  5302.7   68.98  5313.8    69.9
  5391.5   71.54  5396.6   72.42  5473.9   74.23  5484.4   75.44  5541.2   77.08
#Mann= 4 ,-1 , 0
  4337.4     .05       0  5028.6     .05       0  5033.1     .05       0
  5067.8     .07       0
Bank Sta=5028.6,5033.1
XS Rating Curve= 0 ,0
Exp/Cntr=0.3,0.1

Type RM Length L Ch R = 1 ,3608    ,344,344,344
BEGIN DESCRIPTION:
Mapping XS 4ce85f21
END DESCRIPTION:
XS GIS Cut Line= 3
       2593569.1     13437835.01      2593770.49       13437335.
      2593867.64     13436689.61
#Sta/Elev= 30
    4488   82.33  4544.9   81.75    4585   80.12  4606.6   78.09  4647.7   76.93
  4730.9   71.03  4746.7   70.94  4755.1   69.18  4760.5    69.9  4779.1   67.84
    4790    67.7  4886.7   59.12  4892.1   59.91    4930   57.14  4951.6   50.83
  4991.8   49.77  4992.2   49.27  4996.4   49.77  5005.5   49.95  5025.8   52.65
  5128.2   54.27  5178.7   58.39  5188.8   58.27  5224.8   61.11  5249.5   61.93
  5340.5   69.02    5472      77  5482.1   76.81  5542.8   79.99  5679.7   83.63
#Mann= 5 ,-1 , 0
    4488    .035       0  4544.9     .05       0  4991.8     .05       0
  4996.4     .05       0  5025.8     .07       0
Bank Sta=4991.8,4996.4
XS Rating Curve= 0 ,0
Exp/Cntr=0.3,0.1

Type RM Length L Ch R = 1 ,3264    ,339,339,339
BEGIN DESCRIPTION:
Mapping XS c5fcbf69
END DESCRIPTION:
XS GIS Cut Line= 3
      2593812.16     13437883.61      2594062.15     13437404.45
       2594193.8     13436808.58
#Sta/Elev= 30
  4482.8   79.59  4543.1   77.55  4639.1   71.56  4653.6   71.63  4736.3      67
  4751.9   64.69  4774.5   63.83  4824.6    59.1  4846.7   58.77  4898.6   53.42
  4907.4   54.08  4921.1   52.47  4966.2   49.76  4995.7   49.82  5009.1   47.42
  5009.4   46.92  5013.7   47.42  5019.5   48.02  5043.2   50.93  5107.9   53.18
  5186.6   58.37  5249.1   60.32  5299.2   65.86  5319.7   66.47  5385.2   71.42
  5477.6    76.4  5483.5   77.46  5618.6    81.8  5626.9    82.6  5633.5   81.88
#Mann= 5 ,-1 , 0
  4482.8     .05       0  5009.1     .05       0  5013.7     .05       0
  5019.5     .07       0  5618.6     .05       0
Bank Sta=5009.1,5013.7
XS Rating Curve= 0 ,0
Exp/Cntr=0.3,0.1

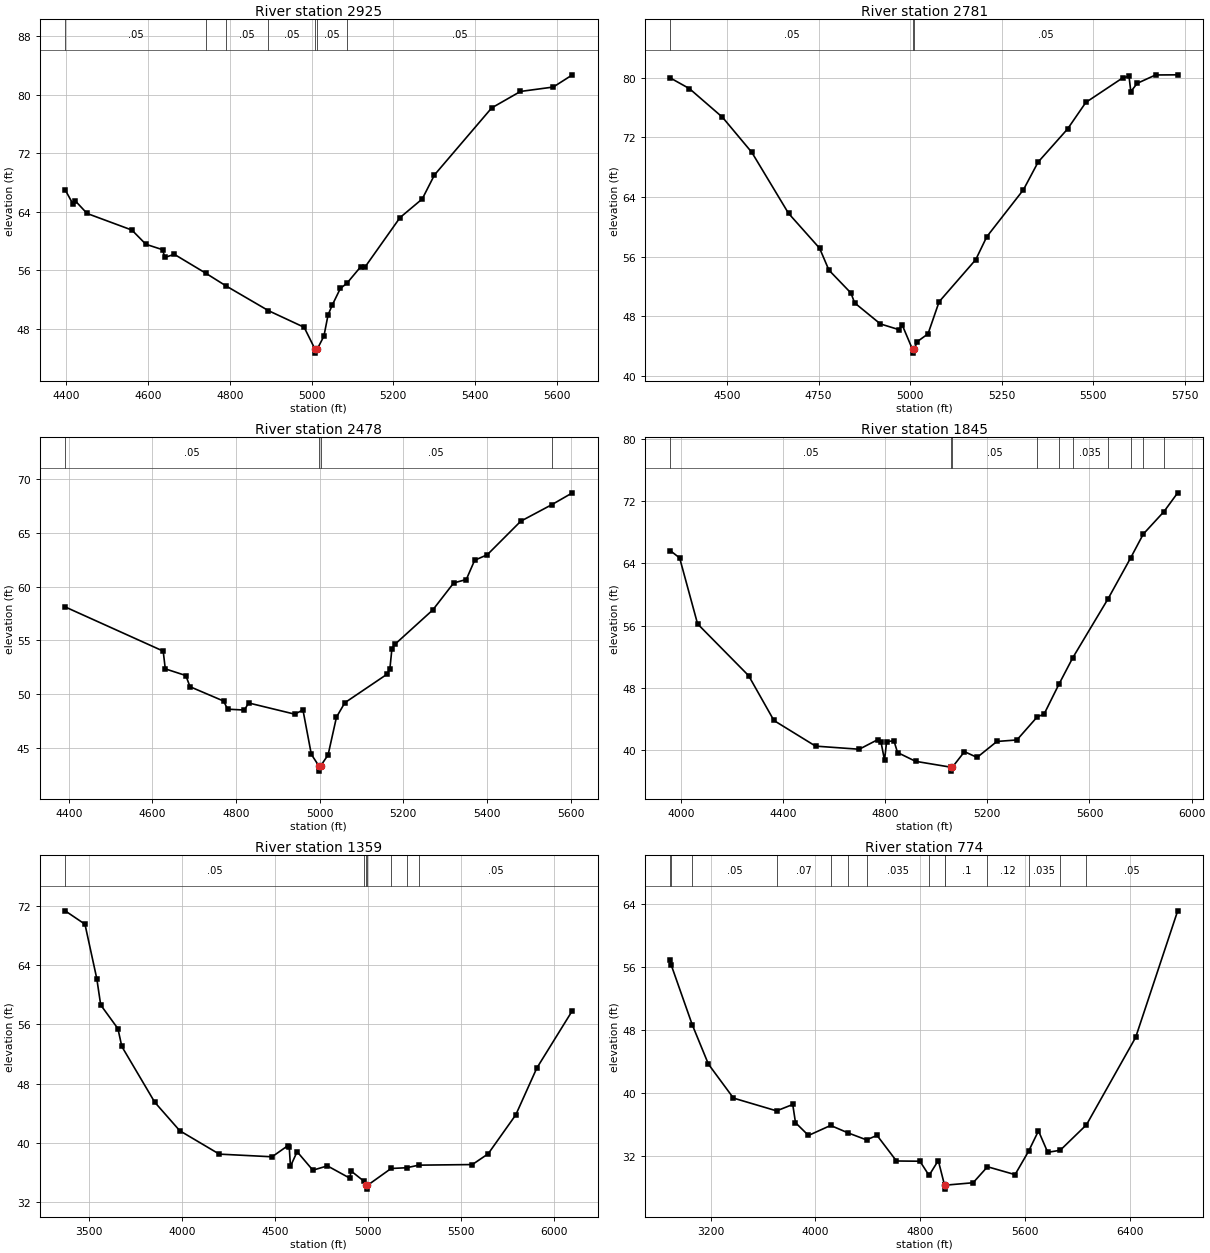
Type RM Length L Ch R = 1 ,2925    ,144,144,144
BEGIN DESCRIPTION:
Mapping XS 25483660
END DESCRIPTION:
XS GIS Cut Line= 3
      2594110.78     13437973.87      2594360.77     13437418.34
      2594388.46     13436788.23
#Sta/Elev= 30
  4397.8      67  4416.6   65.09  4422.1   65.52  4451.4   63.77    4561    61.5
  4595.1   59.56    4636   58.82  4641.4   57.76  4664.6   58.19  4741.2   55.62
  4791.1   53.87  4894.8   50.49    4982   48.22  5008.9   45.19  5009.2   44.69
  5013.5   45.19  5030.3   47.01  5040.4    49.9  5050.4   51.22  5070.4   53.52
  5086.4   54.23  5120.4    56.5  5130.4   56.42  5216.4   63.21  5270.6   65.75
  5300.6   69.04  5440.4   78.19  5510.8   80.44  5590.9   81.04  5637.7   82.71
#Mann= 7 ,-1 , 0
  4397.8     .05       0  4741.2     .07       0  4791.1     .05       0
  4894.8     .05       0  5008.9     .05       0  5013.5     .05       0
  5086.4     .05       0
Bank Sta=5008.9,5013.5
XS Rating Curve= 0 ,0
Exp/Cntr=0.3,0.1

Type RM Length L Ch R = 1 ,2781    ,303,303,303
BEGIN DESCRIPTION:
Mapping XS 8eeb706a
END DESCRIPTION:
XS GIS Cut Line= 3
       2594444.1     13438126.69      2594485.77     13437473.89
      2594527.43     13436744.71
#Sta/Elev= 30
  4345.8   79.96  4397.6   78.54  4487.8    74.7  4567.9   69.99  4668.1   61.81
  4752.9   57.13  4778.4   54.19  4838.5   51.12  4848.5    49.8  4918.7   46.98
  4968.8   46.22  4978.8   46.79  5006.5   43.56  5006.8   43.06  5011.2   43.56
  5018.9   44.58  5048.9   45.65  5079.1   49.95  5179.1    55.6  5209.2   58.67
  5309.3   64.98  5349.4   68.69  5429.6   73.12  5479.6   76.69  5579.8   79.97
  5597.4    80.2  5602.4   78.14  5619.8   79.25  5669.9   80.37  5730.3   80.39
#Mann= 3 ,-1 , 0
  4345.8     .05       0  5006.5     .05       0  5011.2     .05       0
Bank Sta=5006.5,5011.2
XS Rating Curve= 0 ,0
Exp/Cntr=0.3,0.1

Type RM Length L Ch R = 1 ,2478    ,633,633,633
BEGIN DESCRIPTION:
Mapping XS e5f2ed05
END DESCRIPTION:
XS GIS Cut Line= 3
      2594774.68     13438083.46      2594788.57     13437468.83
      2594757.32     13436871.63
#Sta/Elev= 30
  4391.4   58.12  4625.8   54.01  4630.8   52.36  4679.9   51.74  4689.9    50.7
    4770   49.37    4780   48.61    4820   48.53    4830   49.19    4940   48.15
    4960   48.53    4980   44.41  4997.7   43.35    4998   42.85  5002.4   43.35
    5020   44.35  5040.1   47.87  5060.1   49.21  5160.2   51.84  5167.7   52.32
  5172.7   54.25  5180.3   54.66  5270.4   57.84  5320.4   60.35  5350.5   60.67
  5370.5   62.46  5400.6   62.97  5480.7   66.09    5555   67.63  5604.2   68.73
#Mann= 4 ,-1 , 0
  4391.4     .05       0  4997.7     .05       0  5002.4     .05       0
    5555    .035       0
Bank Sta=4997.7,5002.4
XS Rating Curve= 0 ,0
Exp/Cntr=0.3,0.1

Type RM Length L Ch R = 1 ,1845    ,486,486,486
BEGIN DESCRIPTION:
TRIB 2-9 TO GUADALUPE RIVER 3.0
END DESCRIPTION:
XS GIS Cut Line= 3
      2594724.98     13438225.02        2595375.       13437425.
      2594724.97     13436724.97
#Sta/Elev= 30
  3959.3    65.6  3995.3   64.68  4065.6   56.21  4265.3   49.57  4364.5   43.81
  4527.5   40.52  4698.5   40.12  4770.3   41.34    4784   41.01  4797.6    38.7
  4805.5   41.07  4834.3   41.22  4848.4    39.7    4919   38.57  5058.3   37.81
  5058.7   37.31    5063   37.81  5110.6   39.81  5159.9   39.07  5237.6   41.12
  5315.8   41.31  5396.1    44.3  5421.8    44.6  5480.8   48.49  5534.3   51.85
  5672.5   59.42  5761.3   64.69  5810.6   67.74  5891.6   70.63  5945.4   73.04
#Mann= 10 ,-1 , 0
  3959.3     .05       0  5058.3     .05       0    5063     .05       0
  5396.1    .035       0  5480.8     .05       0  5534.3    .035       0
  5672.5     .05       0  5761.3    .035       0  5810.6     .05       0
  5891.6    .063       0
Bank Sta=5058.3,5063
XS Rating Curve= 0 ,0
Exp/Cntr=0.3,0.1

Type RM Length L Ch R = 1 ,1359    ,585,585,585
BEGIN DESCRIPTION:
TRIB 2-9 TO GUADALUPE RIVER 2.0
END DESCRIPTION:
XS GIS Cut Line= 3
      2594674.97     13438625.03        2595775.       13437425.
      2594975.01       13436675.
#Sta/Elev= 30
  3372.5   71.34  3478.9   69.53  3542.4   62.18  3563.4   58.62  3655.9   55.42
  3676.8   53.01  3853.8   45.47  3988.2   41.62  4200.4   38.46    4484    38.1
  4568.5    39.6  4575.9   39.48  4582.7   36.81  4618.4   38.79  4702.9   36.29
  4781.2   36.87  4901.5   35.21  4908.2   36.18  4977.7   34.79    4991   34.23
  4991.3   33.73  4995.7   34.23  5123.2   36.52  5206.5   36.62  5271.8   36.97
  5559.5   37.05  5644.4    38.5  5792.9   43.77  5905.8   50.09    6097   57.86
#Mann= 7 ,-1 , 0
  3372.5     .05       0  4977.7    .035       0    4991    .035       0
  4995.7    .035       0  5123.2     .05       0  5206.5    .035       0
  5271.8     .05       0
Bank Sta=4991,4995.7
XS Rating Curve= 0 ,0
Exp/Cntr=0.3,0.1

Type RM Length L Ch R = 1 ,774     ,0,0,0
BEGIN DESCRIPTION:
TRIB 2-9 TO GUADALUPE RIVER 1.0
END DESCRIPTION:
XS GIS Cut Line= 4
      2594974.99     13438925.02      2596246.56     13437577.23
       2596272.6     13437125.84      2595025.02     13436175.01
#Sta/Elev= 30
  2893.4   56.81  2899.1   56.25  3059.6   48.67  3183.3   43.66  3374.6   39.35
  3704.1   37.73  3827.4   38.54  3848.4   36.23  3947.5   34.61  4116.8   35.88
    4249   34.94  4390.7   34.05    4471   34.62  4619.5   31.37  4798.7   31.34
  4868.3   29.54  4938.9   31.43  4986.6    28.3  4986.9    27.8  4991.4    28.3
  5204.9   28.61  5314.5   30.64  5525.1   29.64  5627.9   32.59  5703.9   35.19
  5774.6   32.47  5869.9   32.73  6070.3   35.96    6446   47.05  6767.1   63.11
#Mann= 14 ,-1 , 0
  2893.4     .05       0  2899.1    .035       0  3059.6     .05       0
  3704.1     .07       0  4116.8    .035       0    4249     .12       0
  4390.7    .035       0  4868.3      .1       0  4986.6     .05       0
  4991.4      .1       0  5314.5     .12       0  5627.9    .035       0
  5869.9     .07       0  6070.3     .05       0
Bank Sta=4986.6,4991.4
XS Rating Curve= 0 ,0
Exp/Cntr=0.3,0.1

Chan Stop Cuts=-1
Use User Specified Reach Order=0
Composite Channel Slope=5