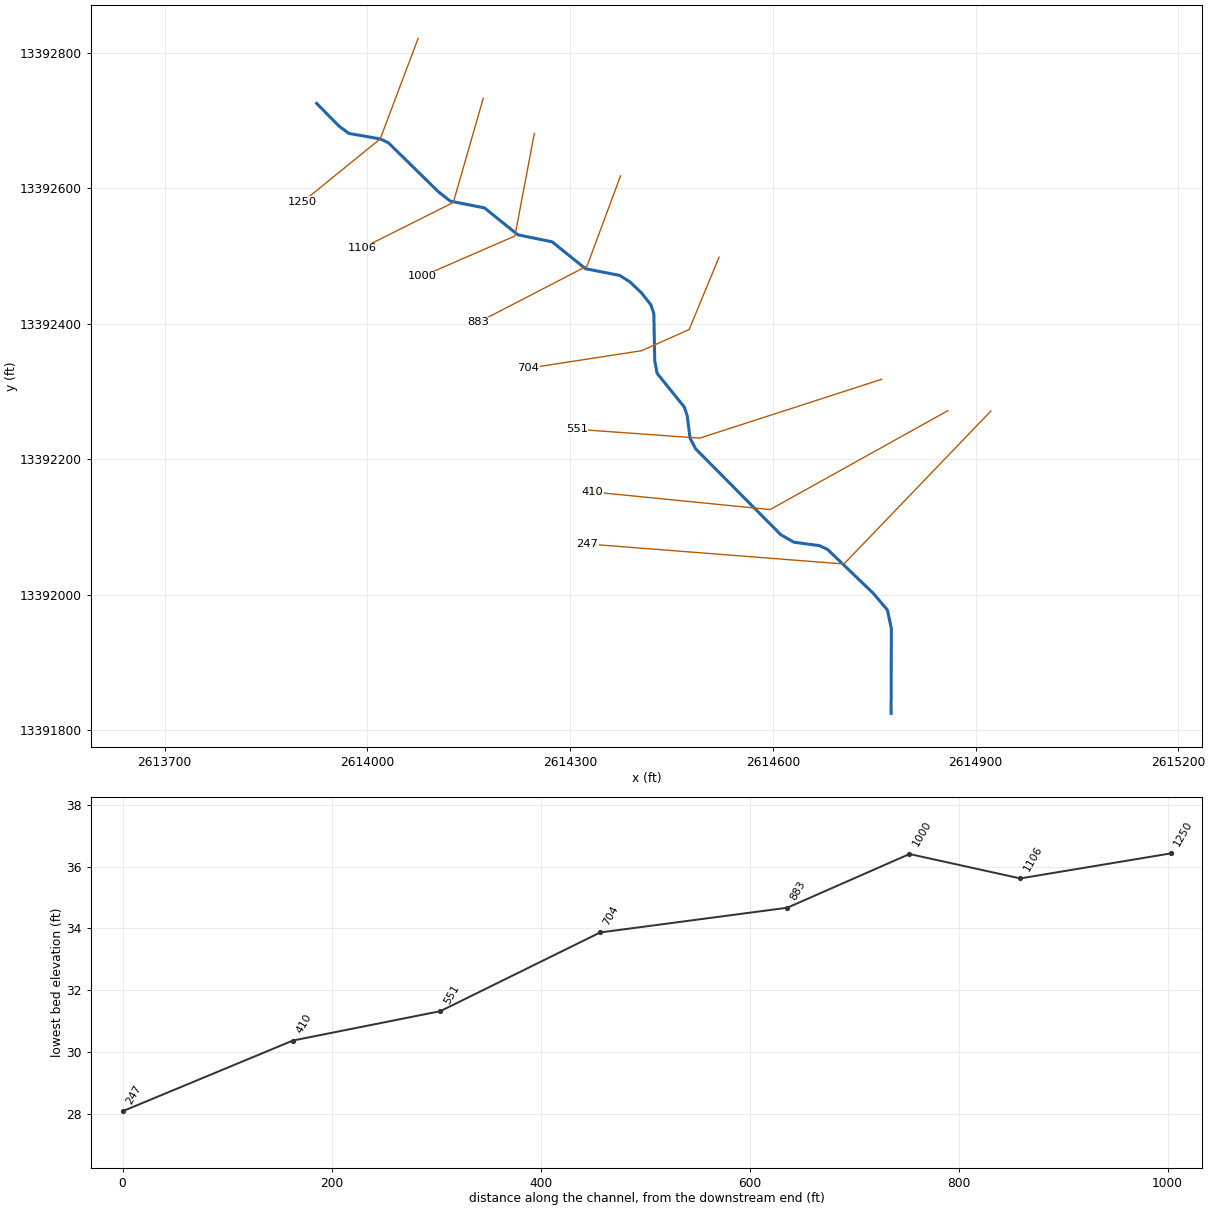
--- TRIB 4 TO KUY CREEK.prj (project) ---

Proj Title=TRIB 4 TO KUY CREEK Base Level Engineering
Current Plan=p01
Default Exp/Contr=0.3,0.1
English Units
Geom File=g01
Flow File=f01
Plan File=p01
BEGIN DESCRIPTION:
TRIB 4 TO KUY CREEK
END DESCRIPTION:

--- TRIB 4 TO KUY CREEK.p01 (plan) ---

Plan Title=Multiple Run
Short Identifier=Multiple
Geom File=g01
Flow File=f01
Subcritical Flow
K Sum by GR= 0
Std Step Tol= 0.01
Critical Tol= 0.01
Num of Std Step Trials= 20
Max Error Tol= 0.3
Flow Tol Ratio= 0.001
Split Flow NTrial= 30
Split Flow Tol= 0.02
Split Flow Ratio= 0.02
Log Output Level= 0
Friction Slope Method= 1
Unsteady Friction Slope Method= 2
Unsteady Bridges Friction Slope Method= 1
Parabolic Critical Depth
Global Vel Dist=  1 , 1 , 1
Global Log Level= 0
CheckData=True
Encroach Param= -1, 0, 0, 0
BEGIN DESCRIPTION:
Multiple Run
END DESCRIPTION:

--- TRIB 4 TO KUY CREEK.f01 (steady flow) ---

Flow Title=Multiple
Number of Profiles=7
Profile Names=10-year,25-year,50-year,1pct_min,100-year,1pct_plu,500-year
River Rch & RM= TRIB 4 TO KUY CR,Reach-1,1250
     593     920    1204     762    1521    3035    2399
Boundary for River Rch & Prof#=TRIB 4 TO KUY CR,Reach-1,1
Up Type=0
Dn Type=3
Dn Slope=0.005
Boundary for River Rch & Prof#=TRIB 4 TO KUY CR,Reach-1,2
Up Type=0
Dn Type=3
Dn Slope=0.005
Boundary for River Rch & Prof#=TRIB 4 TO KUY CR,Reach-1,3
Up Type=0
Dn Type=3
Dn Slope=0.005
Boundary for River Rch & Prof#=TRIB 4 TO KUY CR,Reach-1,4
Up Type=0
Dn Type=3
Dn Slope=0.005
Boundary for River Rch & Prof#=TRIB 4 TO KUY CR,Reach-1,5
Up Type=0
Dn Type=3
Dn Slope=0.005
Boundary for River Rch & Prof#=TRIB 4 TO KUY CR,Reach-1,6
Up Type=0
Dn Type=3
Dn Slope=0.005
Boundary for River Rch & Prof#=TRIB 4 TO KUY CR,Reach-1,7
Up Type=0
Dn Type=3
Dn Slope=0.005

--- TRIB 4 TO KUY CREEK.g01 (geometry) ---

Geom Title=Existing Conditions

River Reach=TRIB 4 TO KUY CR,Reach-1
Reach XY= 30
      2613925.00     13392725.00      2613958.08     13392691.42
      2613972.65     13392680.70      2614019.03     13392672.65
      2614031.08     13392666.93      2614104.93     13392594.82
      2614122.71     13392580.85      2614173.26     13392570.81
      2614222.80     13392531.08      2614273.28     13392520.84
      2614322.84     13392481.12      2614373.61     13392471.15
      2614388.63     13392461.55      2614405.54     13392445.54
      2614419.58     13392427.68      2614423.90     13392414.67
      2614425.24     13392345.11      2614428.83     13392326.59
      2614468.86     13392277.17      2614473.28     13392264.29
      2614477.50     13392231.03      2614485.76     13392215.32
      2614611.79     13392088.63      2614631.05     13392077.54
      2614668.96     13392072.47      2614681.07     13392066.85
      2614748.86     13392001.93      2614769.58     13391977.48
      2614775.38     13391950.16      2614775.00     13391825.00

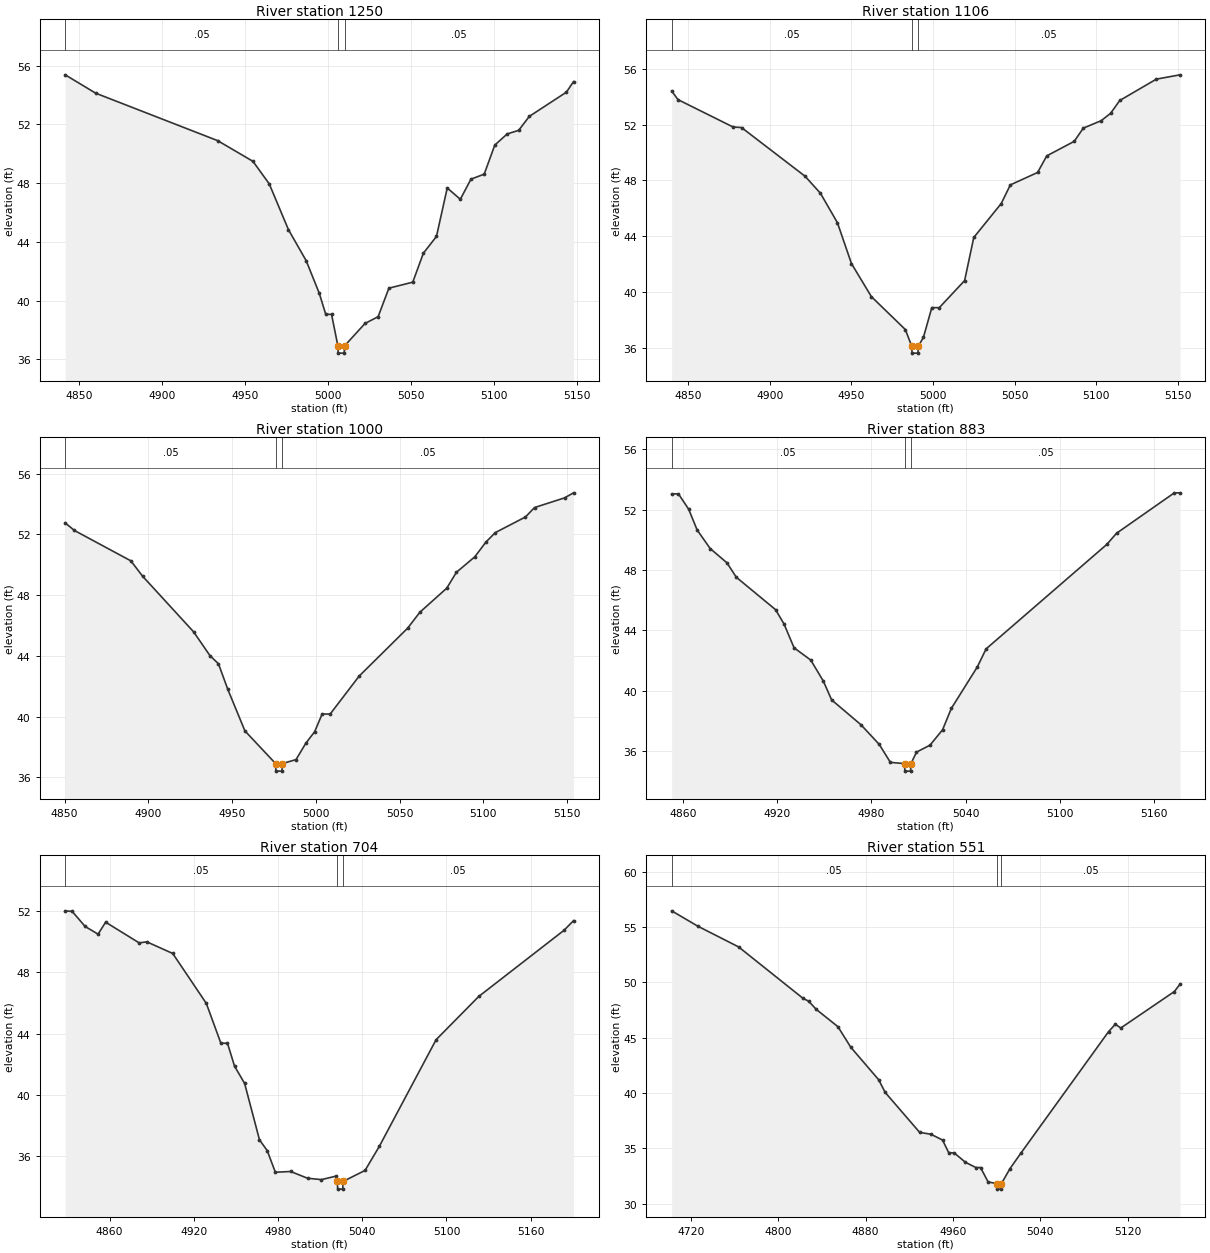
Type RM Length L Ch R = 1,1250,144,144,144
BEGIN DESCRIPTION:
TRIB 4 TO KUY CREEK 2.0
END DESCRIPTION:
XS GIS Cut Line= 3
      2614075.09     13392821.02      2614019.03     13392672.65
      2613903.94     13392579.44
#Sta/Elev= 30
  4841.4   55.37  4859.8   54.12  4933.4   50.89  4954.7   49.48  4964.5   47.95
  4976.1   44.83  4986.8   42.72  4994.7   40.50  4998.6   39.07  5002.1   39.07
  5005.9   36.93  5006.1   36.43  5009.7   36.43  5010.0   36.93  5022.3   38.45
  5030.2   38.91  5036.7   40.85  5051.1   41.26  5057.5   43.23  5065.4   44.37
  5071.9   47.67  5079.8   46.90  5086.2   48.27  5094.2   48.61  5100.6   50.59
  5108.1   51.35  5115.0   51.59  5121.4   52.54  5143.8   54.19  5148.1   54.91
#Mann=3,-1,0
  4841.4    0.05       0  5005.9    0.05       0  5010.0    0.05       0
Bank Sta=5005.9,5010
Exp/Cntr=0.3,0.1

Type RM Length L Ch R = 1,1106,106,106,106
BEGIN DESCRIPTION:
Mapping XS fd0436b6
END DESCRIPTION:
XS GIS Cut Line= 3
      2614171.45     13392732.50      2614127.18     13392578.86
      2613991.76     13392511.15
#Sta/Elev= 30
  4840.0   54.41  4843.9   53.79  4877.6   51.83  4882.8   51.79  4921.7   48.30
  4931.1   47.08  4941.5   44.97  4950.1   42.04  4962.3   39.67  4983.1   37.31
  4987.0   36.12  4987.2   35.62  4990.8   35.62  4991.1   36.12  4994.2   36.76
  4999.3   38.88  5003.9   38.88  5019.4   40.82  5025.0   43.91  5041.8   46.34
  5047.4   47.68  5064.1   48.57  5069.7   49.76  5086.5   50.80  5092.1   51.75
  5103.0   52.28  5108.8   52.81  5114.4   53.73  5136.8   55.26  5151.3   55.57
#Mann=3,-1,0
  4840.0    0.05       0  4987.0    0.05       0  4991.1    0.05       0
Bank Sta=4987,4991.1
Exp/Cntr=0.3,0.1

Type RM Length L Ch R = 1,1000,117,117,117
BEGIN DESCRIPTION:
Mapping XS a7edad1f
END DESCRIPTION:
XS GIS Cut Line= 3
      2614246.97     13392680.39      2614218.33     13392529.38
      2614080.91     13392469.75
#Sta/Elev= 30
  4850.4   52.76  4855.9   52.26  4889.6   50.26  4896.6   49.25  4927.1   45.58
  4936.8   44.02  4941.9   43.48  4947.5   41.79  4957.7   39.06  4976.0   36.91
  4976.2   36.41  4979.8   36.41  4980.1   36.91  4988.2   37.17  4994.2   38.27
  4999.3   39.00  5003.8   40.17  5008.6   40.17  5025.9   42.67  5054.8   45.82
  5062.2   46.88  5078.2   48.46  5084.0   49.51  5094.9   50.52  5101.7   51.51
  5107.2   52.12  5125.2   53.15  5130.6   53.77  5148.6   54.41  5153.9   54.74
#Mann=3,-1,0
  4850.4    0.05       0  4976.0    0.05       0  4980.1    0.05       0
Bank Sta=4976,4980.1
Exp/Cntr=0.3,0.1

Type RM Length L Ch R = 1,883,179,179,179
BEGIN DESCRIPTION:
Mapping XS 6bfa0f6b
END DESCRIPTION:
XS GIS Cut Line= 3
      2614374.59     13392617.96      2614325.10     13392485.11
      2614163.60     13392401.76
#Sta/Elev= 30
  4852.9   53.04  4857.2   53.04  4863.7   52.03  4869.1   50.65  4877.4   49.42
  4888.1   48.47  4894.0   47.52  4919.0   45.37  4924.4   44.42  4930.8   42.84
  4941.4   42.03  4949.4   40.64  4954.7   39.39  4973.4   37.74  4985.0   36.44
  4992.1   35.25  5001.1   35.17  5001.3   34.67  5004.9   34.67  5005.2   35.17
  5008.7   35.93  5017.3   36.39  5025.3   37.41  5030.9   38.83  5047.4   41.57
  5053.0   42.77  5129.8   49.69  5136.0   50.43  5172.8   53.11  5176.4   53.11
#Mann=3,-1,0
  4852.9    0.05       0  5001.1    0.05       0  5005.2    0.05       0
Bank Sta=5001.1,5005.2
Exp/Cntr=0.3,0.1

Type RM Length L Ch R = 1,704,153,153,153
BEGIN DESCRIPTION:
Mapping XS f8988d44
END DESCRIPTION:
XS GIS Cut Line= 4
      2614520.42     13392498.15      2614476.14     13392391.36
      2614405.83     13392360.11      2614238.25     13392334.33
#Sta/Elev= 30
  4828.4   52.01  4833.4   51.97  4842.6   50.99  4851.8   50.49  4857.2   51.27
  4881.1   49.92  4886.5   49.99  4905.0   49.23  4928.9   45.98  4939.3   43.38
  4944.0   43.38  4949.0   41.89  4956.2   40.76  4966.8   37.08  4972.3   36.38
  4978.1   34.97  4989.0   35.02  5001.0   34.58  5010.9   34.49  5021.0   34.71
  5022.2   34.37  5022.5   33.87  5026.1   33.87  5026.3   34.37  5042.0   35.09
  5052.1   36.65  5092.6   43.61  5123.0   46.43  5183.7   50.74  5190.5   51.37
#Mann=3,-1,0
  4828.4    0.05       0  5022.2    0.05       0  5026.3    0.05       0
Bank Sta=5022.2,5026.3
Exp/Cntr=0.3,0.1

Type RM Length L Ch R = 1,551,141,141,141
BEGIN DESCRIPTION:
Mapping XS 5aea598f
END DESCRIPTION:
XS GIS Cut Line= 3
      2614761.05     13392317.95      2614491.91     13392231.13
      2614309.77     13392244.14
#Sta/Elev= 30
  4702.5   56.45  4726.5   55.06  4763.8   53.19  4822.6   48.56  4827.9   48.29
  4834.9   47.55  4854.7   45.99  4866.5   44.13  4892.0   41.20  4898.0   40.05
  4929.5   36.45  4940.0   36.27  4950.5   35.75  4956.1   34.62  4961.3   34.58
  4971.5   33.74  4981.0   33.27  4985.3   33.27  4992.2   31.97  5000.2   31.82
  5000.5   31.32  5004.1   31.32  5004.4   31.82  5012.3   33.18  5022.3   34.58
  5102.5   45.54  5108.7   46.21  5113.7   45.87  5162.7   49.16  5167.9   49.83
#Mann=3,-1,0
  4702.5    0.05       0  5000.2    0.05       0  5004.4    0.05       0
Bank Sta=5000.2,5004.4
Exp/Cntr=0.3,0.1

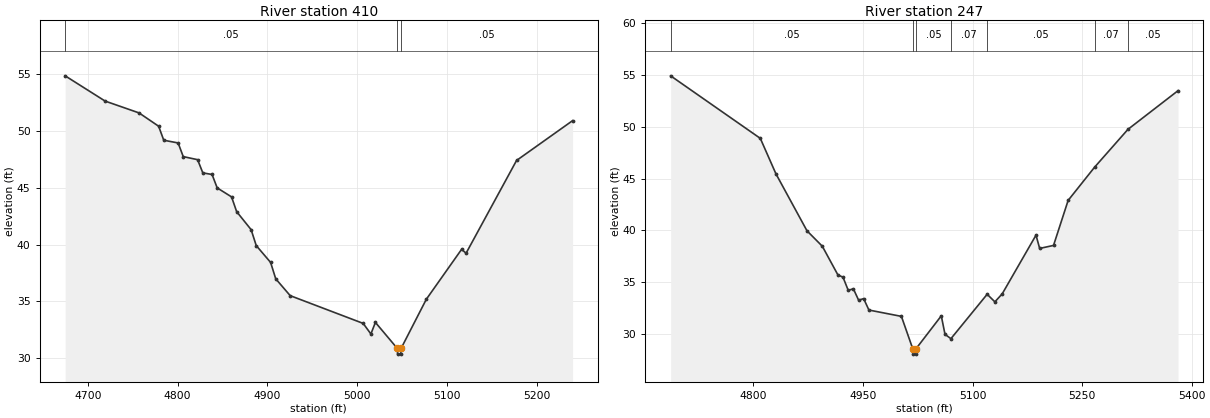
Type RM Length L Ch R = 1,410,163,163,163
BEGIN DESCRIPTION:
Mapping XS 0e51922c
END DESCRIPTION:
XS GIS Cut Line= 3
      2614858.97     13392271.58      2614595.93     13392125.74
      2614332.89     13392151.78
#Sta/Elev= 30
  4674.7   54.83  4719.2   52.61  4757.0   51.57  4778.8   50.40  4784.5   49.17
  4800.5   48.93  4806.2   47.73  4822.2   47.46  4828.0   46.30  4838.3   46.16
  4844.0   44.98  4860.0   44.19  4865.7   42.89  4881.8   41.31  4887.5   39.91
  4903.5   38.43  4909.2   36.99  4925.3   35.51  5006.6   33.07  5015.2   32.14
  5020.2   33.16  5044.6   30.87  5044.9   30.37  5048.5   30.37  5048.8   30.87
  5076.9   35.19  5116.2   39.58  5121.2   39.24  5177.4   47.39  5239.8   50.89
#Mann=3,-1,0
  4674.7    0.05       0  5044.6    0.05       0  5048.8    0.05       0
Bank Sta=5044.6,5048.8
Exp/Cntr=0.3,0.1

Type RM Length L Ch R = 1,247,0,0,0
BEGIN DESCRIPTION:
TRIB 4 TO KUY CREEK 1.0
END DESCRIPTION:
XS GIS Cut Line= 3
      2614922.66     13392271.13      2614705.24     13392045.42
      2614324.99     13392075.00
#Sta/Elev= 30
  4686.6   54.91  4809.4   48.88  4830.8   45.46  4873.3   39.97  4894.3   38.48
  4915.7   35.71  4922.6   35.50  4929.8   34.23  4936.8   34.38  4944.0   33.28
  4950.9   33.43  4958.1   32.33  5002.6   31.72  5018.2   28.58  5018.5   28.08
  5022.1   28.08  5022.4   28.58  5057.2   31.77  5062.3   29.99  5070.4   29.57
  5120.0   33.85  5130.6   33.12  5140.7   33.90  5186.9   39.55  5191.9   38.27
  5210.9   38.56  5230.9   42.90  5267.1   46.10  5312.8   49.75  5381.4   53.48
#Mann=7,-1,0
  4686.6    0.05       0  5018.2    0.05       0  5022.4    0.05       0
  5070.4    0.07       0  5120.0    0.05       0  5267.1    0.07       0
  5312.8    0.05       0
Bank Sta=5018.2,5022.4
Exp/Cntr=0.3,0.1

Chan Stop Cuts=-1