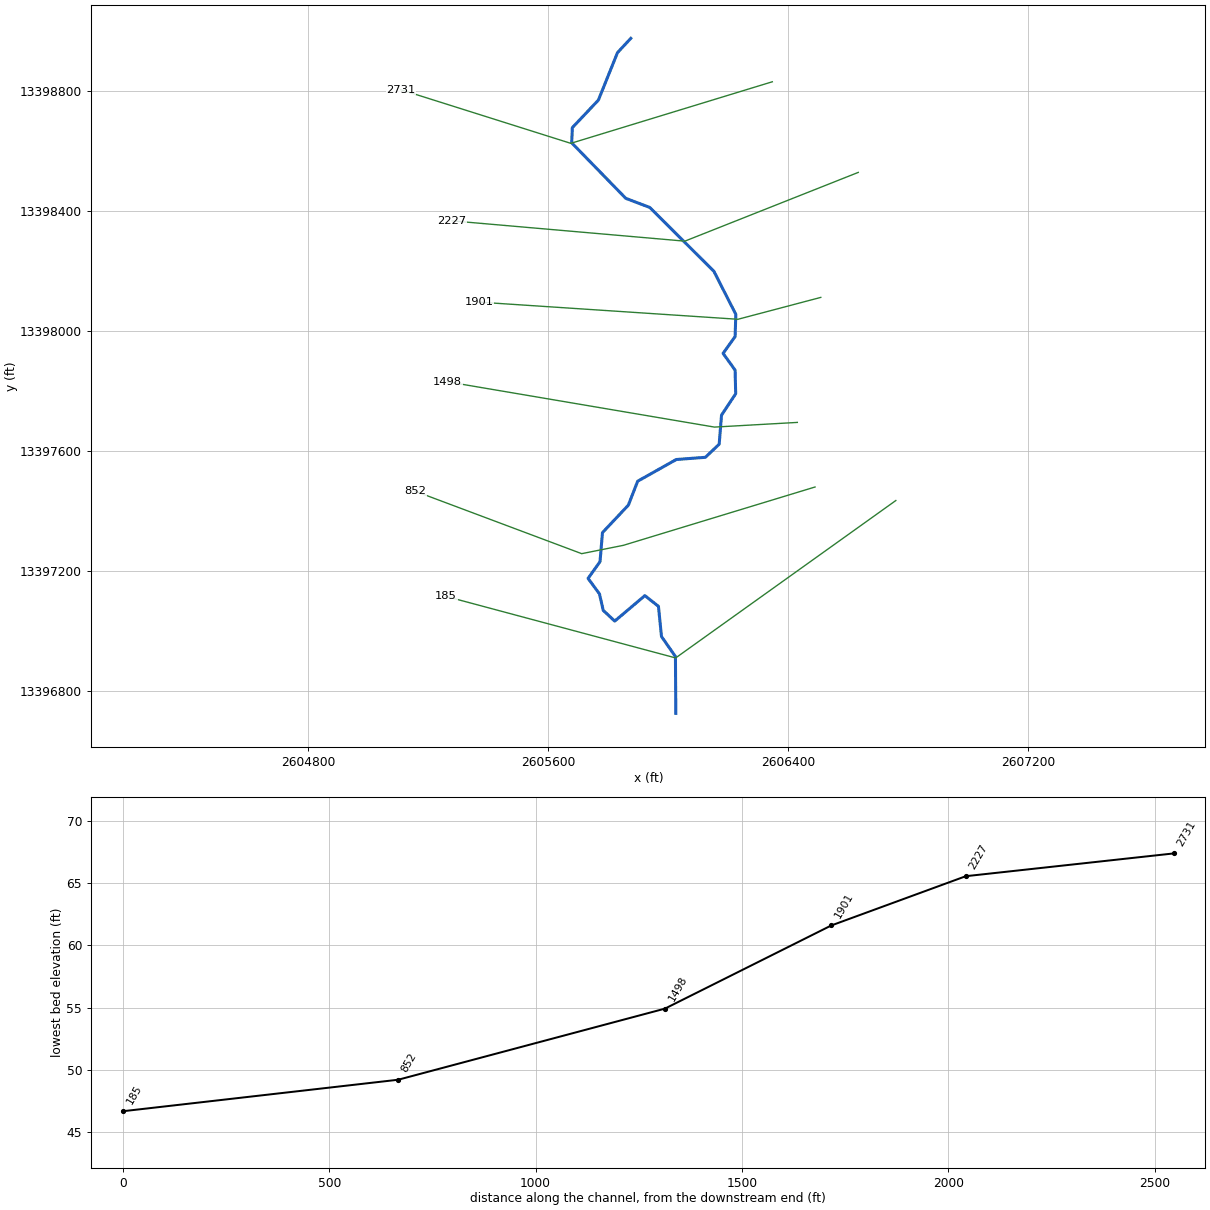
--- TRIB 5 TO KUY CREEK.prj (project) ---

Proj Title=TRIB 5 TO KUY CREEK Base Level Engineering
Current Plan=p01
Default Exp/Contr=0.3,0.1
English Units
Geom File=g01
Flow File=f01
Plan File=p01
Y Axis Title=Elevation
X Axis Title(PF)=Main Channel Distance
X Axis Title(XS)=Station
BEGIN DESCRIPTION:
TRIB 5 TO KUY CREEK
END DESCRIPTION:
DSS Export Rating Curves= 0
DSS Export Rating Curve Sorted= 0
DSS Export Volume Flow Curves= 0
DXF OffsetX= 0
DXF OffsetY= 0
DXF ScaleX= 1
DXF ScaleY= 10

--- TRIB 5 TO KUY CREEK.p01 (plan) ---

Plan Title=Multiple Run
Short Identifier=Multiple
Geom File=g01
Flow File=f01
Subcritical Flow
K Sum by GR= 0
Std Step Tol= 0.01
Critical Tol= 0.01
Num of Std Step Trials= 20
Max Error Tol= 0.3
Flow Tol Ratio= 0.001
Split Flow NTrial= 30
Split Flow Tol= 0.02
Split Flow Ratio= 0.02
Log Output Level= 0
Friction Slope Method= 1
Unsteady Friction Slope Method= 2
Unsteady Bridges Friction Slope Method= 1
Parabolic Critical Depth
Global Vel Dist=  1 , 1 , 1
Global Log Level= 0
CheckData=True
Encroach Param= -1, 0, 0, 0
BEGIN DESCRIPTION:
Multiple Run
END DESCRIPTION:

--- TRIB 5 TO KUY CREEK.f01 (steady flow) ---

Flow Title=Multiple
Number of Profiles=7
Profile Names=10-year,25-year,50-year,1pct_min,100-year,1pct_plu,500-year
River Rch & RM= TRIB 5 TO KUY CR,Reach-1,2731
     420     633     812     504    1005    2005    1521
Boundary for River Rch & Prof#=TRIB 5 TO KUY CR,Reach-1,1
Up Type=0
Dn Type=3
Dn Slope=0.005
Boundary for River Rch & Prof#=TRIB 5 TO KUY CR,Reach-1,2
Up Type=0
Dn Type=3
Dn Slope=0.005
Boundary for River Rch & Prof#=TRIB 5 TO KUY CR,Reach-1,3
Up Type=0
Dn Type=3
Dn Slope=0.005
Boundary for River Rch & Prof#=TRIB 5 TO KUY CR,Reach-1,4
Up Type=0
Dn Type=3
Dn Slope=0.005
Boundary for River Rch & Prof#=TRIB 5 TO KUY CR,Reach-1,5
Up Type=0
Dn Type=3
Dn Slope=0.005
Boundary for River Rch & Prof#=TRIB 5 TO KUY CR,Reach-1,6
Up Type=0
Dn Type=3
Dn Slope=0.005
Boundary for River Rch & Prof#=TRIB 5 TO KUY CR,Reach-1,7
Up Type=0
Dn Type=3
Dn Slope=0.005

--- TRIB 5 TO KUY CREEK.g01 (geometry) ---

Geom Title=Existing Conditions
Program Version=4.10

River Reach=TRIB 5 TO KUY CR,Reach-1
Reach XY= 30
        2605875.       13398975.      2605830.67     13398927.36
      2605766.84     13398768.95      2605680.08     13398677.28
       2605678.1     13398626.65      2605858.33     13398441.65
      2605938.21     13398411.37      2606151.99     13398198.47
       2606225.1      13398054.9      2606222.64     13397980.89
      2606182.57       13397925.      2606222.64     13397869.11
      2606224.61     13397790.28      2606177.36     13397719.02
       2606169.6     13397622.29      2606123.75     13397578.51
      2606026.59     13397571.17      2605897.86     13397498.84
      2605866.81     13397418.98      2605780.53     13397327.42
      2605772.44      13397230.9      2605732.53     13397174.99
      2605770.55     13397123.28      2605783.12     13397068.29
      2605821.42      13397032.5      2605921.87     13397117.47
      2605967.14     13397081.83      2605977.36     13396980.98
      2606023.79      13396914.5        2606025.       13396725.

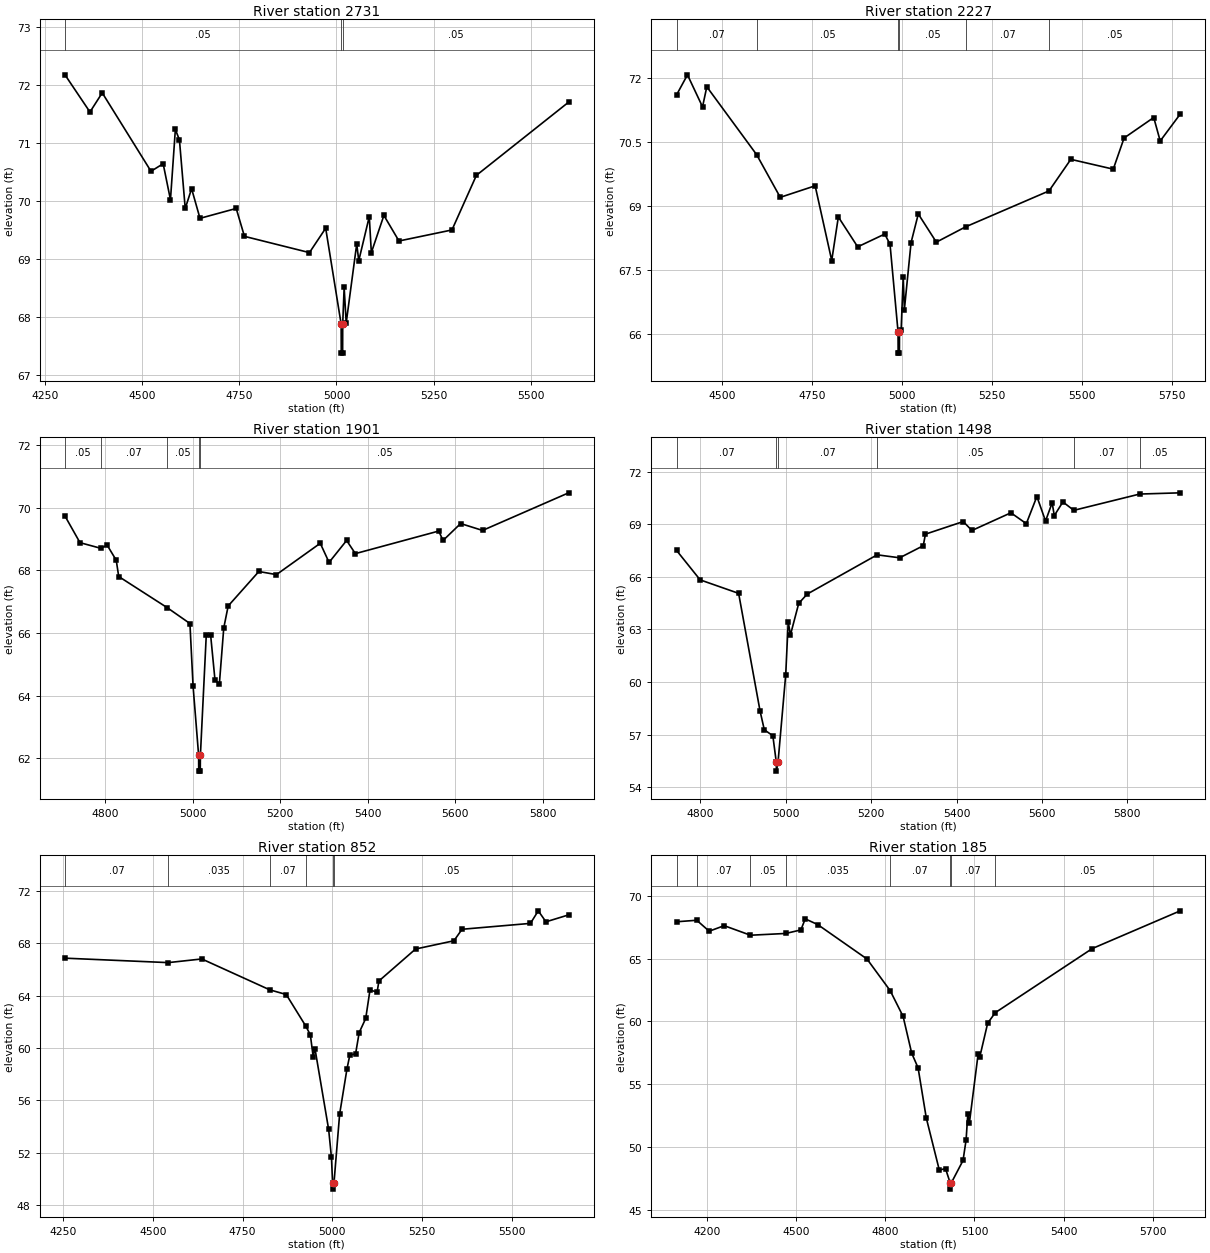
Type RM Length L Ch R = 1 ,2731    ,504,504,504
BEGIN DESCRIPTION:
TRIB 5 TO KUY CREEK 6.0
END DESCRIPTION:
XS GIS Cut Line= 3
       2606346.7     13398830.23        2605675.       13398625.
      2605108.59     13398803.75
#Sta/Elev= 30
  4301.2   72.17  4365.5   71.53  4397.1   71.86  4522.6   70.51  4553.9   70.64
  4572.7   70.02  4585.3   71.23  4595.8   71.05  4610.7   69.87  4627.1   70.21
  4648.7    69.7  4741.9   69.87  4763.1   69.39  4930.4   69.11  4972.2   69.53
    5012   67.88  5012.3   67.38  5015.8   67.38    5016   67.88  5019.7   68.51
    5025    67.9  5052.1   69.26  5057.3   68.97  5084.4   69.73  5089.7   69.11
    5122   69.75  5160.8   69.31  5297.2    69.5  5360.1   70.44  5597.5    71.7
#Mann= 3 ,-1 , 0
  4301.2     .05       0    5012     .05       0    5016     .05       0
Bank Sta=5012,5016
XS Rating Curve= 0 ,0
Exp/Cntr=0.3,0.1

Type RM Length L Ch R = 1 ,2227    ,326,326,326
BEGIN DESCRIPTION:
Mapping XS f0d91233
END DESCRIPTION:
XS GIS Cut Line= 3
      2606633.16     13398528.15      2606055.07     13398298.99
      2605279.47     13398366.66
#Sta/Elev= 30
  4373.7    71.6    4404   72.07  4445.9   71.32  4457.8   71.79  4596.3    70.2
    4662    69.2    4759   69.47  4805.1   67.72  4823.5   68.74  4877.3   68.04
  4952.6   68.34  4967.2    68.1  4989.5   66.05  4989.8   65.55  4993.3   65.55
  4993.5   66.05  4998.1   66.09  5003.9   67.34  5007.1   66.57  5025.7   68.14
  5045.8   68.81    5096   68.15  5177.7   68.51  5409.2   69.35  5469.9   70.09
  5587.9   69.86    5618   70.59  5700.4   71.07  5718.4   70.52  5774.1   71.15
#Mann= 6 ,-1 , 0
  4373.7     .07       0  4596.3     .05       0  4989.5     .05       0
  4993.5     .05       0  5177.7     .07       0  5409.2     .05       0
Bank Sta=4989.5,4993.5
XS Rating Curve= 0 ,0
Exp/Cntr=0.3,0.1

Type RM Length L Ch R = 1 ,1901    ,403,403,403
BEGIN DESCRIPTION:
Mapping XS 7ca56467
END DESCRIPTION:
XS GIS Cut Line= 3
      2606508.21      13398111.5      2606232.15     13398038.58
      2605368.77     13398095.79
#Sta/Elev= 30
    4708   69.73  4742.3   68.88  4789.8    68.7  4804.4    68.8  4825.1   68.32
  4830.8    67.8  4942.2    66.8  4993.5    66.3  5000.7    64.3  5013.4   62.09
  5013.6   61.59  5017.1   61.59  5017.4   62.09  5030.8   65.92  5040.8   65.93
  5050.8   64.49  5060.8   64.38  5070.8   66.16  5080.9   66.86    5151   67.96
  5191.1   67.86  5291.3   68.86  5311.4   68.25  5351.5   68.95  5371.5   68.53
  5561.9   69.25  5571.9   68.95    5612   69.49  5662.1   69.27  5858.8   70.47
#Mann= 5 ,-1 , 0
    4708     .05       0  4789.8     .07       0  4942.2     .05       0
  5013.4     .05       0  5017.4     .05       0
Bank Sta=5013.4,5017.4
XS Rating Curve= 0 ,0
Exp/Cntr=0.3,0.1

Type RM Length L Ch R = 1 ,1498    ,646,646,646
BEGIN DESCRIPTION:
Mapping XS a011f218
END DESCRIPTION:
XS GIS Cut Line= 3
      2606430.09     13397694.83      2606154.02      13397679.2
      2605264.14     13397830.12
#Sta/Elev= 30
  4744.5   67.51  4799.7   65.83  4889.8   65.06  4939.9   58.35  4949.9   57.27
  4969.9   56.93    4978   55.41  4978.2   54.91    4982   55.41    5000   60.41
  5005.9   63.45    5011   62.68  5030.5   64.49  5050.4   65.02  5214.1   67.26
  5266.8   67.09    5322   67.78  5327.1   68.44  5415.6   69.16  5435.9   68.65
  5527.2   69.66  5563.3   69.04    5588   70.59  5608.3   69.19  5623.7   70.23
  5628.8    69.5  5648.9   70.28  5674.5    69.8  5828.6   70.73  5923.6    70.8
#Mann= 6 ,-1 , 0
  4744.5     .07       0    4978     .05       0    4982     .07       0
  5214.1     .05       0  5674.5     .07       0  5828.6     .05       0
Bank Sta=4978,4982
XS Rating Curve= 0 ,0
Exp/Cntr=0.3,0.1

Type RM Length L Ch R = 1 ,852     ,667,667,667
BEGIN DESCRIPTION:
Mapping XS daf7d95d
END DESCRIPTION:
XS GIS Cut Line= 4
      2606489.14     13397479.56      2605850.21      13397285.1
      2605711.32     13397257.33       2605155.8     13397465.65
#Sta/Elev= 30
  4255.4   66.86    4543   66.52  4636.5    66.8  4825.7   64.44  4871.7   64.08
    4926   61.67  4938.8      61  4946.6   59.34  4951.7   59.94  4989.8   53.76
  4997.6   51.62  5000.7    49.7  5000.9    49.2  5004.7    49.7  5020.4   54.94
  5040.8   58.39  5048.6   59.43  5064.9   59.56  5074.8   61.17    5093   62.25
    5105   64.44  5124.6   64.25  5129.9   65.12  5231.9   67.56  5338.7   68.19
  5361.3   69.07  5551.8   69.52  5573.6   70.48    5595   69.64  5658.2   70.17
#Mann= 6 ,-1 , 0
  4255.4     .07       0    4543    .035       0  4825.7     .07       0
    4926     .05       0  5000.7     .05       0  5004.7     .05       0
Bank Sta=5000.7,5004.7
XS Rating Curve= 0 ,0
Exp/Cntr=0.3,0.1

Type RM Length L Ch R = 1 ,185     ,0,0,0
BEGIN DESCRIPTION:
TRIB 5 TO KUY CREEK 4.0
END DESCRIPTION:
XS GIS Cut Line= 3
      2606758.42     13397434.48      2606024.49     13396909.79
      2605259.18     13397114.82
#Sta/Elev= 30
  4097.8   67.93  4165.7   68.05  4207.6   67.18    4258   67.62  4346.5   66.86
  4464.9      67    4516   67.28  4530.7   68.16  4572.5   67.71  4738.4   64.97
  4816.3   62.46    4860    60.4  4888.7   57.49  4910.4   56.31  4937.9   52.33
  4981.7   48.19  5002.7    48.3  5018.2   47.17  5018.4   46.67  5022.2   47.17
  5061.6   48.95  5071.9   50.59  5077.6   52.65  5082.8    51.9  5112.5   57.44
  5117.6   57.15  5144.4   59.86  5169.9    60.7  5496.4    65.8  5792.3    68.8
#Mann= 8 ,-1 , 0
  4097.8    .035       0  4165.7     .07       0  4346.5     .05       0
  4464.9    .035       0  4816.3     .07       0  5018.2     .05       0
  5022.2     .07       0  5169.9     .05       0
Bank Sta=5018.2,5022.2
XS Rating Curve= 0 ,0
Exp/Cntr=0.3,0.1

Chan Stop Cuts=-1
Use User Specified Reach Order=0
Composite Channel Slope=5