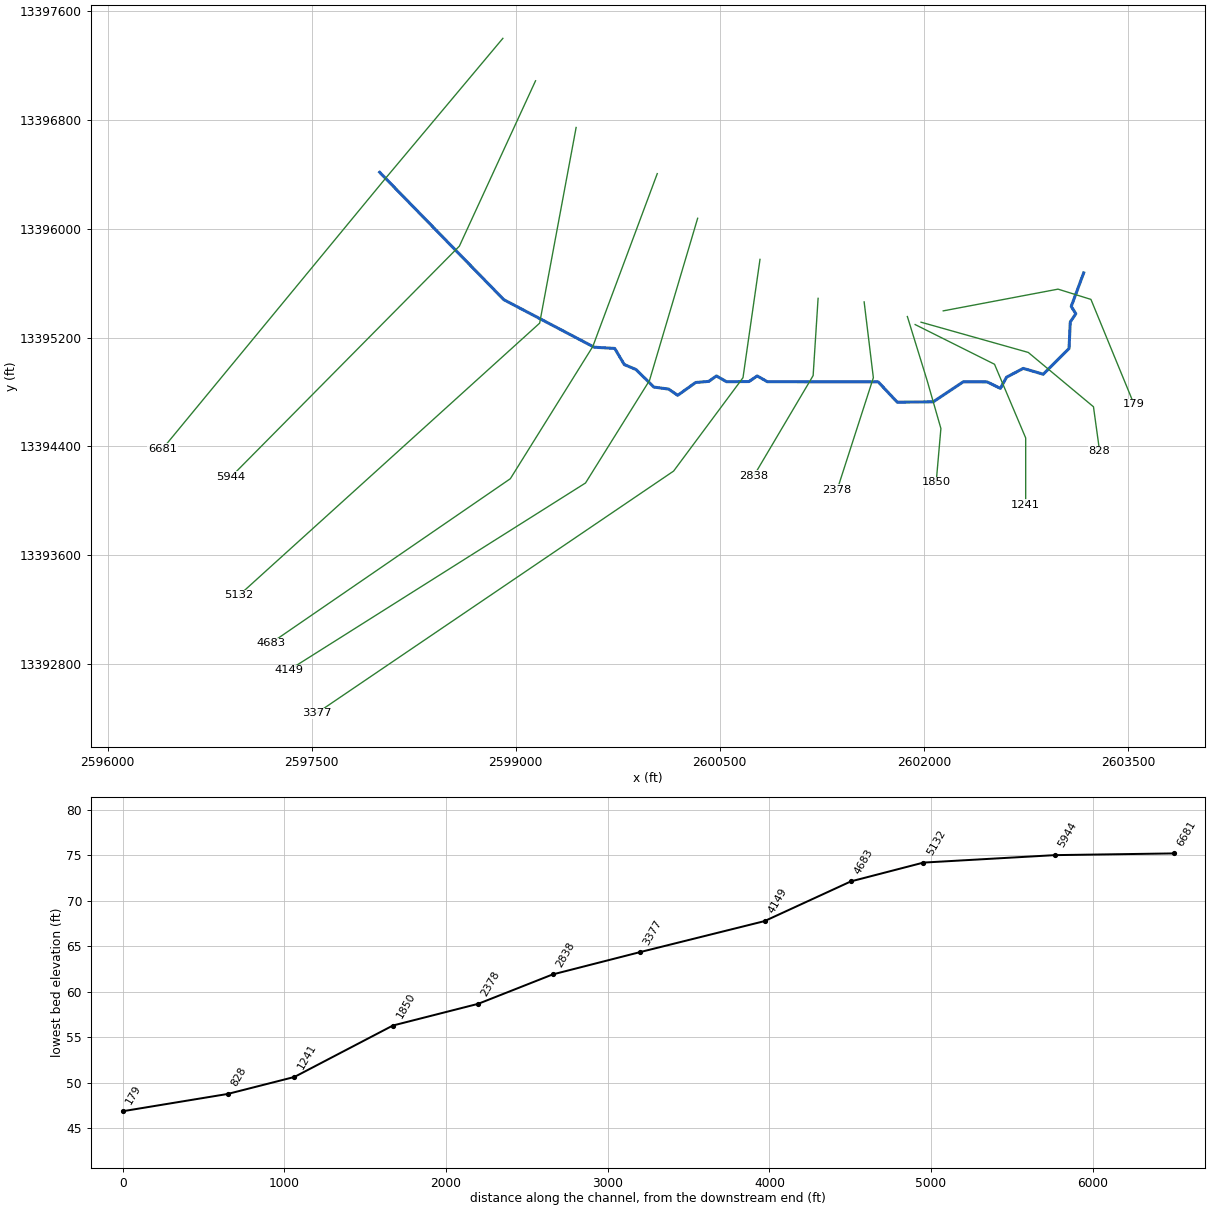
--- TRIB 6 TO KUY CREEK.prj (project) ---

Proj Title=TRIB 6 TO KUY CREEK Base Level Engineering
Current Plan=p01
Default Exp/Contr=0.3,0.1
English Units
Geom File=g01
Flow File=f01
Plan File=p01
Y Axis Title=Elevation
X Axis Title(PF)=Main Channel Distance
X Axis Title(XS)=Station
BEGIN DESCRIPTION:
TRIB 6 TO KUY CREEK
END DESCRIPTION:
DSS Export Rating Curves= 0
DSS Export Rating Curve Sorted= 0
DSS Export Volume Flow Curves= 0
DXF OffsetX= 0
DXF OffsetY= 0
DXF ScaleX= 1
DXF ScaleY= 10

--- TRIB 6 TO KUY CREEK.p01 (plan) ---

Plan Title=Multiple Run
Short Identifier=Multiple
Geom File=g01
Flow File=f01
Subcritical Flow
K Sum by GR= 0
Std Step Tol= 0.01
Critical Tol= 0.01
Num of Std Step Trials= 20
Max Error Tol= 0.3
Flow Tol Ratio= 0.001
Split Flow NTrial= 30
Split Flow Tol= 0.02
Split Flow Ratio= 0.02
Log Output Level= 0
Friction Slope Method= 1
Unsteady Friction Slope Method= 2
Unsteady Bridges Friction Slope Method= 1
Parabolic Critical Depth
Global Vel Dist=  1 , 1 , 1
Global Log Level= 0
CheckData=True
Encroach Param= -1, 0, 0, 0
BEGIN DESCRIPTION:
Multiple Run
END DESCRIPTION:

--- TRIB 6 TO KUY CREEK.f01 (steady flow) ---

Flow Title=Multiple
Number of Profiles=7
Profile Names=10-year,25-year,50-year,1pct_min,100-year,1pct_plu,500-year
River Rch & RM= TRIB 6 TO KUY CR,Reach-1,6681
     285     414     517     312     623    1242     892
River Rch & RM= TRIB 6 TO KUY CR,Reach-1,5132
     422     630     803     494     985    1966    1466
River Rch & RM= TRIB 6 TO KUY CR,Reach-1,3377
     616     949    1236     777    1551    3095    2413
River Rch & RM= TRIB 6 TO KUY CR,Reach-1,828
    1011    1606    2135    1369    2731    5449    4418
Boundary for River Rch & Prof#=TRIB 6 TO KUY CR,Reach-1,1
Up Type=0
Dn Type=3
Dn Slope=0.005
Boundary for River Rch & Prof#=TRIB 6 TO KUY CR,Reach-1,2
Up Type=0
Dn Type=3
Dn Slope=0.005
Boundary for River Rch & Prof#=TRIB 6 TO KUY CR,Reach-1,3
Up Type=0
Dn Type=3
Dn Slope=0.005
Boundary for River Rch & Prof#=TRIB 6 TO KUY CR,Reach-1,4
Up Type=0
Dn Type=3
Dn Slope=0.005
Boundary for River Rch & Prof#=TRIB 6 TO KUY CR,Reach-1,5
Up Type=0
Dn Type=3
Dn Slope=0.005
Boundary for River Rch & Prof#=TRIB 6 TO KUY CR,Reach-1,6
Up Type=0
Dn Type=3
Dn Slope=0.005
Boundary for River Rch & Prof#=TRIB 6 TO KUY CR,Reach-1,7
Up Type=0
Dn Type=3
Dn Slope=0.005

--- TRIB 6 TO KUY CREEK.g01 (geometry) ---

Geom Title=Existing Conditions
Program Version=4.10

River Reach=TRIB 6 TO KUY CR,Reach-1
Reach XY= 30
       2597999.7     13396414.51      2598912.12     13395478.12
      2599576.56     13395128.76       2599727.7     13395119.64
      2599797.86     13395001.17      2599884.66     13394964.21
      2600015.21     13394835.52      2600123.41     13394821.11
      2600190.42     13394775.03      2600322.58     13394869.46
       2600419.1     13394877.56        2600475.     13394917.44
      2600549.88     13394874.89      2600714.56     13394876.38
        2600775.     13394917.44      2600849.88     13394874.89
      2601664.57     13394873.95      2601804.56     13394724.46
      2602069.07     13394727.24      2602290.16     13394874.62
      2602464.52     13394873.75      2602562.98     13394826.19
      2602607.98     13394908.42      2602731.11      13394973.2
       2602877.3     13394930.09      2603067.19     13395118.81
      2603076.38     13395314.57      2603117.21      13395375.1
      2603083.28     13395428.22        2603175.       13395675.

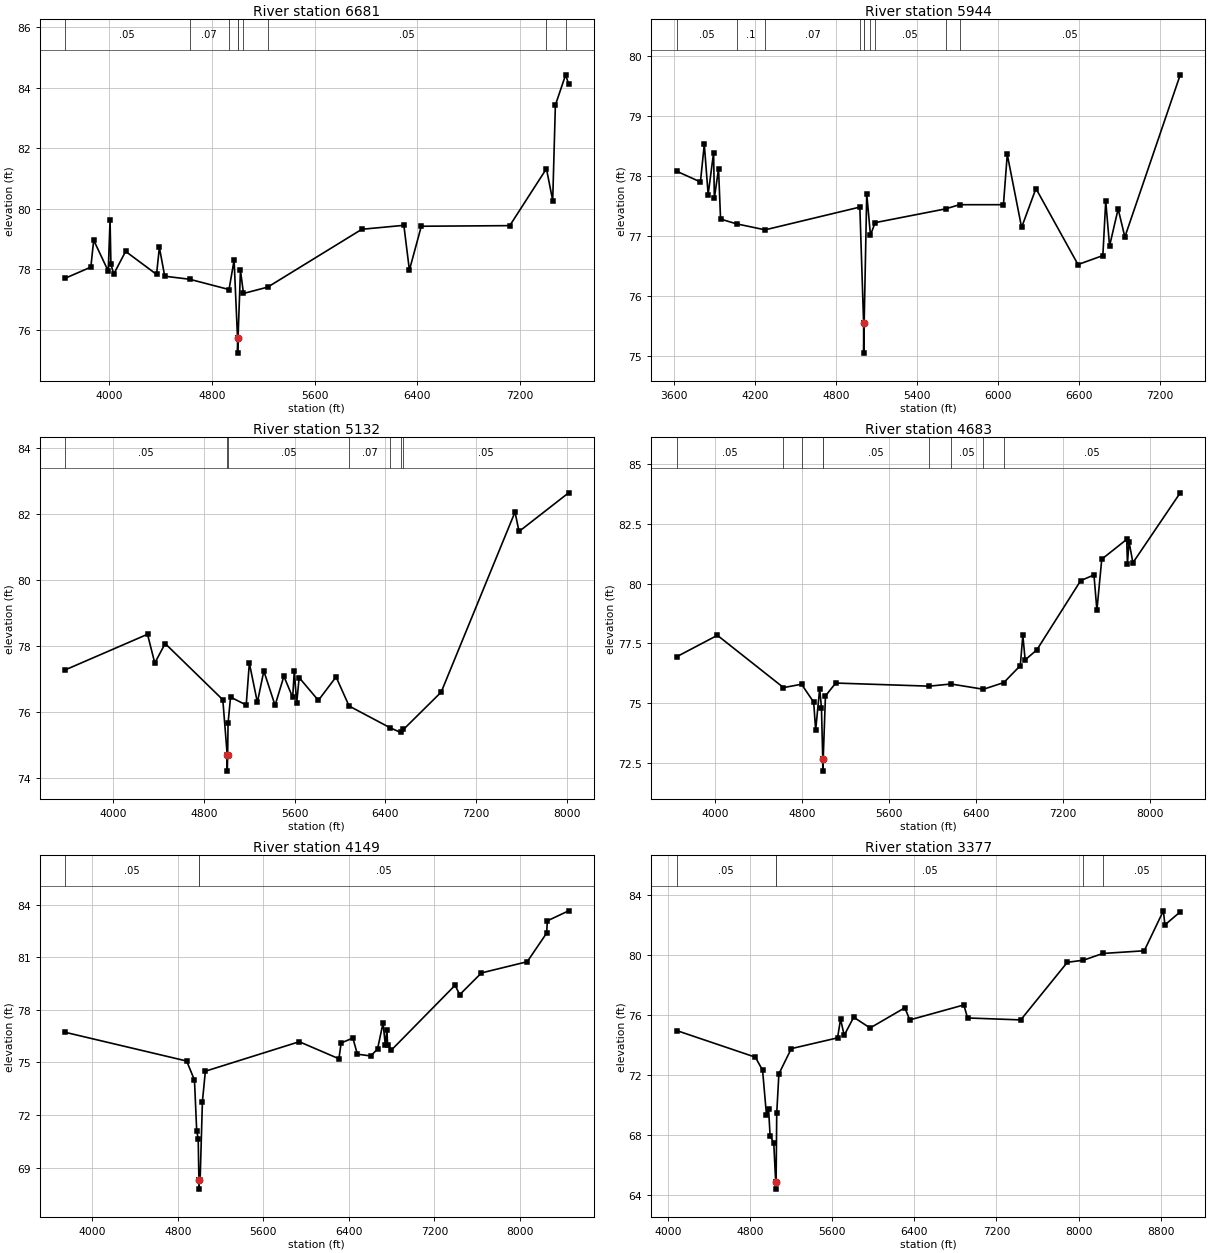
Type RM Length L Ch R = 1 ,6681    ,737,737,737
BEGIN DESCRIPTION:
TRIB 6 TO KUY CREEK 12.0
END DESCRIPTION:
XS GIS Cut Line= 3
      2598905.27     13397399.04      2598042.98     13396370.24
       2596403.5     13394381.47
#Sta/Elev= 30
  3657.3    77.7  3858.6   78.07  3880.7   78.96  3993.9   77.94  4008.2   79.61
  4014.9   78.16  4036.8   77.84  4129.2   78.59  4369.9   77.83    4392   78.72
  4433.6   77.77  4626.9   77.67  4934.1   77.33  4973.5    78.3  5000.2   75.73
  5000.4   75.23  5004.2   75.73    5023   77.96  5046.5    77.2  5235.2   77.41
  5967.7   79.32  6294.7   79.45  6337.8   77.97  6430.3   79.42  7118.9   79.44
  7404.3   81.32  7453.1   80.27  7473.9   83.42  7553.7   84.42  7577.1   84.11
#Mann= 9 ,-1 , 0
  3657.3     .05       0  4626.9     .07       0  4934.1     .05       0
  5000.2     .05       0  5004.2     .05       0  5046.5     .07       0
  5235.2     .05       0  7404.3    .035       0  7553.7    .063       0
Bank Sta=5000.2,5004.2
XS Rating Curve= 0 ,0
Exp/Cntr=0.3,0.1

Type RM Length L Ch R = 1 ,5944    ,812,812,812
BEGIN DESCRIPTION:
Mapping XS 9fd3a2a0
END DESCRIPTION:
XS GIS Cut Line= 3
      2599145.51     13397086.98      2598585.61      13395871.7
      2596905.92     13394174.65
#Sta/Elev= 30
  3621.8   78.08  3798.4    77.9  3826.9   78.53  3855.4   77.69  3895.8   78.39
  3901.3   77.63  3932.3   78.12  3947.2   77.28  4065.5    77.2  4276.6    77.1
  4977.6   77.48  5005.5   75.54  5005.7   75.04  5009.5   75.54  5028.6    77.7
  5056.1   77.01  5090.3   77.22  5611.2   77.45    5715   77.52  6039.8   77.52
  6068.1   78.36  6174.2   77.14  6280.2   77.79  6591.4   76.52  6775.2   76.67
  6796.5   77.58  6824.8   76.83  6888.4   77.45  6937.9   76.98  7347.6   79.69
#Mann= 10 ,-1 , 0
  3621.8     .05       0  4065.5      .1       0  4276.6     .07       0
  4977.6     .05       0  5005.5     .05       0  5009.5     .05       0
  5056.1     .07       0  5090.3     .05       0  5611.2     .07       0
    5715     .05       0
Bank Sta=5005.5,5009.5
XS Rating Curve= 0 ,0
Exp/Cntr=0.3,0.1

Type RM Length L Ch R = 1 ,5132    ,449,449,449
BEGIN DESCRIPTION:
Mapping XS d1bbbb33
END DESCRIPTION:
XS GIS Cut Line= 3
      2599443.84     13396743.85      2599175.67     13395305.56
      2596966.32     13393305.29
#Sta/Elev= 30
  3573.5   77.28  4301.7   78.36  4365.8   77.49  4457.3   78.08  4965.9   76.38
  5004.6   74.72  5004.9   74.22  5008.6   74.72  5012.3   75.67  5034.3   76.46
  5172.3   76.22    5200   77.49  5270.9    76.3  5327.7   77.25  5427.1   76.21
  5504.8   77.09  5582.5   76.45  5596.7   77.26  5617.7   76.27  5639.3   77.05
  5808.9   76.36  5965.1   77.07    6080   76.19  6443.3   75.53  6534.3   75.39
  6559.3   75.48  6892.4   76.61  7543.9   82.06    7579   81.47  8016.9   82.64
#Mann= 7 ,-1 , 0
  3573.5     .05       0  5004.6     .05       0  5008.6     .05       0
    6080     .07       0  6443.3     .05       0  6534.3     .07       0
  6559.3     .05       0
Bank Sta=5004.6,5008.6
XS Rating Curve= 0 ,0
Exp/Cntr=0.3,0.1

Type RM Length L Ch R = 1 ,4683    ,534,534,534
BEGIN DESCRIPTION:
Mapping XS d00302c5
END DESCRIPTION:
XS GIS Cut Line= 4
      2600040.26     13396404.54       2599566.3     13395133.68
       2598960.2       13394162.       2597200.7     13392953.73
#Sta/Elev= 30
  3644.8   76.94  4020.4   77.84    4629   75.65    4795   75.79  4906.9   75.04
    4925   73.87  4962.2    75.6  4978.4   74.81  4990.5   72.65  4990.7   72.15
  4994.5   72.65  5015.2    75.3  5109.6   75.84  5970.5   75.71  6170.5    75.8
  6469.2   75.58  6656.9   75.86  6808.7   76.57    6832   77.84  6853.4   76.81
  6960.9   77.23  7364.3   80.13  7486.7   80.37  7513.8   78.89  7558.5   81.03
  7788.5   81.86  7794.6   80.83  7809.5   81.76  7845.3   80.88  8280.8   83.81
#Mann= 9 ,-1 , 0
  3644.8     .05       0    4629     .07       0    4795     .05       0
  4990.5     .05       0  4994.5     .05       0  5970.5     .07       0
  6170.5     .05       0  6469.2     .07       0  6656.9     .05       0
Bank Sta=4990.5,4994.5
XS Rating Curve= 0 ,0
Exp/Cntr=0.3,0.1

Type RM Length L Ch R = 1 ,4149    ,772,772,772
BEGIN DESCRIPTION:
Mapping XS a73c9c88
END DESCRIPTION:
XS GIS Cut Line= 4
      2600337.12     13396076.36      2599982.96     13394883.68
      2599512.91     13394130.69      2597330.88     13392754.07
#Sta/Elev= 30
  3743.5   76.72    4882   75.08    4955   73.99  4975.8    71.1  4989.8   70.65
  4996.5   68.28  4996.7   67.78  5000.6   68.28    5008   68.32  5029.2   72.77
  5056.8    74.5  5935.3   76.18    6306   75.21  6327.2   76.11  6436.7   76.39
    6479   75.47  6603.8   75.37  6667.3   75.76  6719.1   77.25  6740.3   75.99
  6755.6   76.87  6761.5   75.99    6798   75.71  7393.4    79.4  7435.8   78.86
  7639.4    80.1  8067.8   80.74  8249.4   82.37  8256.1   83.07  8455.3   83.64
#Mann= 3 ,-1 , 0
  3743.5     .05       0  4996.5     .05       0  5000.6     .05       0
Bank Sta=4996.5,5000.6
XS Rating Curve= 0 ,0
Exp/Cntr=0.3,0.1

Type RM Length L Ch R = 1 ,3377    ,539,539,539
BEGIN DESCRIPTION:
Mapping XS 346f545c
END DESCRIPTION:
XS GIS Cut Line= 4
      2600795.46      13395774.3      2600670.46     13394904.52
      2600160.35     13394218.19      2597534.94     13392437.27
#Sta/Elev= 30
  4084.2   74.96  4851.3   73.18    4922   72.31  4960.1   69.31  4980.7    69.7
  4995.3   67.92  5030.8   67.47  5049.5   64.86  5049.7   64.36  5053.8   64.86
    5060   69.44  5080.9   72.06  5201.8   73.75  5652.4   74.47  5681.6   75.72
  5717.1   74.64  5809.6   75.85  5969.3   75.13  6307.7   76.48  6356.2   75.67
  6882.7   76.67  6918.7    75.8  7436.8   75.67  7890.8   79.52  8047.5   79.66
  8236.4   80.11    8640   80.29  8826.3   82.96  8841.3   82.02  8990.5   82.89
#Mann= 5 ,-1 , 0
  4084.2     .05       0  5049.5     .05       0  5053.8     .05       0
  8047.5     .07       0  8236.4     .05       0
Bank Sta=5049.5,5053.8
XS Rating Curve= 0 ,0
Exp/Cntr=0.3,0.1

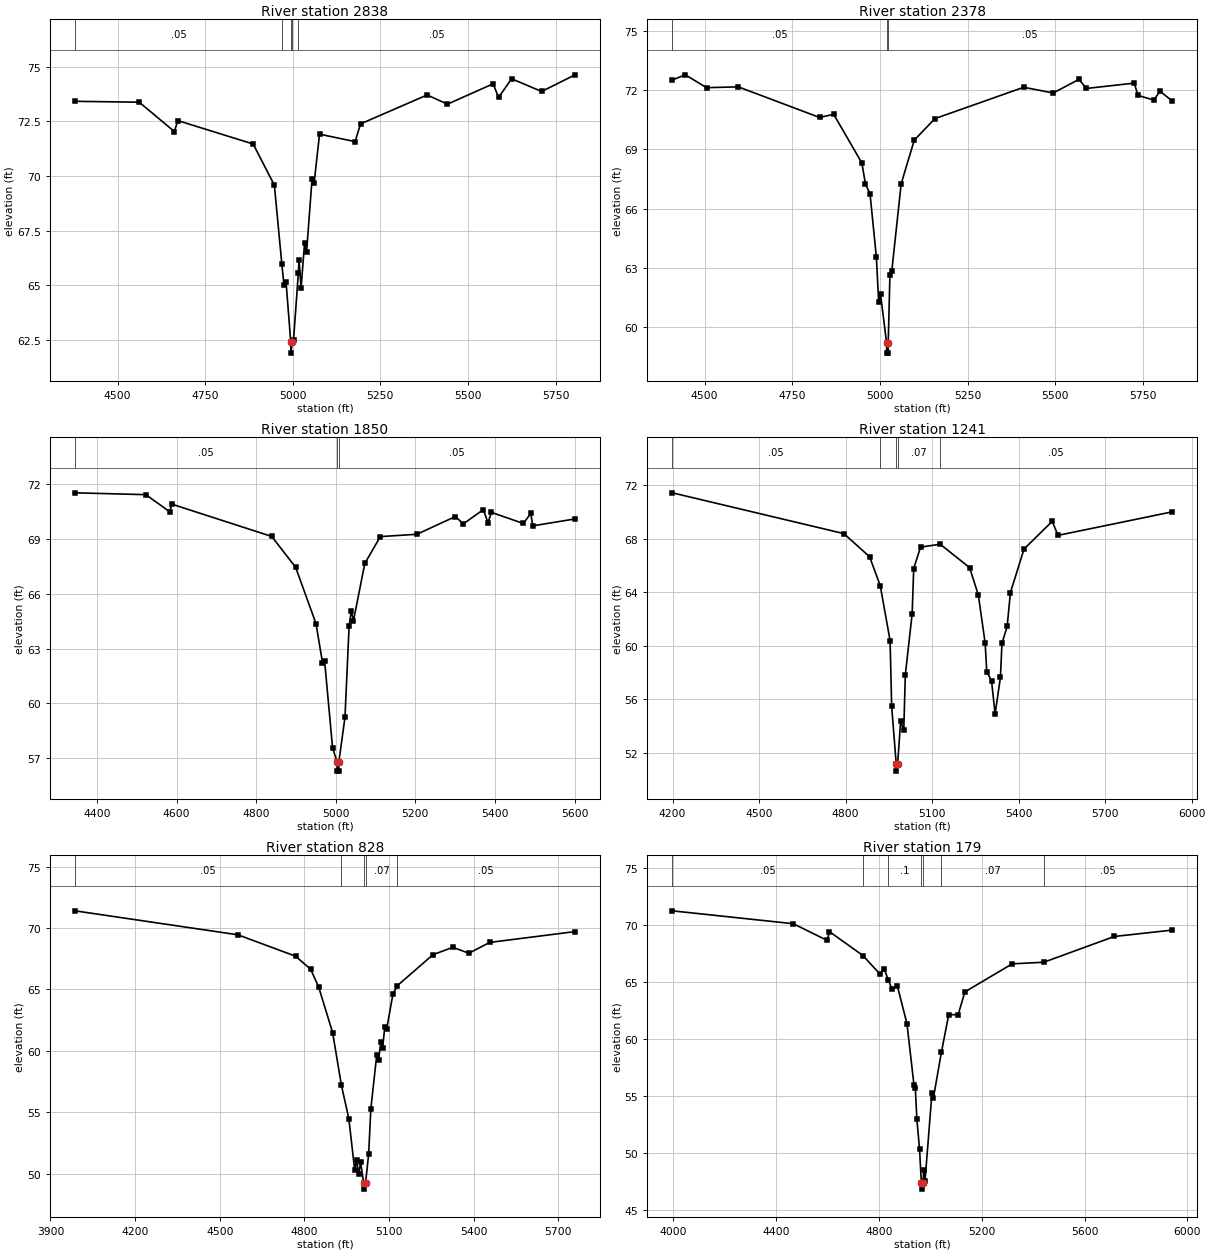
Type RM Length L Ch R = 1 ,2838    ,460,460,460
BEGIN DESCRIPTION:
Mapping XS 9278877c
END DESCRIPTION:
XS GIS Cut Line= 3
      2601222.54     13395487.82      2601186.09     13394920.14
      2600749.27     13394181.72
#Sta/Elev= 30
  4378.7   73.41  4561.9   73.37  4662.1   72.03  4672.1   72.53    4887   71.46
  4947.5   69.58  4968.8   65.98    4975      65  4980.9   65.15  4994.3   62.41
  4994.6   61.91  4998.7   62.41  5002.3   62.53    5016   65.58  5017.9   66.16
  5023.7   64.88  5033.6   66.92  5039.4   66.52    5055   69.86  5060.8   69.66
  5076.4   71.91  5177.8   71.57  5193.5   72.38  5383.4    73.7  5441.5   73.28
  5571.7   74.21  5587.4   73.59  5624.4   74.44  5710.2   73.86  5805.5   74.62
#Mann= 5 ,-1 , 0
  4378.7     .05       0  4968.8     .07       0  4994.3     .05       0
  4998.7     .07       0    5016     .05       0
Bank Sta=4994.3,4998.7
XS Rating Curve= 0 ,0
Exp/Cntr=0.3,0.1

Type RM Length L Ch R = 1 ,2378    ,528,528,528
BEGIN DESCRIPTION:
Mapping XS f5b9449c
END DESCRIPTION:
XS GIS Cut Line= 3
      2601561.09      13395461.8       2601628.8     13394904.52
      2601363.17     13394081.61
#Sta/Elev= 30
    4408   72.52  4445.1   72.78  4505.5   72.13  4596.2   72.17  4827.9   70.62
  4868.2   70.78  4948.7   68.31  4958.8   67.24  4971.8   66.76  4989.9   63.55
  4996.6   61.25  5001.8   61.67  5019.2   59.18  5019.5   58.68  5023.4   58.68
  5023.7   59.18  5028.6   62.64  5033.9   62.84  5060.7   67.26    5098   69.47
  5156.8   70.56  5410.2   72.15  5494.3   71.86  5567.8   72.55    5589   72.09
  5725.5   72.36    5736   71.74  5781.3    71.5    5799   71.95  5834.1   71.45
#Mann= 3 ,-1 , 0
    4408     .05       0  5019.2     .05       0  5023.7     .05       0
Bank Sta=5019.2,5023.7
XS Rating Curve= 0 ,0
Exp/Cntr=0.3,0.1

Type RM Length L Ch R = 1 ,1850    ,609,609,609
BEGIN DESCRIPTION:
Mapping XS d42126af
END DESCRIPTION:
XS GIS Cut Line= 4
      2601878.79     13395354.17      2602024.63     13394881.95
      2602125.32     13394531.25      2602090.61     13394135.47
#Sta/Elev= 30
  4344.8   71.54  4522.7   71.44  4582.8    70.5    4588   70.92    4839   69.15
  4899.1   67.46  4950.3   64.37  4966.6   62.24  4971.8   62.35  4991.9   57.58
  5003.2   56.79  5003.5   56.29  5007.4   56.29  5007.7   56.79  5023.1   59.24
  5033.5   64.24  5039.2   65.09  5044.4   64.52  5072.9   67.67  5111.9   69.14
  5203.9   69.27  5300.5   70.24  5320.6   69.84  5370.8   70.62  5382.5    69.9
  5390.9   70.47  5471.2   69.86    5490   70.41    5495   69.73  5601.2   70.11
#Mann= 3 ,-1 , 0
  4344.8     .05       0  5003.2     .05       0  5007.7     .05       0
Bank Sta=5003.2,5007.7
XS Rating Curve= 0 ,0
Exp/Cntr=0.3,0.1

Type RM Length L Ch R = 1 ,1241    ,413,413,413
BEGIN DESCRIPTION:
Mapping XS 294042e1
END DESCRIPTION:
XS GIS Cut Line= 4
      2601936.09     13395295.14      2602519.42     13395003.48
      2602748.59     13394461.81      2602748.59     13393968.54
#Sta/Elev= 30
  4199.4   71.43  4794.3   68.38  4883.3   66.65  4920.3   64.49  4954.4   60.38
  4959.8   55.48  4975.8   51.13  4976.1   50.63  4980.4   51.13  4991.1    54.4
  5001.8   53.67  5007.2   57.83  5030.9   62.39  5036.3   65.77    5060   67.37
  5128.1   67.59    5230   65.84  5260.4   63.79  5284.1   60.18  5289.5   58.07
    5306   57.39  5318.6   54.91  5336.9   57.63  5342.3   60.18  5360.3   61.44
  5371.5   63.97  5418.8   67.23  5516.5    69.3  5536.5   68.25    5933   70.01
#Mann= 5 ,-1 , 0
  4199.4     .05       0  4920.3     .07       0  4975.8     .05       0
  4980.4     .07       0  5128.1     .05       0
Bank Sta=4975.8,4980.4
XS Rating Curve= 0 ,0
Exp/Cntr=0.3,0.1

Type RM Length L Ch R = 1 ,828     ,649,649,649
BEGIN DESCRIPTION:
Mapping XS 88084775
END DESCRIPTION:
XS GIS Cut Line= 4
      2601979.46     13395312.51      2602767.68     13395090.28
      2603246.85     13394690.98      2603291.99     13394364.57
#Sta/Elev= 30
  3987.1    71.4  4564.3   69.45  4768.6   67.71  4822.1   66.65  4850.7    65.2
  4900.2   61.48  4931.2   57.21  4957.5    54.5  4978.3   50.32  4984.8   51.11
  4992.6   49.95  4999.1   50.96  5010.1   49.26  5010.6   48.76  5016.8   49.26
  5027.8   51.61  5035.6   55.31  5056.4   59.66  5062.9   59.23  5070.7   60.71
  5077.2   60.26    5085   61.94  5091.6   61.78  5113.7   64.61  5129.4   65.31
  5255.6   67.83  5325.9   68.43  5383.1   67.95  5456.9   68.83  5759.3   69.71
#Mann= 5 ,-1 , 0
  3987.1     .05       0  4931.2     .07       0  5010.1     .05       0
  5016.8     .07       0  5129.4     .05       0
Bank Sta=5010.1,5016.8
XS Rating Curve= 0 ,0
Exp/Cntr=0.3,0.1

Type RM Length L Ch R = 1 ,179     ,0,0,0
BEGIN DESCRIPTION:
TRIB 6 TO KUY CREEK 1.0
END DESCRIPTION:
XS GIS Cut Line= 4
      2602142.66     13395395.83      2602986.43     13395555.56
      2603228.25     13395480.09      2603545.13     13394709.15
#Sta/Elev= 30
    3996   71.27  4466.6   70.14  4598.9   68.67  4606.9   69.45  4737.5   67.35
  4802.4   65.76  4821.3   66.13    4837   65.17  4851.5   64.37  4871.2   64.71
  4908.9   61.38  4936.2   56.01  4941.4   55.76  4947.5   52.99    4958   50.35
  4965.1   47.36  4965.6   46.86  4971.9   47.36  4973.9   48.55  4979.2   47.58
  5006.4   55.33  5011.7   54.84  5042.9   58.85  5071.4   62.16  5108.1   62.16
  5134.4   64.16  5318.4   66.62  5441.5   66.76  5715.7   69.02  5941.6   69.58
#Mann= 7 ,-1 , 0
    3996     .05       0  4737.5     .07       0    4837      .1       0
  4965.1     .05       0  4971.9      .1       0  5042.9     .07       0
  5441.5     .05       0
Bank Sta=4965.1,4971.9
XS Rating Curve= 0 ,0
Exp/Cntr=0.3,0.1

Chan Stop Cuts=-1
Use User Specified Reach Order=0
Composite Channel Slope=5