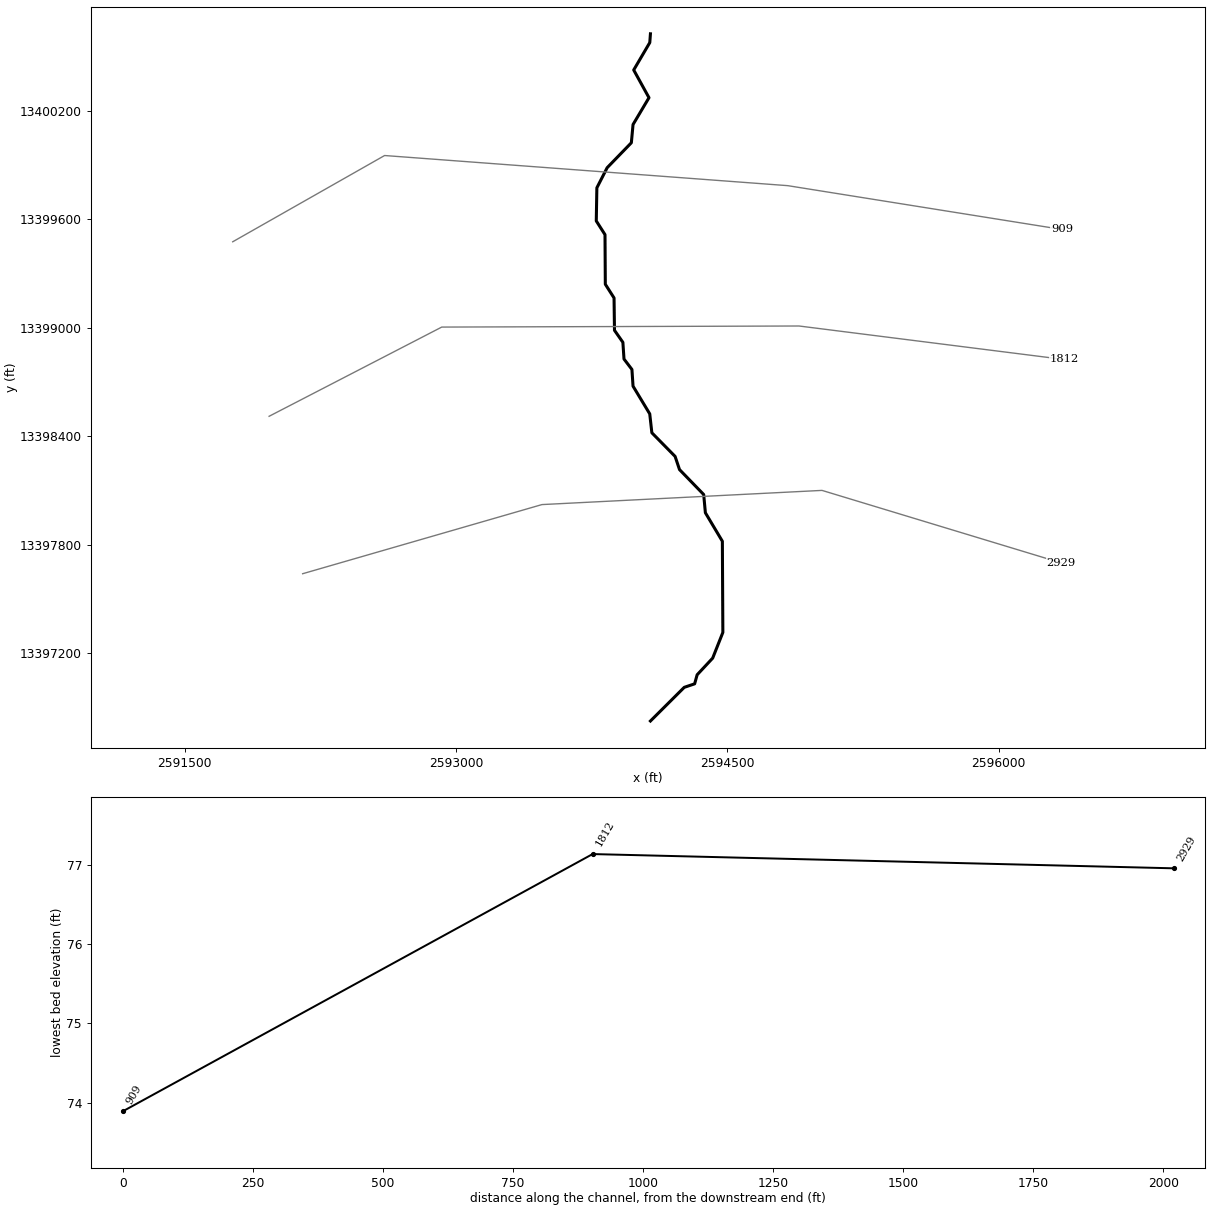
--- TRIB 9 TO KUY CREEK.prj (project) ---

Proj Title=TRIB 9 TO KUY CREEK Base Level Engineering
Current Plan=p01
Default Exp/Contr=0.3,0.1
English Units
Geom File=g01
Flow File=f01
Plan File=p01
Y Axis Title=Elevation
X Axis Title(PF)=Main Channel Distance
X Axis Title(XS)=Station
BEGIN DESCRIPTION:
TRIB 9 TO KUY CREEK
END DESCRIPTION:
DSS Export Rating Curves= 0
DSS Export Rating Curve Sorted= 0
DSS Export Volume Flow Curves= 0
DXF OffsetX= 0
DXF OffsetY= 0
DXF ScaleX= 1
DXF ScaleY= 10

--- TRIB 9 TO KUY CREEK.p01 (plan) ---

Plan Title=Multiple Run
Short Identifier=Multiple
Geom File=g01
Flow File=f01
Subcritical Flow
K Sum by GR= 0
Std Step Tol= 0.01
Critical Tol= 0.01
Num of Std Step Trials= 20
Max Error Tol= 0.3
Flow Tol Ratio= 0.001
Split Flow NTrial= 30
Split Flow Tol= 0.02
Split Flow Ratio= 0.02
Log Output Level= 0
Friction Slope Method= 1
Unsteady Friction Slope Method= 2
Unsteady Bridges Friction Slope Method= 1
Parabolic Critical Depth
Global Vel Dist=  1 , 1 , 1
Global Log Level= 0
CheckData=True
Encroach Param= -1, 0, 0, 0
BEGIN DESCRIPTION:
Multiple Run
END DESCRIPTION:

--- TRIB 9 TO KUY CREEK.f01 (steady flow) ---

Flow Title=Multiple
Number of Profiles=7
Profile Names=10-year,25-year,50-year,1pct_min,100-year,1pct_plu,500-year
River Rch & RM= TRIB 9 TO KUY CR,Reach-1,2929
     556     853    1106     693    1382    2758    2134
Boundary for River Rch & Prof#=TRIB 9 TO KUY CR,Reach-1,1
Up Type=0
Dn Type=3
Dn Slope=0.005
Boundary for River Rch & Prof#=TRIB 9 TO KUY CR,Reach-1,2
Up Type=0
Dn Type=3
Dn Slope=0.005
Boundary for River Rch & Prof#=TRIB 9 TO KUY CR,Reach-1,3
Up Type=0
Dn Type=3
Dn Slope=0.005
Boundary for River Rch & Prof#=TRIB 9 TO KUY CR,Reach-1,4
Up Type=0
Dn Type=3
Dn Slope=0.005
Boundary for River Rch & Prof#=TRIB 9 TO KUY CR,Reach-1,5
Up Type=0
Dn Type=3
Dn Slope=0.005
Boundary for River Rch & Prof#=TRIB 9 TO KUY CR,Reach-1,6
Up Type=0
Dn Type=3
Dn Slope=0.005
Boundary for River Rch & Prof#=TRIB 9 TO KUY CR,Reach-1,7
Up Type=0
Dn Type=3
Dn Slope=0.005

--- TRIB 9 TO KUY CREEK.g01 (geometry) ---

Geom Title=Existing Conditions
Program Version=4.10

River Reach=TRIB 9 TO KUY CR,Reach-1
Reach XY= 30
        2594075.       13396825.      2594262.02     13397011.27
      2594319.38     13397030.62       2594333.3     13397080.74
      2594419.16     13397172.71      2594475.46     13397314.81
      2594472.76     13397819.07      2594378.83     13397976.59
      2594369.48     13398077.43      2594235.78     13398215.32
      2594211.37     13398288.21      2594082.86     13398418.83
      2594071.17     13398523.41      2593978.83     13398676.58
      2593972.65     13398769.03      2593928.85      13398826.6
      2593922.64     13398919.02      2593876.22      13398985.5
      2593873.78     13399164.49      2593825.52     13399240.22
      2593823.78      13399514.5      2593775.52     13399590.22
      2593778.75     13399773.45      2593835.76     13399884.68
      2593969.48     13400022.57      2593978.83     13400123.41
      2594066.98     13400271.69       2593982.5       13400425.
       2594071.4     13400576.49        2594075.       13400625.

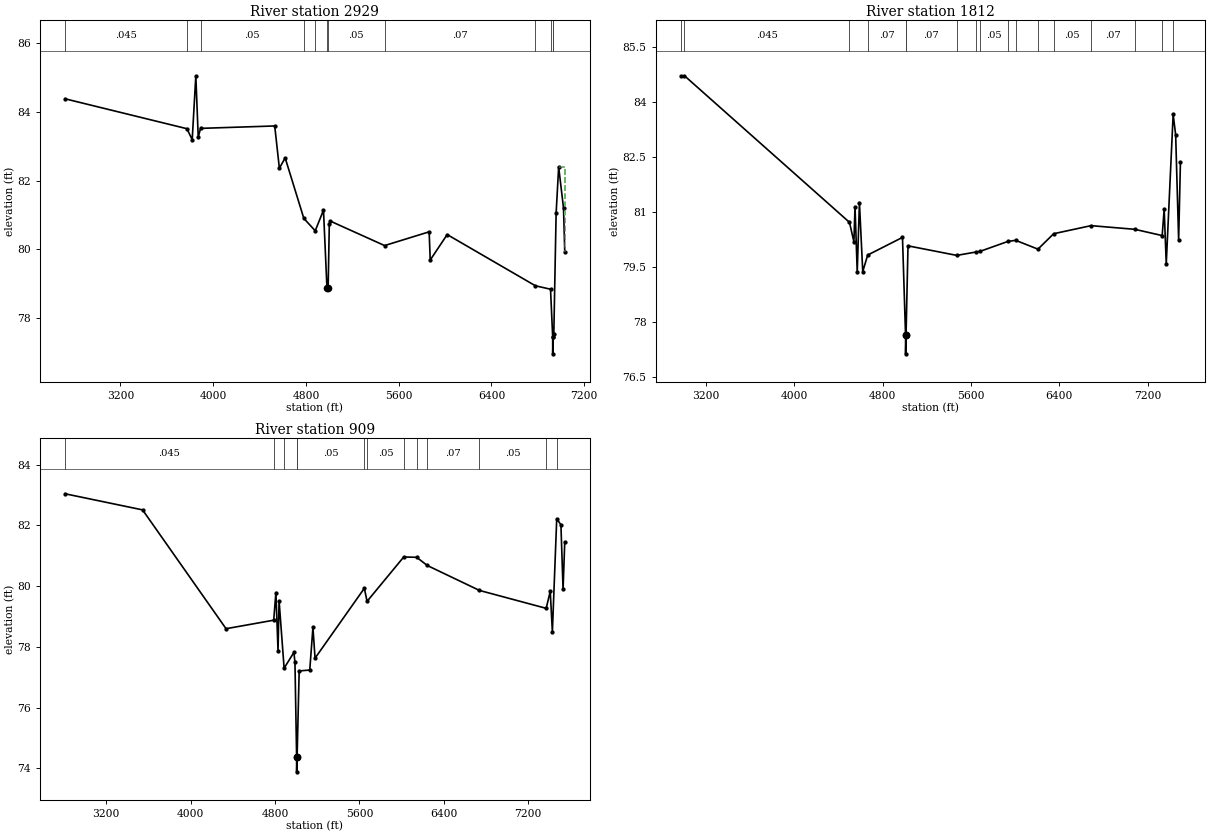
Type RM Length L Ch R = 1 ,2929    ,1117,1117,1117
BEGIN DESCRIPTION:
TRIB 9 TO KUY CREEK 0.0
END DESCRIPTION:
XS GIS Cut Line= 4
      2592151.91     13397639.51      2593475.12     13398021.83
      2595023.64     13398100.27       2596345.3     13397699.61
#Sta/Elev= 30
  2723.4   84.38  3774.2   83.51  3819.6   83.19  3850.8   85.05  3871.6   83.26
  3891.5   83.52  4531.2   83.59  4571.2   82.36  4621.3   82.66  4782.2    80.9
  4880.5   80.54  4951.7   81.14  4981.7   78.87  4991.8   78.88  5001.8   80.73
  5011.8   80.82  5478.6   80.11  5862.9   80.51  5872.1   79.69  6018.4   80.43
  6779.2   78.94  6909.6   78.84    6928   77.46  6928.3   76.96  6932.2   77.46
  6937.9   77.54  6957.8   81.05  6979.7    82.4  7021.5    81.2  7032.3   79.93
#Mann= 12 ,-1 , 0
  2723.4    .045       0  3774.2    .035       0  3891.5     .05       0
  4782.2     .07       0  4880.5     .05       0  4981.7     .05       0
  4991.8     .05       0  5478.6     .07       0  6779.2     .05       0
  6909.6    .063       0    6928     .05       0  6932.2    .063       0
#XS Ineff= 2 , 0
       0                  6979.7       0    82.4
Permanent Ineff=
       F       F
Bank Sta=4981.7,4991.8
XS Rating Curve= 0 ,0
Exp/Cntr=0.3,0.1

Type RM Length L Ch R = 1 ,1812    ,903,903,903
BEGIN DESCRIPTION:
TRIB 9 TO KUY CREEK 2.0
END DESCRIPTION:
XS GIS Cut Line= 4
      2591966.39     13398510.05        2592921.     13399003.37
      2594896.74     13399009.32      2596361.12     13398824.37
#Sta/Elev= 30
  2971.8    84.7  3005.6   84.71  4500.1   80.72  4540.3   80.19  4550.3   81.15
  4570.3   79.37  4590.3   81.26  4620.3   79.38  4665.3   79.83  4980.3   80.31
  5008.2   77.64  5008.5   77.14  5012.5   77.64  5030.3   80.08  5472.2   79.82
  5641.8   79.91  5683.2   79.93  5934.9    80.2  6005.7   80.23  6207.4   79.99
  6349.9   80.41  6688.4   80.63    7085   80.53  7332.8   80.36  7350.8   81.08
  7369.6   79.59  7432.2   83.66  7454.9    83.1  7481.9   80.24  7498.1   82.36
#Mann= 17 ,-1 , 0
  2971.8    .035       0  3005.6    .045       0  4500.1    .035       0
  4665.3     .07       0  5008.2     .05       0  5012.5     .07       0
  5472.2     .05       0  5641.8     .07       0  5683.2     .05       0
  5934.9     .07       0  6005.7     .05       0  6207.4     .07       0
  6349.9     .05       0  6688.4     .07       0    7085     .05       0
  7332.8    .035       0  7432.2    .063       0
Bank Sta=5008.2,5012.5
XS Rating Curve= 0 ,0
Exp/Cntr=0.3,0.1

Type RM Length L Ch R = 1 ,909     ,0,0,0
BEGIN DESCRIPTION:
TRIB 9 TO KUY CREEK 1.0
END DESCRIPTION:
XS GIS Cut Line= 4
      2591765.18     13399475.02      2592605.08     13399952.03
      2594834.24     13399785.36      2596350.93     13399543.12
#Sta/Elev= 30
  2809.8   83.04  3544.4   82.51  4335.8    78.6  4787.6   78.88  4808.5   79.79
  4828.6   77.88  4838.6   79.52  4886.3    77.3    4979   77.82    4989    77.5
  5004.8   74.39  5005.1   73.89  5009.3   74.39  5029.1   77.21  5129.4   77.24
  5159.5   78.64  5179.5   77.63  5646.9   79.93  5672.7    79.5  6020.3   80.96
  6142.8   80.95  6243.7   80.68    6738   79.86  7370.9   79.27  7409.3   79.83
  7429.6    78.5  7470.8   82.22  7510.6   82.02  7530.9    79.9    7547   81.46
#Mann= 13 ,-1 , 0
  2809.8    .045       0  4787.6    .035       0  4886.3     .05       0
  5004.8     .05       0  5009.3     .05       0  5646.9     .07       0
  5672.7     .05       0  6020.3     .07       0  6142.8     .05       0
  6243.7     .07       0    6738     .05       0  7370.9    .035       0
  7470.8    .063       0
Bank Sta=5004.8,5009.3
XS Rating Curve= 0 ,0
Exp/Cntr=0.3,0.1

Chan Stop Cuts=-1
Use User Specified Reach Order=0
Composite Channel Slope=5